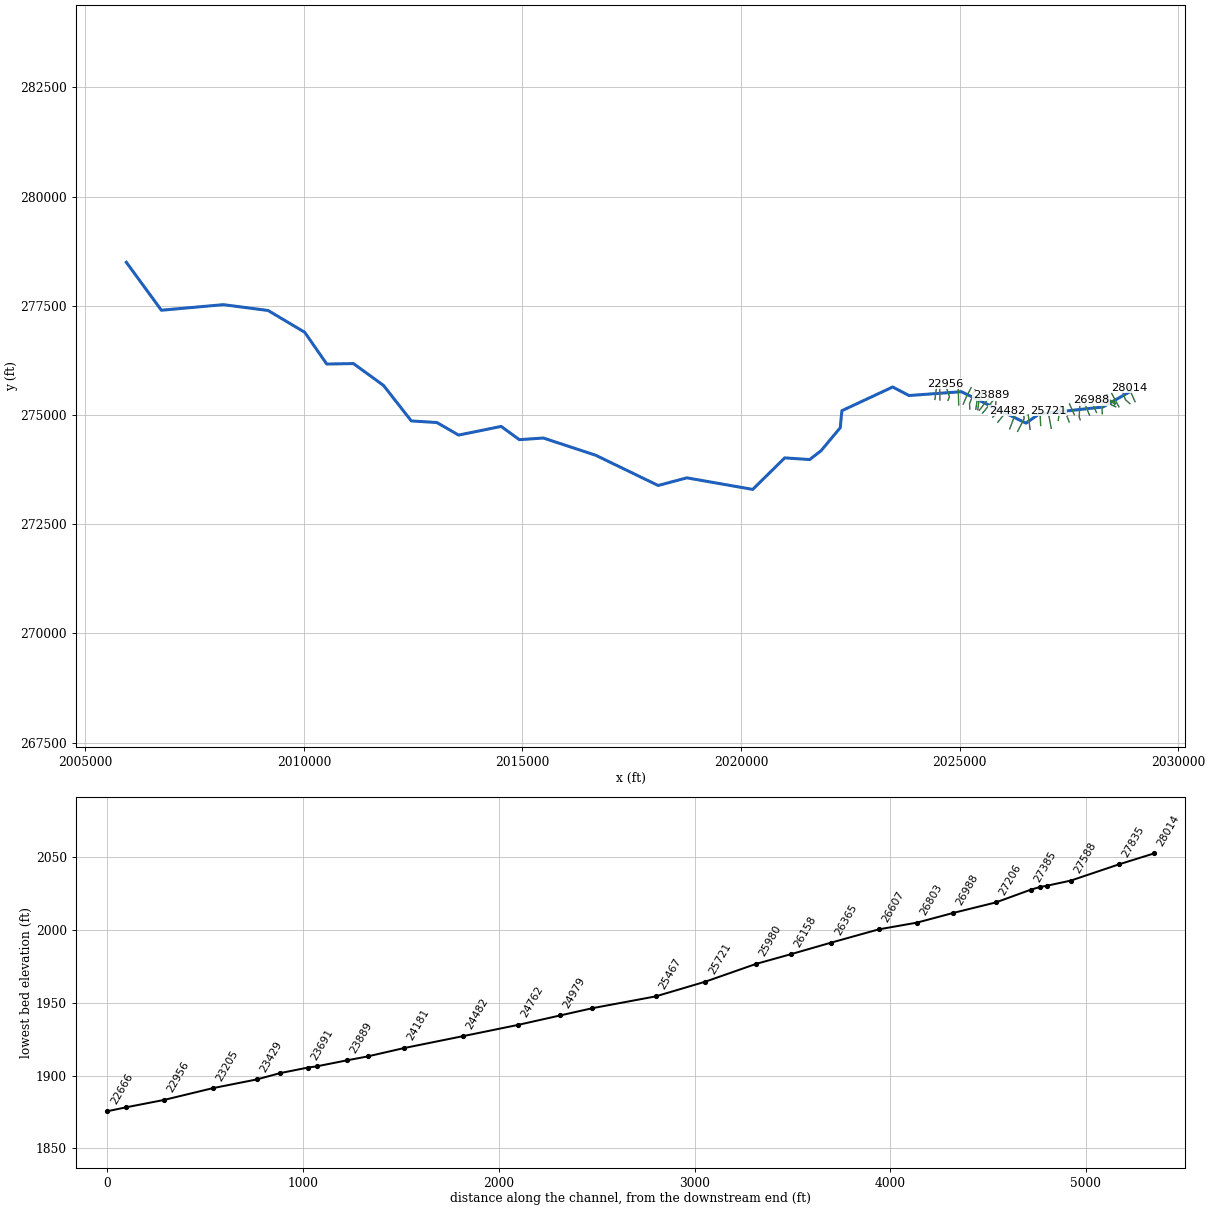
--- LAURELCK_A.prj (project) ---

Proj Title=LAURELCK_A
Current Plan=p01
Default Exp/Contr=0,0
English Units
Geom File=g01
Flow File=f01
Plan File=p01
BEGIN DESCRIPTION:
Stream Name: Laurel Creek
Flood Zone: Approximate
Summers County, West Virginia
HEC-RAS Version: 5.0.7
Hydrology Method:
regression
Model Notes:
KWSEL tie in with LAURELCK_AE, forms coincident peak with LAURELCK_T1
END DESCRIPTION:
DSS File=dss
DSS Export Rating Curves= 0
DSS Export Rating Curve Sorted= 0
DSS Export Volume Flow Curves= 0
DXF OffsetX= 0
DXF OffsetY= 0
DXF ScaleX= 0
DXF ScaleY= 0

--- LAURELCK_A.p01 (plan) ---

Plan Title=Floodplain
Program Version=5.07
Short Identifier=Floodplain
Geom File=g01
Flow File=f01
Subcritical Flow
K Sum by GR= 0
Std Step Tol= 0.01
Critical Tol= 0.01
Num of Std Step Trials= 20
Max Error Tol= 0.3
Flow Tol Ratio= 0.001
Split Flow NTrial= 30
Split Flow Tol= 0.02
Split Flow Ratio= 0.02
Log Output Level= 0
Friction Slope Method= 1
Unsteady Friction Slope Method= 2
Unsteady Bridges Friction Slope Method= 1
Parabolic Critical Depth
Global Vel Dist= 0 , 0 , 0
Global Log Level= 0
CheckData=True
Encroach Param=-1 ,0,0, 0
Computation Interval=0.1SEC
Output Interval=1MIN
Instantaneous Interval=Max Profile
Mapping Interval=1HOUR
Computation Time Step Use Courant=        0
Computation Time Step Use Time Series=    0
Computation Time Step Count To Double=0
Computation Time Step Max Doubling=0
Computation Time Step Max Halving=0
Computation Time Step Residence Courant=0
Run HTab= 0
Run UNet= 0
Run Sediment= 0
Run PostProcess= 0
Run WQNet= 0
Run RASMapper= 0
UNET Theta= 0
UNET Theta Warmup= 0
UNET ZTol= 0
UNET ZSATol= 0
UNET MxIter= 0
UNET Max Iter WO Improvement= 0
UNET MaxInSteps= 0
UNET DtIC= 0
UNET DtMin= 0
UNET MaxCRTS= 0
UNET WFStab= 0
UNET SFStab= 0
UNET WFX= 1
UNET SFX= 1
UNET 1D Methodology=Finite Difference
UNET DSS MLevel= 1
UNET Pardiso=0
UNET DZMax Abort= 0
UNET Use Existing IB Tables= 0
UNET Froude Reduction=False
UNET Froude Limit= 0
UNET Froude Power= 0
UNET D1 Cores= 0
UNET D2 Coriolis=0
UNET D2 Cores= 0
UNET D2 Theta= 1
UNET D2 Theta Warmup= 1
UNET D2 Z Tol= 0.01
UNET D2 Volume Tol= 0.01
UNET D2 Max Iterations= 20
UNET D2 Equation= 0
UNET D2 RampUpFraction=0.1
UNET D2 TimeSlices= 1
UNET D2 BCVolumeCheck=0
UNET D1D2 MaxIter= 0
UNET D1D2 ZTol=0.01
UNET D1D2 QTol=0.1
UNET D1D2 MinQTol=1
DSS File=dss
Write IC File= 0
Write IC File at Fixed DateTime=0
Write IC File at Sim End=0
Echo Input=False
Echo Parameters=False
Echo Output=False
Write Detailed= 0
HDF Write Warmup=0
HDF Write Time Slices=0
HDF Flush=0
HDF Face Node Velocities=0
HDF Compression= 1
HDF Chunk Size= 1
HDF Spatial Parts= 1
HDF Use Max Rows=0
HDF Fixed Rows= 1
Calibration Method= 0
Calibration Iterations= 20
Calibration Max Change=0.05
Calibration Tolerance=0.2
Calibration Maximum=1.5
Calibration Minimum=0.5
Calibration Optimization Method= 1
WQ AD Non Conservative
WQ ULTIMATE=-1
WQ Max Comp Step=1HOUR
WQ Output Interval=15MIN
WQ Output Selected Increments= 0
WQ Output face flow=0
WQ Output face velocity=0
WQ Output face area=0
WQ Output face dispersion=0
WQ Output cell volume=0
WQ Output cell surface area=0
WQ Output cell continuity=0
WQ Output cumulative cell continuity=0
WQ Output face conc=0
WQ Output face dconc_dx=0
WQ Output face courant=0
WQ Output face peclet=0
WQ Output face adv mass=0
WQ Output face disp mass=0
WQ Output cell mass=0
WQ Output cell source sink temp=0
WQ Output nsm pathways=0
WQ Output nsm derived pathways=0
WQ Output MaxMinRange=-1
WQ Daily Max Min Mean=-1
WQ Daily Range=0
WQ Daily Time=0
WQ Create Restart=0
WQ Fixed Restart=0
WQ System Summary=0
WQ Write To DSS=0
WQ Use Fixed Temperature=0
Sorting and Armoring Iterations= 10
XS Update Threshold= 0.02
Bed Roughness Predictor= 0
Hydraulics Update Threshold= 0.02
Energy Slope Method= 1
Volume Change Method= 1
Sediment Retention Method= 0
XS Weighting Method= 0
Number of US Weighted Cross Sections= 1
Number of DS Weighted Cross Sections= 1
Upstream XS Weight=0
Main XS Weight=1
Downstream XS Weight=0
Number of DS XS's Weighted with US Boundary= 1
Upstream Boundary Weight= 1
Weight of XSs Associated with US Boundary= 0
Number of US XS's Weighted with DS Boundary= 1
Downstream Boundary Weight= 0.5
Weight of XSs Associated with DS Boundary= 0.5
Percentile Method= 0
Sediment Output Level= 3
Mass or Volume Output= 0
Output Increment Type= 1
Profile and TS Output Increment= 1
XS Output Flag= 0
XS Output Increment= 10
Write Gradation File= 0
Read Gradation Hotstart= 0
Write HDF5 File= 1
Write Binary Output= 1
Write DSS Sediment File= 0
SV Curve= 0
Specific Gage Flag= 0

--- LAURELCK_A.f01 (steady flow) ---

Flow Title=Flows
Program Version=5.07
Number of Profiles= 6
Profile Names=01pct,10pct,04pct,02pct,0_2pct,01plus
River Rch & RM=LAURELCK_A,Main            ,28014
     635     337     447     538     885     939
River Rch & RM=LAURELCK_A,Main            ,26158
     707     377     499     600     983    1045
River Rch & RM=LAURELCK_A,Main            ,23429
     820     440     581     697    1138    1213
River Rch & RM=LAURELCK_A,Main            ,20766
     989     534     703     842    1368    1463
River Rch & RM=LAURELCK_A,Main            ,18434
    1881    1041    1353    1609    2569    2781
River Rch & RM=LAURELCK_A,Main            ,14308
    2090    1161    1507    1789    2849    3091
River Rch & RM=LAURELCK_A,Main            ,8154
    2346    1310    1696    2011    3192    3470
River Rch & RM=LAURELCK_A,Main            ,4162
    2723    1529    1974    2337    3694    4028
River Rch & RM=LAURELCK_A,Main            ,0
    3024    1705    2197    2598    4095    4473
Boundary for River Rch & Prof#=LAURELCK_A,Main            , 1
Up Type= 0
Dn Type= 1
Dn Known WS=1486.3
Boundary for River Rch & Prof#=LAURELCK_A,Main            , 2
Up Type= 0
Dn Type= 1
Dn Known WS=1485.3
Boundary for River Rch & Prof#=LAURELCK_A,Main            , 3
Up Type= 0
Dn Type= 1
Dn Known WS=1485.8
Boundary for River Rch & Prof#=LAURELCK_A,Main            , 4
Up Type= 0
Dn Type= 1
Dn Known WS=1486
Boundary for River Rch & Prof#=LAURELCK_A,Main            , 5
Up Type= 0
Dn Type= 1
Dn Known WS=1486.8
Boundary for River Rch & Prof#=LAURELCK_A,Main            , 6
Up Type= 0
Dn Type= 1
Dn Known WS=1487
DSS Import GetInterval= 0
DSS Import GetPeak= 0
DSS Import FillOption= 0

--- LAURELCK_A.g01 (geometry) ---

Geom Title=Geometry
Program Version=5.07

River Reach=LAURELCK_A      ,Main
Reach XY= 30
     2028911.731275543.4259999132028278.80414911275183.568506766
2026818.20007045275023.4896312342026518.09906771 274813.81237681
2025039.70206387275533.1307730432023842.35167731275445.235773048
2023468.28699999 275640.760999912022306.11964537275097.861836925
2022269.23962357274707.862222664     2021833.389 274184.87599991
     2021569.849273979.3029999092020999.53699999 274017.49799991
2020267.12664208273295.939936032      2018759.72273560.528999912
2018104.19064537273385.9015527522016672.60599892274079.129999915
2015478.70299999274472.3589999122014928.42594269274434.827996628
     2014513.426274737.9839999082013539.47699999 274539.67899991
2013043.18264208274827.249287368     2012457.918274863.700999905
2011822.50099999275676.2009999132011134.13299999276177.068999915
 2010523.6576723276166.182949491     2010018.792276894.423999918
2009181.25097479277392.623520966     2008160.317277526.139999917
2006740.90399999277398.4239999172005939.63823824278495.791569237

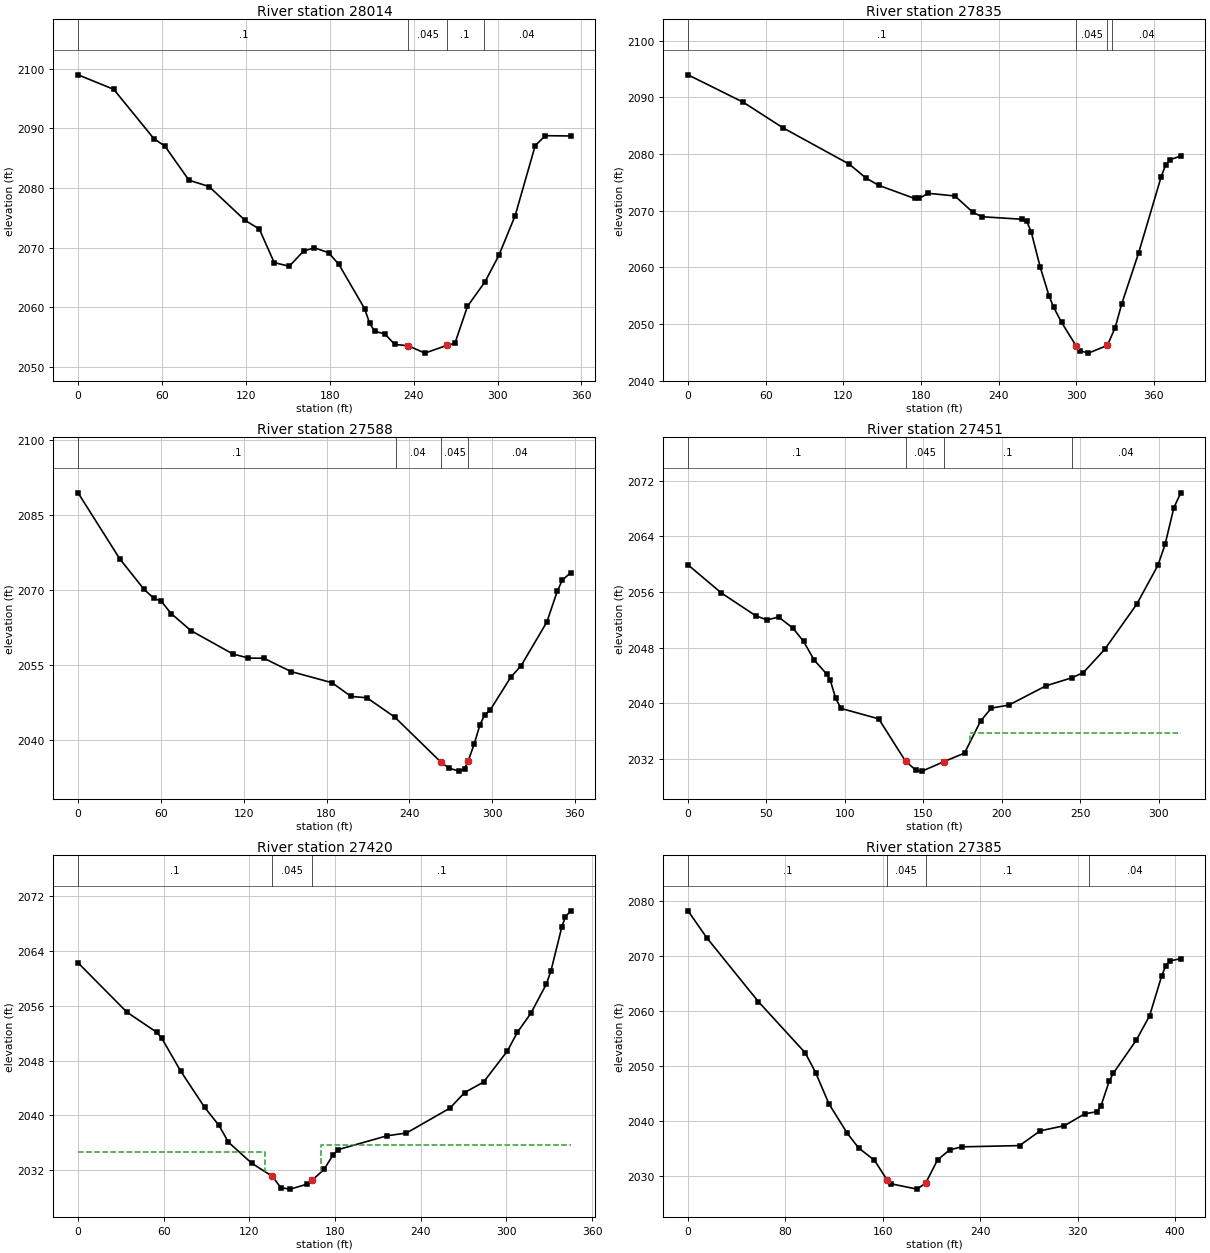
Type RM Length L Ch R = 1 ,28014   ,179.1,179.1,179.1
XS GIS Cut Line= 2
2029012.30860953275304.4603278152028869.60280071275626.618469621
#Sta/Elev= 30
       0 2098.99    25.5 2096.56    54.2  2088.3    62.2 2087.01    79.3 2081.33
    93.7 2080.26   119.4  2074.6   129.6 2073.15   140.3  2067.5   151.1 2066.91
   161.3 2069.46     169 2069.99   179.1 2069.18   186.5 2067.22   204.9  2059.8
   208.5 2057.37   212.1 2055.99   219.3 2055.58   226.4 2053.81   236.3 2053.56
     248 2052.34   263.6 2053.63   269.5 2053.98   278.5 2060.19   290.9 2064.25
   300.9 2068.71   312.6  2075.4   326.9 2087.11   334.1 2088.79   352.4 2088.74
#Mann= 4 ,-1 , 0
       0      .1       0   236.3    .045       0   263.6      .1       0
     290     .04       0
Bank Sta=236.3,263.6
XS Rating Curve= 0 ,0
Exp/Cntr=0.3,0.1

Type RM Length L Ch R = 1 ,27835   ,240.6,246.5,248.3
XS GIS Cut Line= 3
2028894.47424937275260.120559211 2028791.4518772275351.310584435
2028713.24922237275581.591347345
#Sta/Elev= 30
       0 2093.98    42.7 2089.14    73.5 2084.61   124.6 2078.21   137.6 2075.75
   147.4 2074.47   175.1 2072.15   178.6 2072.15   185.5 2073.07   206.3 2072.59
   220.1 2069.72   227.1 2068.93   258.3 2068.48   261.7 2068.14   265.2 2066.28
   272.1 2060.09     279 2054.96   282.5 2052.97   288.7 2050.27   299.8 2046.17
   303.3 2045.26   309.4 2044.85   324.1 2046.22   330.1 2049.36   335.2 2053.57
   348.2 2062.52   365.7 2076.03   369.1 2078.07   372.6    2079   380.8 2079.65
#Mann= 4 ,-1 , 0
       0      .1       0   299.8    .045       0   324.1      .1       0
  327.58     .04       0
Bank Sta=299.8,324.1
XS Rating Curve= 0 ,0
Exp/Cntr=0.3,0.1

Type RM Length L Ch R = 1 ,27588   ,102.8,119,133.9
XS GIS Cut Line= 2
2028643.90412845275186.3209180342028474.48494552275500.573035002
#Sta/Elev= 30
       0 2089.35    30.2 2076.15    47.8 2070.05      55 2068.24    60.1 2067.72
    67.5  2065.2    81.7 2061.81   112.2 2057.12   123.4 2056.31   134.6 2056.27
   154.3 2053.61     184 2051.38   197.8 2048.63   209.2 2048.38   229.4 2044.51
   262.8 2035.52   268.8 2034.28   276.2  2033.7     280 2034.16   282.7 2035.77
   287.1 2039.21   291.2 2043.01   294.6 2044.93   298.6 2045.94   313.5 2052.48
     321 2054.79   339.6  2063.5   347.1 2069.62   350.8 2071.89     357 2073.41
#Mann= 4 ,-1 , 0
       0      .1       0     230     .04       0   262.8    .045       0
   282.7     .04       0
Bank Sta=262.8,282.7
XS Rating Curve= 0 ,0
Exp/Cntr=0.5,0.3

Type RM Length L Ch R = 1 ,27451   ,36.9,39.1,42.6
XS GIS Cut Line= 4
2028564.06486077275256.1367249652028538.89124967275308.220058323
2028400.00236077275349.0186694282028371.35652743275456.657558323
#Sta/Elev= 30
       0 2059.91    21.3 2055.86    43.1  2052.6    50.4 2051.99    57.7 2052.41
    66.8 2050.83    73.6 2048.92    80.4 2046.22    88.4 2044.21    90.7  2043.3
    94.1 2040.71    97.5 2039.27   121.5 2037.78   138.6 2031.69   145.4 2030.36
   149.2 2030.26   163.22031.639   176.2 2032.85   186.4 2037.45   193.3 2039.32
   204.4 2039.75   228.2 2042.53   244.4 2043.66   251.9 2044.42   265.5 2047.75
   285.9 2054.24   299.4 2059.82     304 2062.84   309.6 2068.13     314 2070.26
#Mann= 4 ,-1 , 0
       0      .1       0   138.6    .045       0   163.2      .1       0
   244.4     .04       0
#XS Ineff= 2 , 0
           127.6  2034.7     180          2035.7
Permanent Ineff=
       F       F
Bank Sta=138.6,163.2
XS Rating Curve= 0 ,0
Exp/Cntr(USF)=0,0
Exp/Cntr=0.5,0.3

Type RM Length L Ch R = 1 ,27420   ,49.7,45,39.8
XS GIS Cut Line= 4
 2028543.6460421275231.1865249782028523.77428566275282.593894905
2028374.73611234275311.9695348642028342.76850415275446.319888205
#Sta/Elev= 30
       0 2062.28    34.2 2055.08    55.1 2052.14    58.5 2051.32    71.8  2046.5
    88.6 2041.19    98.6 2038.58   105.3  2036.1   121.5 2033.05   136.1 2031.11
   142.1 2029.44   148.7 2029.25   160.6 2029.99   163.82030.518   172.2 2032.12
   178.8  2034.3   182.2 2035.02   216.5 2037.04     230 2037.44   260.4 2041.07
   270.7 2043.34     284 2044.88   300.7 2049.42   307.6 2052.12   317.1 2054.91
     328  2059.2   331.2 2061.13   338.8 2067.52   341.3 2069.02   345.1 2069.87
#Mann= 3 , 0 , 0
       0      .1       0   136.1    .045       0   163.8      .1       0
#XS Ineff= 2 , 0
             131  2034.7     170          2035.7
Permanent Ineff=
       F       F
Bank Sta=136.1,163.8
XS Rating Curve= 0 ,0
Exp/Cntr(USF)=0,0
Exp/Cntr=0.5,0.3

Type RM Length L Ch R = 1 ,27385   ,202.6,179.5,146.1
XS GIS Cut Line= 3
2028569.62579961275186.7142523642028343.49025738 275291.78977811
2028317.50571263275444.851078976
#Sta/Elev= 30
       0 2078.23    15.5  2073.3    57.8 2061.68    96.3 2052.35   104.8 2048.76
   115.7 2043.07   130.8  2037.7   140.1 2035.03   153.1 2032.78   163.5  2029.2
   166.3 2028.52     188 2027.53   195.1 2028.61   204.9 2032.85   214.8 2034.68
   224.7 2035.23   272.2 2035.46   289.2 2038.15   309.1 2039.09   325.8 2041.26
   335.8 2041.63   339.1 2042.72   345.8 2047.16   349.2 2048.64     368 2054.65
     379 2059.11     389 2066.42   392.3 2068.24   395.7 2069.11   404.6 2069.51
#Mann= 4 ,-1 , 0
       0      .1       0   163.5    .045       0   195.1      .1       0
  329.36     .04       0
Bank Sta=163.5,195.1
XS Rating Curve= 0 ,0
Exp/Cntr=0.3,0.1

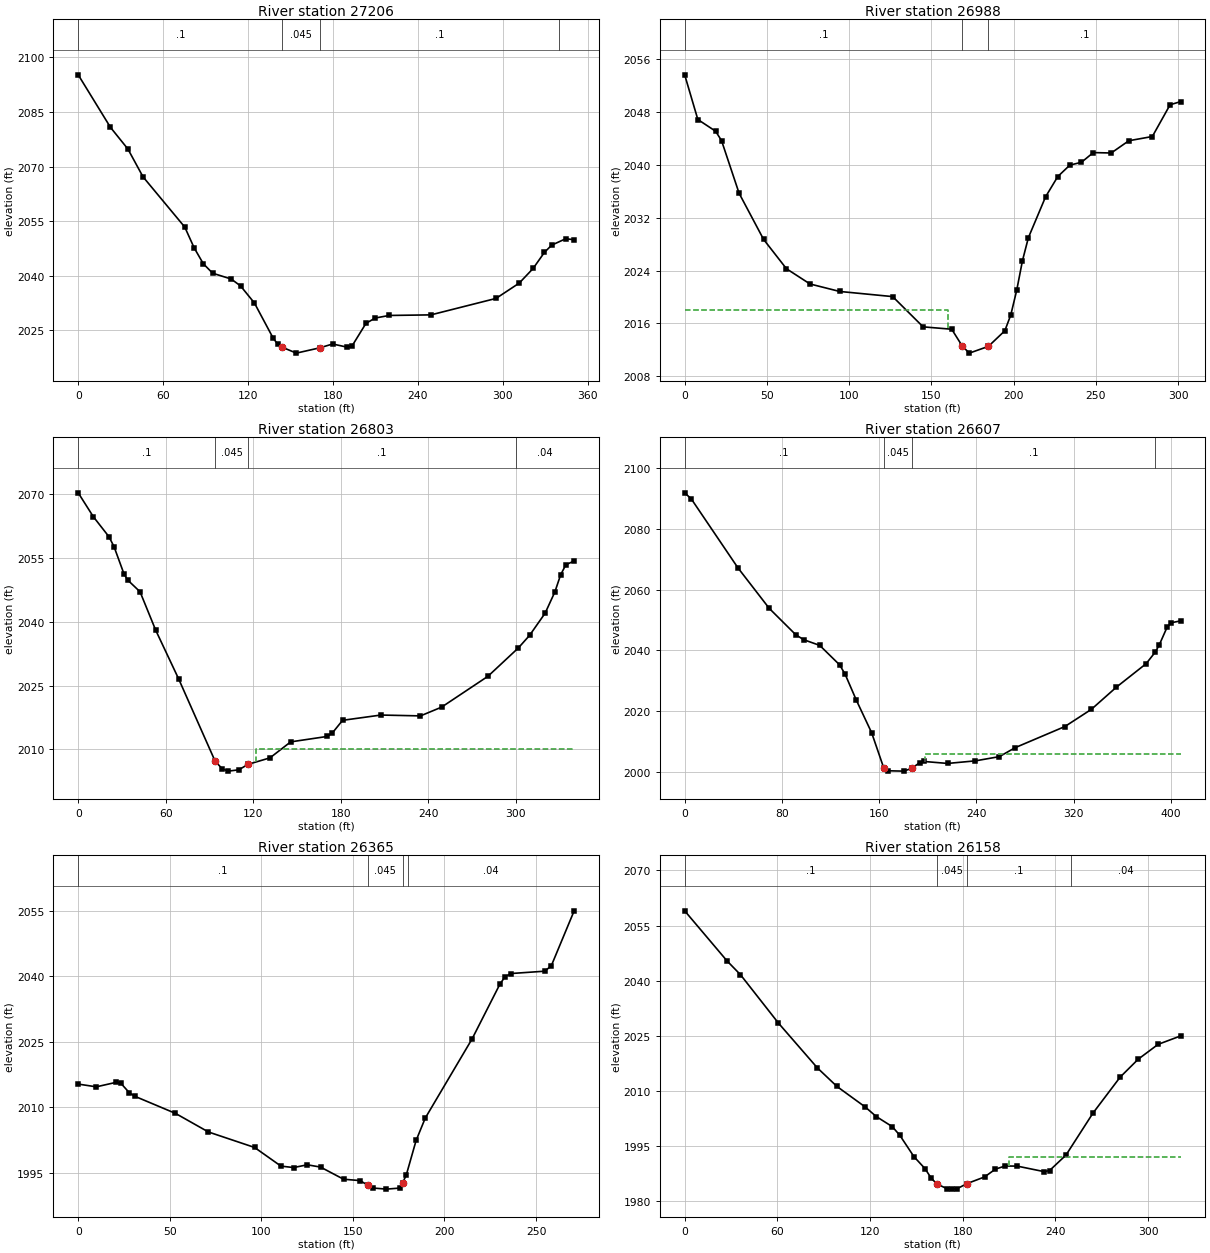
Type RM Length L Ch R = 1 ,27206   ,209.8,218,221.6
XS GIS Cut Line= 2
2028260.88993153275029.365858054     2028256.264275379.745671651
#Sta/Elev= 30
       0  2095.2    22.8 2080.76    35.1 2074.82    45.8 2067.17    75.3 2053.36
    81.9 2047.68    88.4 2043.29      95 2040.69   108.1  2039.1   114.7  2037.2
   124.5 2032.51   137.7 2022.89   140.9  2021.2   144.2 2020.35   154.1 2018.74
   170.5 2020.18   179.8 2021.25   190.2 2020.36   193.4 2020.66   203.3 2026.91
   209.8 2028.38   219.7 2029.09   249.2 2029.25   295.2 2033.77   311.6 2037.98
   321.4    2042   329.4 2046.42   334.5  2048.4   344.4 2050.16   350.4 2049.91
#Mann= 4 ,-1 , 0
       0      .1       0   144.2    .045       0   170.5      .1       0
     340     .04       0
Bank Sta=144.2,170.5
XS Rating Curve= 0 ,0
Exp/Cntr=0.3,0.1

Type RM Length L Ch R = 1 ,26988   ,184.5,184.2,181
XS GIS Cut Line= 2
2028130.33527136275057.9817311462028007.94314542275333.659977529
#Sta/Elev= 30
       0 2053.57       8 2046.82    18.8 2045.05    22.4 2043.64    33.1 2035.67
      48  2028.7    61.9 2024.27    76.2 2021.97    94.2 2020.84   126.5 2020.06
     145 2015.49   162.4 2015.13   168.8 2012.59   173.1 2011.52   184.7 2012.54
   194.7  2014.9   198.3 2017.28   201.9 2020.99   205.4 2025.47     209 2028.95
   219.5 2035.15   226.9  2038.2   234.2 2039.92   241.3 2040.36   248.5 2041.82
   259.4 2041.76   270.1 2043.61   284.4 2044.25   295.2 2049.05   301.6 2049.52
#Mann= 3 ,-1 , 0
       0      .1       0   168.8    .045       0   184.7      .1       0
#XS Ineff= 2 , 0
             160    2018
Permanent Ineff=
       F       F
Bank Sta=168.8,184.7
XS Rating Curve= 0 ,0
Exp/Cntr=0.3,0.1

Type RM Length L Ch R = 1 ,26803   ,204.8,196.1,185.3
XS GIS Cut Line= 2
2027971.23363042274996.678877225 2027839.0853973275310.096295369
#Sta/Elev= 30
       0 2070.36    10.4 2064.73    21.1 2060.03    24.6 2057.67    31.3 2051.37
    33.8 2049.89    42.4 2047.09    53.1 2038.08    68.9 2026.58    93.9 2007.24
    98.9 2005.42     103 2004.91   110.1 2005.22   116.5 2006.51   131.5 2008.03
   145.7 2011.79   170.6 2013.06   174.2 2013.85   181.3 2016.86   207.6  2018.1
   234.7  2017.9   249.2 2019.96     281 2027.22   301.8 2033.87   309.5 2036.82
   320.2 2042.06   326.9 2047.07   330.8 2051.05   334.4 2053.44   340.1 2054.33
#Mann= 4 ,-1 , 0
       0      .1       0    93.9    .045       0   116.5      .1       0
     300     .04       0
#XS Ineff= 2 , 0
                             122            2010
Permanent Ineff=
       F       F
Bank Sta=93.9,116.5
XS Rating Curve= 0 ,0
Exp/Cntr=0.3,0.1

Type RM Length L Ch R = 1 ,26607   ,233.5,242.4,249.7
XS GIS Cut Line= 3
2027758.37103497274889.5970087242027734.98349298274952.378911596
 2027753.3577694275292.901843737
#Sta/Elev= 30
       0  2091.8     5.4 2089.82    43.8 2067.13    69.6 2053.78    91.4 2045.12
    97.9 2043.49   111.1 2041.62   127.5  2035.2     132 2032.13   141.3 2023.53
   153.8  2012.9   163.7 2001.38   166.9 2000.38   180.1 2000.26   186.7 2001.14
   193.2 2003.01   196.5 2003.45   216.3 2002.79   239.2 2003.64   258.9 2005.03
   271.9 2007.98   312.8 2014.93   334.6 2020.59   355.2 2027.89   379.6 2035.59
   387.1 2039.39   390.4 2041.75   396.9 2047.63   400.2 2049.06     408 2049.68
#Mann= 4 ,-1 , 0
       0      .1       0   163.7    .045       0   186.7      .1       0
     387     .04       0
#XS Ineff= 2 , 0
                             198            2006
Permanent Ineff=
       F       F
Bank Sta=163.7,186.7
XS Rating Curve= 0 ,0
Exp/Cntr=0.3,0.1

Type RM Length L Ch R = 1 ,26365   ,204.2,207.3,201
XS GIS Cut Line= 2
2027623.65021689275007.0363257182027512.33711677275253.847614406
#Sta/Elev= 30
       0  2015.3     9.9 2014.67    20.7  2015.7    23.3 2015.48    27.9 2013.32
    30.8 2012.52    53.1 2008.58    71.1 2004.31    96.3 2000.76   110.7 1996.48
   117.6 1996.15   125.1 1996.78   132.3 1996.26   144.9 1993.47   153.9 1993.16
   158.1  1992.1   161.1 1991.45   168.3  1991.2   175.5 1991.44   177.1 1992.63
   179.1 1994.39   184.5 2002.36   189.5  2007.5   215.1 2025.69   230.2 2038.18
   233.1 2039.96   236.5 2040.67   254.7  2041.2   258.3 2042.42   270.8 2055.05
#Mann= 4 ,-1 , 0
       0      .1       0   158.1    .045       0   177.1      .1       0
     180     .04       0
Bank Sta=158.1,177.1
XS Rating Curve= 0 ,0
Exp/Cntr=0.3,0.1

Type RM Length L Ch R = 1 ,26158   ,184.8,177.9,164.7
XS GIS Cut Line= 2
2027505.10568422274841.2836153992027390.83972245275141.218984149
#Sta/Elev= 30
       0    2059    27.4 2045.37    36.1 2041.61    60.7 2028.42    85.9 2016.22
    98.6 2011.16   116.8  2005.6     124 2002.98   134.4 2000.22   139.3 1997.84
   148.4 1992.05   155.5 1988.82   159.6 1986.19   163.2 1984.63   169.5 1983.38
     173 1983.21   176.5 1983.35   182.5 1984.68   194.1 1986.53   201.1 1988.65
   207.4 1989.51   215.2 1989.48   232.7 1987.97   236.2 1988.28   246.8 1992.48
   264.3 2003.93   281.9 2013.73   293.6 2018.61   306.4 2022.63     321 2024.93
#Mann= 4 ,-1 , 0
       0      .1       0   163.2    .045       0   182.5      .1       0
     250     .04       0
#XS Ineff= 2 , 0
                             210            1992
Permanent Ineff=
       F       F
Bank Sta=163.2,182.5
XS Rating Curve= 0 ,0
Exp/Cntr=0.3,0.1

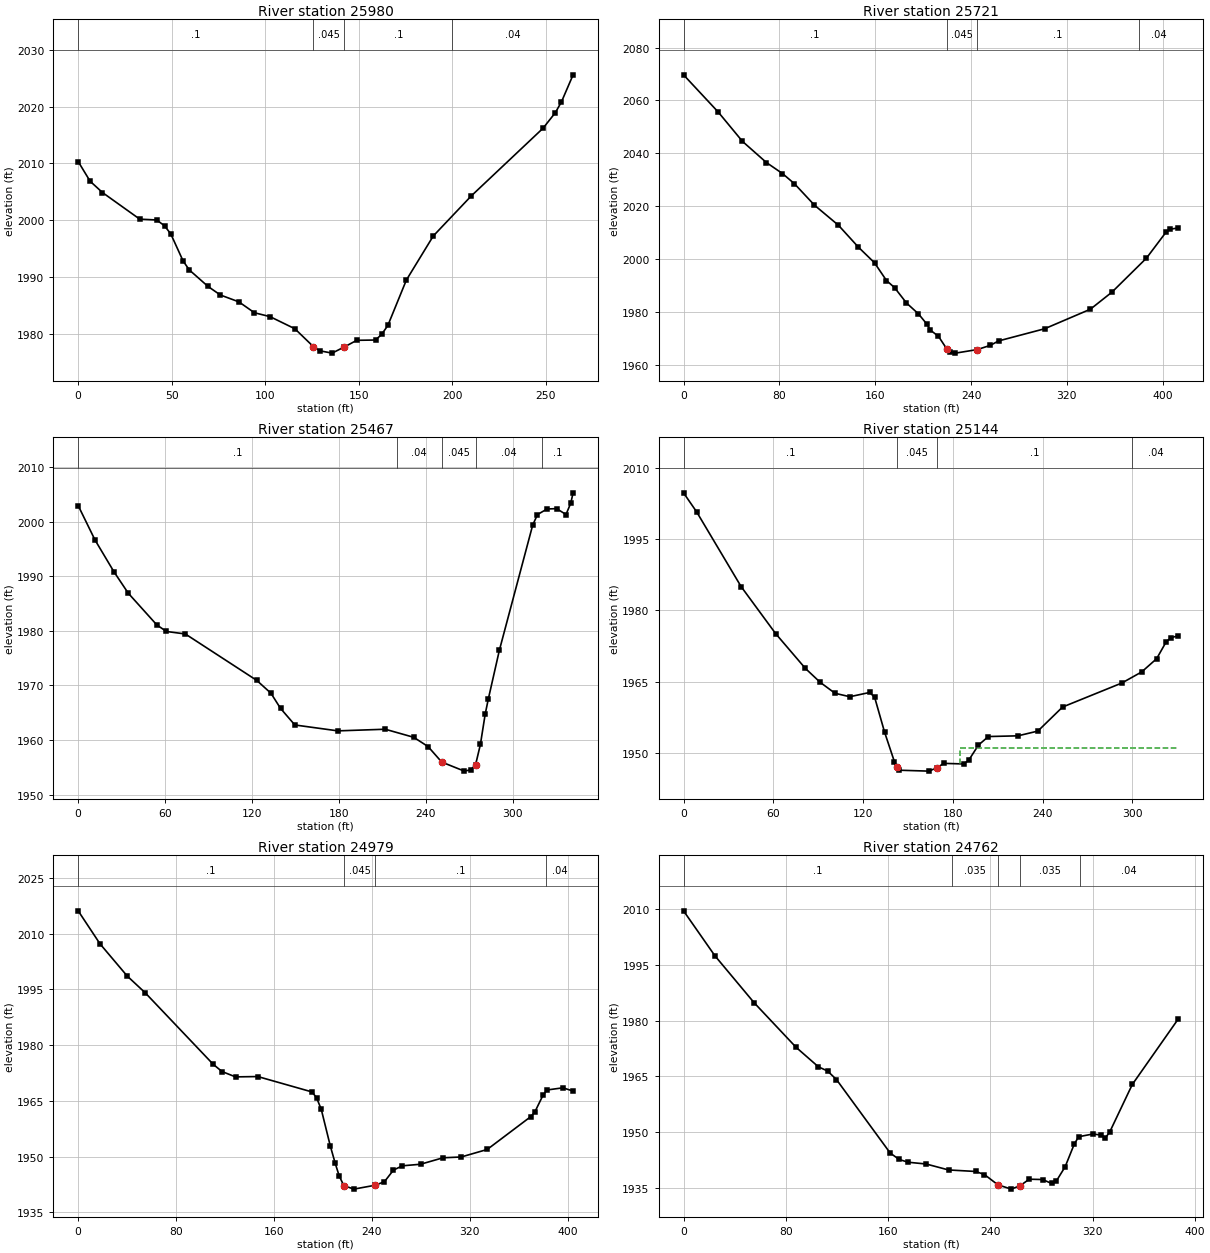
Type RM Length L Ch R = 1 ,25980   ,252,258.5,262.3
XS GIS Cut Line= 2
2027255.48558835274875.2521365342027293.12285587275137.081251117
#Sta/Elev= 30
       0 2010.34     6.4 2006.86      13 2004.87    32.9 2000.18      42 2000.03
    46.2 1998.99    49.5 1997.57    56.1 1992.79    59.4 1991.22    69.4 1988.31
      76  1986.8    85.9 1985.59    94.2 1983.67   102.5 1982.99   115.8 1980.85
   125.7  1977.7     129 1976.97   135.7 1976.55   142.3 1977.65   148.9 1978.81
   158.9 1978.86   162.2 1979.86   165.5 1981.43   175.4 1989.44   189.8 1997.22
   210.1 2004.28   248.4  2016.2     255 2018.95   258.3 2020.88   264.5 2025.63
#Mann= 4 ,-1 , 0
       0      .1       0   125.7    .045       0   142.3      .1       0
     200     .04       0
Bank Sta=125.7,142.3
XS Rating Curve= 0 ,0
Exp/Cntr=0.3,0.1

Type RM Length L Ch R = 1 ,25721   ,254.5,253.8,247.4
XS GIS Cut Line= 2
2027095.06349955274695.4249489522027018.69855572275101.415789536
#Sta/Elev= 30
       0 2069.68    28.9 2055.63    49.2  2044.5    69.2 2036.49    82.6 2032.33
    92.6 2028.47   109.3 2020.36   129.3 2012.77     146 2004.46   159.4 1998.57
   169.4 1991.86   176.1 1989.19   186.1 1983.36   196.1 1979.23   203.1 1975.37
   206.1 1973.08   212.8 1970.73   219.5 1966.13   222.7  1964.8     227 1964.39
   245.2 1965.74   256.2 1967.35   262.9    1969   301.4 1973.61   339.6 1981.01
   357.6 1987.47   386.4 2000.34   403.1 2010.38   406.4  2011.3   413.1 2011.75
#Mann= 4 ,-1 , 0
       0      .1       0   219.5    .045       0   245.2      .1       0
     380     .04       0
Bank Sta=219.5,245.2
XS Rating Curve= 0 ,0
Exp/Cntr(USF)=0,0
Exp/Cntr=0.3,0.1

Type RM Length L Ch R = 1 ,25467   ,321.5,323.4,323.8
XS GIS Cut Line= 2
2026853.83244187274758.4840262982026835.46618956275099.709661361
#Sta/Elev= 30
       0 2002.92    11.6 1996.63    24.7  1990.8    34.6 1986.87    54.3 1981.07
    60.9 1979.87      74 1979.41   123.3 1970.91   133.1 1968.56   139.7 1965.79
   149.6 1962.75   179.3 1961.67     212 1961.97   231.7 1960.49   241.6 1958.79
     251 1955.96   266.6  1954.3   271.1 1954.55   274.4  1955.5   277.7 1959.18
     281 1964.72   283.1 1967.42   290.8 1976.43   313.8 1999.34   317.1 2001.27
   323.7 2002.29   330.3 2002.36   336.8 2001.28   340.1 2003.37   341.7 2005.25
#Mann= 5 ,-1 , 0
       0      .1       0     220     .04       0     251    .045       0
   274.4     .04       0     320      .1       0
Bank Sta=251,274.4
XS Rating Curve= 0 ,0
Exp/Cntr(USF)=0,0
Exp/Cntr=0.3,0.1

Type RM Length L Ch R = 1 ,25144   ,176.7,164.6,149.4
XS GIS Cut Line= 2
2026610.79703022274672.7777277682026569.92535231 275001.16051924
#Sta/Elev= 30
       0 2004.71     8.7 2000.74    38.5    1985    61.6 1975.11    81.5 1967.79
    91.4 1964.87   101.3 1962.57   111.2 1961.85   124.5 1962.75   127.8  1961.7
   134.4 1954.42     141 1948.18   142.8 1947.18   144.3  1946.4   164.1 1946.21
   169.3  1946.9     174 1947.84   187.3 1947.72   190.6 1948.47   197.2 1951.69
   203.8 1953.48   223.6 1953.63   236.9 1954.63   253.4 1959.68   293.1 1964.74
   306.3 1967.06   316.3 1969.84   322.8 1973.45   326.1 1974.28   330.9 1974.67
#Mann= 4 ,-1 , 0
       0      .1       0   142.8    .045       0   169.3      .1       0
     300     .04       0
#XS Ineff= 2 , 0
                             185            1951
Permanent Ineff=
       F       F
Bank Sta=142.8,169.3
XS Rating Curve= 0 ,0
Exp/Cntr(USF)=0,0
Exp/Cntr=0.3,0.1

Type RM Length L Ch R = 1 ,24979   ,215,217.6,219.5
XS GIS Cut Line= 3
2026327.68871159274626.1123447552026474.78262381274912.630184917
2026468.39374921 274994.79279636
#Sta/Elev= 30
       0 2016.16    17.9 2007.25    40.1  1998.6    54.8 1994.09   110.2 1974.89
   117.5  1972.9   128.6 1971.45   146.8 1971.54   191.3 1967.38     195 1965.71
   198.7 1962.68     206 1952.94   210.1 1948.15   213.4 1944.73   217.1 1942.19
   225.3 1941.23   242.9 1942.29   250.3 1943.23   257.7 1946.36     265 1947.51
   279.8 1947.93   298.2 1949.67     313 1949.88   334.3 1951.91   369.9 1960.75
   373.2 1961.99   379.8 1966.44   383.1 1967.92   396.2 1968.51   404.5 1967.63
#Mann= 4 ,-1 , 0
       0      .1       0   217.1    .045       0   242.9      .1       0
  382.07     .04       0
Bank Sta=217.1,242.9
XS Rating Curve= 0 ,0
Exp/Cntr=0.3,0.1

Type RM Length L Ch R = 1 ,24762   ,284,279.9,274.4
XS GIS Cut Line= 2
2026146.56697492274684.3883572952026282.98499064275046.597457788
#Sta/Elev= 30
       0 2009.54    24.6 1997.42    55.2 1984.82      88 1972.83   105.5 1967.57
   112.6 1966.46   119.6 1964.15   161.6 1944.39   168.6 1942.66   175.7 1941.91
   189.7 1941.44   207.2 1939.84   228.4 1939.43   235.3  1938.6   245.8 1935.84
   256.3 1934.68   263.3 1935.62   270.3 1937.35   280.8 1937.26   287.8  1936.2
   291.3 1936.74   298.4  1940.7   305.4 1946.69   308.9 1948.77   320.1 1949.51
   326.4 1949.23   329.9 1948.44   333.4 1950.16   350.9 1962.83     387 1980.53
#Mann= 5 ,-1 , 0
       0      .1       0     210    .035       0   245.8    .045       0
   263.3    .035       0     310     .04       0
Bank Sta=245.8,263.3
XS Rating Curve= 0 ,0
Exp/Cntr=0.3,0.1

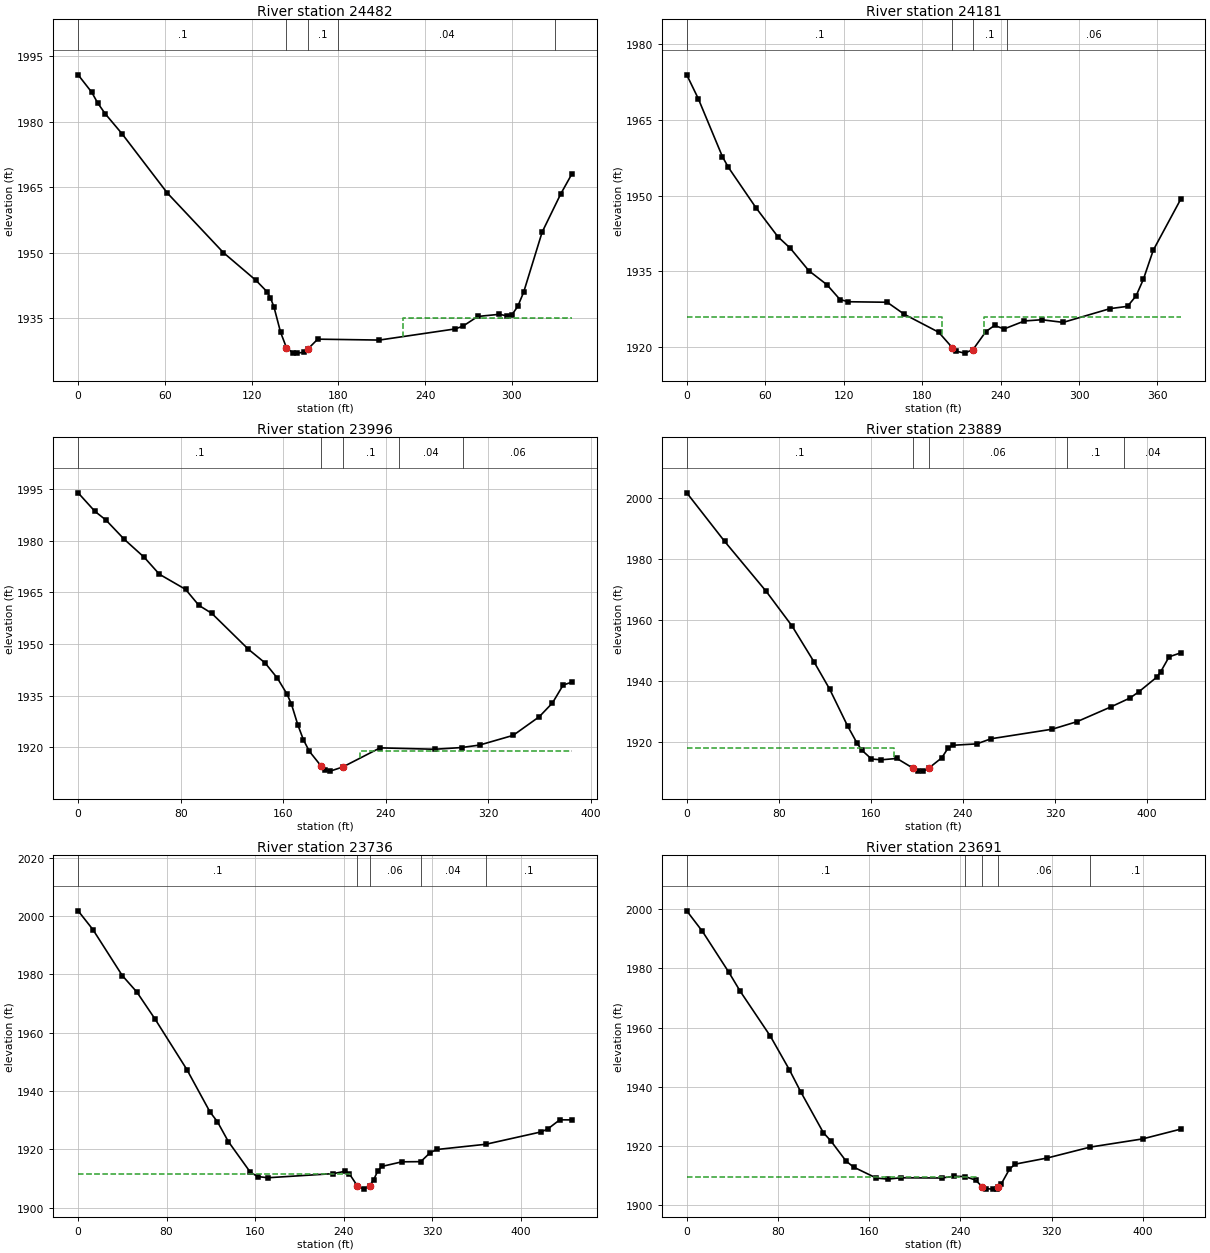
Type RM Length L Ch R = 1 ,24482   ,287.1,301,311.3
XS GIS Cut Line= 2
2025873.55737306274834.9171667532026087.57254474275101.131160794
#Sta/Elev= 30
       0 1990.73     9.4 1986.75    13.6 1984.25    18.7 1981.83    30.4 1977.22
    61.7 1963.66   100.4 1950.04     123 1943.66   130.7 1941.04     133 1939.64
   135.4 1937.62     140 1931.79   144.1 1928.22   148.3 1927.12   151.7    1927
   156.4 1927.22   158.7 1927.88   165.7  1930.2   208.3 1929.99   260.7 1932.54
   266.1 1933.17   276.4  1935.4   291.4 1935.89   296.4 1935.53   299.8  1935.7
     304 1937.68   308.1 1940.95   320.9 1954.72   333.7 1963.42   341.6 1968.12
#Mann= 5 ,-1 , 0
       0      .1       0   144.1    .045       0   158.7      .1       0
     180     .04       0     330      .1       0
#XS Ineff= 2 , 0
                             225            1935
Permanent Ineff=
       F       F
Bank Sta=144.1,158.7
XS Rating Curve= 0 ,0
Exp/Cntr(USF)=0,0
Exp/Cntr=0.3,0.1

Type RM Length L Ch R = 1 ,24181   ,196.4,185.1,172.2
XS GIS Cut Line= 3
2025757.81125326274951.4239179162025819.33017535275010.405977242
2025828.84341073275302.779411109
#Sta/Elev= 30
       0 1973.87     8.8 1969.17    27.3 1957.68    31.8 1955.59    52.9  1947.6
    69.7 1941.86    79.2 1939.58    93.4 1935.13   107.3 1932.35   117.2 1929.44
   123.5    1929   153.3  1928.9   166.4 1926.52   192.7 1922.97     203 1919.95
   205.8 1919.24   212.5 1918.84   218.9 1919.53   228.8 1923.11   235.4 1924.31
   242.7 1923.62   258.3  1925.2   271.5 1925.44   287.9 1924.92   323.8 1927.64
   337.1 1928.09   343.7 1930.17   349.3 1933.48   356.8 1939.19   377.8 1949.27
#Mann= 4 ,-1 , 0
       0      .1       0     203    .045       0   218.9      .1       0
  245.23     .06       0
#XS Ineff= 2 , 0
             195    1926     227            1926
Permanent Ineff=
       F       F
Bank Sta=203,218.9
XS Rating Curve= 0 ,0
Exp/Cntr(USF)=0,0
Exp/Cntr=0.3,0.1

Type RM Length L Ch R = 1 ,23996   ,106.2,106.9,107.3
XS GIS Cut Line= 2
2025523.78566303275042.1167618272025771.12978278275337.661274152
#Sta/Elev= 30
       0 1993.85    13.1 1988.48    21.7 1985.96      36 1980.37    51.6 1975.14
    63.4 1970.24    83.8 1965.86    94.2 1961.22   104.3 1958.89   132.9 1948.46
   145.8 1944.54   155.4 1940.13   162.9 1935.53   166.4 1932.61   171.4 1926.58
   175.8  1922.2   180.4 1918.89   189.7 1914.55   192.8 1913.42   196.7 1913.13
   206.5 1914.33   235.6 1919.88   278.2 1919.47   299.2 1919.97   313.2 1920.69
   339.4  1923.5   359.8 1928.91   370.1 1932.91   378.4 1938.08   385.4 1938.97
#Mann= 5 ,-1 , 0
       0      .1       0   189.7    .045       0   206.5      .1       0
     250     .04       0     300     .06       0
#XS Ineff= 2 , 0
                             220            1919
Permanent Ineff=
       F       F
Bank Sta=189.7,206.5
XS Rating Curve= 0 ,0
Exp/Cntr(USF)=0,0
Exp/Cntr=0.3,0.1

Type RM Length L Ch R = 1 ,23889   ,150,153.1,156.1
XS GIS Cut Line= 2
2025451.33026103275109.2483215492025715.03217256275447.897092139
#Sta/Elev= 30
       0 2001.72    32.9  1985.8    69.1 1969.36    91.4 1958.08   110.6 1946.25
   124.1 1937.37   139.7 1925.28   148.1 1919.51   152.2 1917.27   160.5  1914.4
   168.9 1914.13   182.6 1914.58   196.6 1911.39   201.3 1910.54   205.5 1910.42
   210.8 1911.55   221.5 1914.76     227 1917.93   231.2  1918.9     252 1919.36
   264.4 1921.04   317.6 1924.18   339.2 1926.66   368.4 1931.47   385.1  1934.4
     393  1936.5   408.4 1941.25   411.7 1942.95   419.1 1947.92   429.2 1949.22
#Mann= 5 ,-1 , 0
       0      .1       0   196.6    .045       0   210.8     .06       0
     330      .1       0     380     .04       0
#XS Ineff= 2 , 0
             180    1918
Permanent Ineff=
       F       F
Bank Sta=196.6,210.8
XS Rating Curve= 0 ,0
Exp/Cntr(USF)=0,0
Exp/Cntr=0.5,0.3

Type RM Length L Ch R = 1 ,23736   ,44.9,44.4,43.4
XS GIS Cut Line= 3
 2025415.2447363275120.9067218482025441.89250841275327.426955716
2025547.37327302275541.164294531
#Sta/Elev= 30
       0 2001.74    13.4  1995.3    39.9 1979.56    53.1  1973.9    69.6 1964.61
    98.3 1947.34   119.3 1932.74   125.9 1929.47   135.8 1922.65   155.7 1912.12
   162.3 1910.65   171.5 1910.23   230.6 1911.64   241.5 1912.46   245.2 1911.59
   252.5 1907.43   258.4 1906.33   263.5 1907.45   267.2 1909.52   270.8 1912.47
   274.5  1914.1   292.7 1915.69   309.8 1915.75   318.4 1918.87   324.5 1919.92
   368.6 1921.71   418.5 1925.94   424.5 1926.92   435.5  1930.1   446.6 1930.06
#Mann= 5 ,-1 , 0
       0      .1       0   252.5    .045       0   263.5     .06       0
   309.8     .04       0   368.6      .1       0
#XS Ineff= 2 , 0
       0     246  1911.4               0
Permanent Ineff=
       F       F
Bank Sta=252.5,263.5
XS Rating Curve= 0 ,0
Exp/Cntr(USF)=0,0
Exp/Cntr=0.5,0.3

Type RM Length L Ch R = 1 ,23691   ,140.8,142.7,144.8
XS GIS Cut Line= 3
2025370.83178278275133.6754459852025400.81052641275345.192137124
 2025502.9603195275539.498808774
#Sta/Elev= 30
       0 1999.35    13.8  1992.4      37 1978.58    46.9 1972.22    73.4 1957.04
      90 1945.77    99.9 1938.37   119.8 1924.55   126.5 1921.71   139.7 1914.97
   146.3 1912.95   166.2 1909.25   176.2 1908.88   187.5 1909.33   223.6 1909.27
   234.7 1909.85   244.2 1909.74   253.3 1908.55     259 1906.38   262.1 1905.67
   268.5 1905.51   271.8 1905.63   273.3  1906.1   275.8 1907.25     283 1912.23
   287.9 1913.93   316.3 1916.02   353.8 1919.68   399.7 1922.44   433.2 1925.74
#Mann= 5 ,-1 , 0
       0      .1       0   244.2     .06       0     259    .045       0
   273.3     .06       0   353.8      .1       0
#XS Ineff= 2 , 0
       0   253.3 1909.47               0
Permanent Ineff=
       F       F
Bank Sta=259,273.3
XS Rating Curve= 0 ,0
Exp/Cntr(USF)=0,0
Exp/Cntr=0.5,0.3

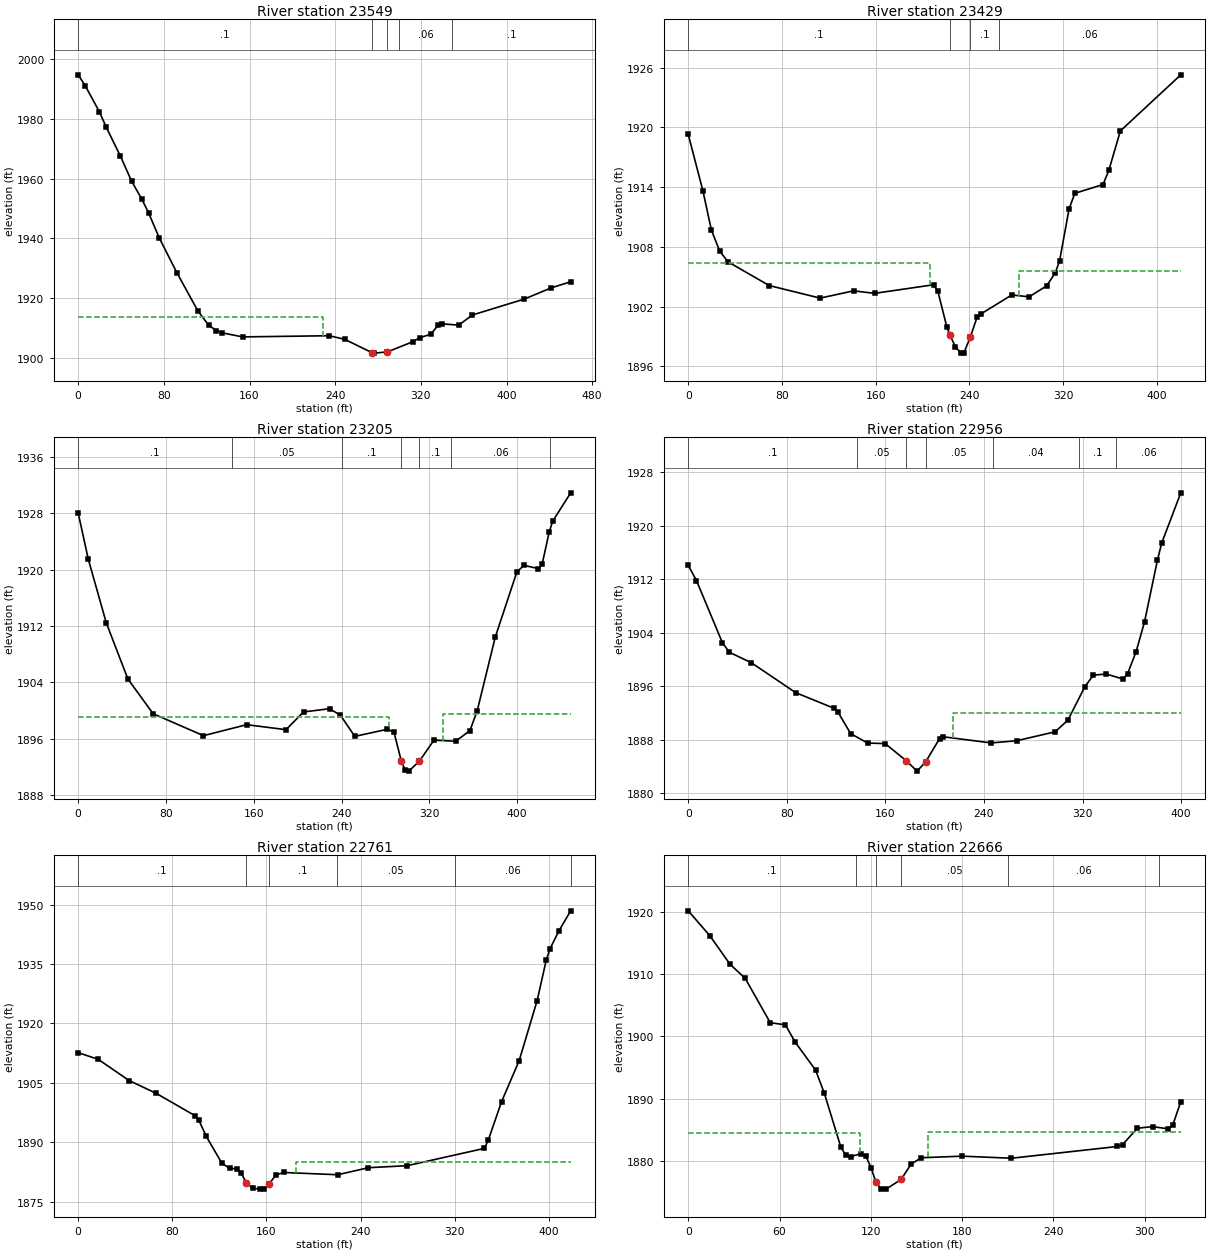
Type RM Length L Ch R = 1 ,23549   ,122,119.8,117.9
XS GIS Cut Line= 3
2025233.78931614 275137.483753582025225.51589818275256.446965326
2025348.34871504275574.138153953
#Sta/Elev= 30
       0 1994.64     6.6    1991    19.7 1982.36    26.3 1977.09    39.5 1967.45
    49.8 1959.18    59.2 1953.26    65.8 1948.52    75.6 1940.25    92.1 1928.59
   111.8 1915.78   121.9    1911   128.9 1909.24   134.6 1908.45   153.5 1907.11
   234.4  1907.5   248.8 1906.31   274.31901.856   276.6 1901.69   288.81902.107
   312.2 1905.46   318.8 1906.81   329.4 1908.02   336.4 1911.18   340.1 1911.47
   355.3 1911.04   368.1 1914.43   416.2  1919.7   441.9 1923.51   459.9 1925.53
#Mann= 5 ,-1 , 0
       0      .1       0   274.3    .045       0   288.8      .1       0
  299.25     .06       0  349.25      .1       0
#XS Ineff= 2 , 0
          228.93 1913.86
Permanent Ineff=
       F       F
Bank Sta=274.3,288.8
XS Rating Curve= 0 ,0
Exp/Cntr(USF)=0,0
Exp/Cntr=0.3,0.1

Type RM Length L Ch R = 1 ,23429   ,214.3,224.4,233.1
XS GIS Cut Line= 3
2025081.64921499275247.2744926332025158.92195568275427.120810076
2025263.81495959275625.990031437
#Sta/Elev= 30
       0 1919.29    12.6 1913.59    19.8 1909.68    26.9 1907.57    34.1 1906.49
    69.2 1904.12   112.6 1902.86   141.2 1903.59   159.1 1903.34   209.5  1904.2
   213.2 1903.53   220.8 1899.97   223.4 1899.18   228.1 1897.97     233 1897.34
   235.5 1897.39   240.8 1898.93   246.6 1900.93   250.3  1901.3   276.3 1903.18
   291.1 1902.99     306 1904.09   313.4 1905.39   317.1  1906.6   325.2 1911.81
   330.1 1913.38   354.2 1914.26   359.2  1915.7     369 1919.64   420.6 1925.27
#Mann= 4 ,-1 , 0
       0      .1       0   223.4    .045       0   240.8      .1       0
  265.74     .06       0
#XS Ineff= 2 , 0
           206.3 1906.42  282.17         1905.62
Permanent Ineff=
       F       F
Bank Sta=223.4,240.8
XS Rating Curve= 0 ,0
Exp/Cntr=0.3,0.1

Type RM Length L Ch R = 1 ,23205   ,242.5,248.4,253
XS GIS Cut Line= 2
2024978.53670169275229.9675673092024966.86930849275678.711888196
#Sta/Elev= 30
       0 1928.07     9.2  1921.5    25.6 1912.45    45.3 1904.47    68.3 1899.53
   114.2 1896.41   153.6 1897.97   189.4 1897.26   205.4 1899.78   229.1 1900.24
     239 1899.32   252.1 1896.31   281.6 1897.31   287.8 1896.93   294.5 1892.81
     298 1891.53   301.3 1891.37     311 1892.79   324.3 1895.78     344 1895.61
   357.1 1897.14   363.7 1899.96   380.1  1910.4   399.8 1919.67   406.3 1920.62
   419.5 1920.14   422.8 1920.74   429.3 1925.36   432.5  1926.9   448.9 1930.92
#Mann= 7 ,-1 , 0
       0      .1       0     140     .05       0     240      .1       0
   294.5    .045       0     311      .1       0     340     .06       0
     430      .1       0
#XS Ineff= 2 , 0
             283    1899   332.3         1899.47
Permanent Ineff=
       F       F
Bank Sta=294.5,311
XS Rating Curve= 0 ,0
Exp/Cntr=0.3,0.1

Type RM Length L Ch R = 1 ,22956   ,200.2,195.3,189.5
XS GIS Cut Line= 3
2024733.43755323275336.3961611412024767.44447332  275416.7452425
2024668.89746662 275713.26181968
#Sta/Elev= 30
       0 1914.09     6.7 1911.82    27.7 1902.53    33.4 1901.09    51.2 1899.53
    87.2 1895.05     118 1892.74   121.4 1892.18   131.8 1888.92   145.6 1887.51
   159.8 1887.43   176.7  1884.9   185.7 1883.31   192.61884.676   203.9 1888.16
   206.5 1888.46   245.9 1887.53   266.6 1887.86   297.7 1889.19   308.1 1890.94
   321.9 1895.96   328.8 1897.67   339.2 1897.84     353 1897.08   356.5 1897.88
   363.4 1901.15   370.3 1905.66   380.7 1914.83   384.2 1917.43   399.7 1924.95
#Mann= 7 ,-1 , 0
       0      .1       0  137.25     .05       0   176.7    .045       0
   192.6     .05       0  247.25     .04       0  317.25      .1       0
  347.25     .06       0
#XS Ineff= 2 , 0
                             215            1892
Permanent Ineff=
       F       F
Bank Sta=176.7,192.6
XS Rating Curve= 0 ,0
Exp/Cntr=0.3,0.1

Type RM Length L Ch R = 1 ,22761   ,97.9,95,92.8
XS GIS Cut Line= 2
2024549.56642051275343.5488017952024541.44300413275762.014495524
#Sta/Elev= 30
       0 1912.65      17 1910.96    43.3 1905.61    66.3 1902.38    99.1 1896.78
   102.4 1895.71   108.9  1891.5     122 1884.81   128.6 1883.45   135.2 1883.36
   138.5 1882.25   142.8 1879.88   148.3 1878.45   154.9 1878.22   158.1 1878.37
   162.4  1879.6     168 1881.77   174.5 1882.42   220.5 1881.85   246.7 1883.63
   279.6 1884.13   345.2  1888.5   348.5 1890.59   359.8  1900.3   374.7 1910.59
     390 1925.77   397.7 1935.94     401 1938.86   408.3 1943.26   418.5 1948.42
#Mann= 6 ,-1 , 0
       0      .1       0   142.8    .045       0   162.4      .1       0
     220     .05       0     320     .06       0  418.54      .1       0
#XS Ineff= 2 , 0
                             185            1885
Permanent Ineff=
       F       F
Bank Sta=142.8,162.4
XS Rating Curve= 0 ,0
Exp/Cntr=0.3,0.1

Type RM Length L Ch R = 1 ,22666   ,78,75.1,72.8
XS GIS Cut Line= 3
2024435.11473581275356.3389893472024464.62862471275583.769544885
2024475.04529139275677.519544885
#Sta/Elev= 30
       0 1920.13    14.2 1916.14    27.4 1911.59    37.4 1909.32    53.9 1902.21
    63.8 1901.87    70.4 1899.06    83.7 1894.61    89.4 1890.94   100.2 1882.35
   103.5 1880.94   106.8 1880.77   113.5 1881.22   116.8 1880.81   120.1    1879
   123.4 1876.64   126.7 1875.62     130 1875.55   139.9  1877.1   146.5 1879.57
   153.2 1880.58   180.1 1880.83   212.4  1880.5   282.1 1882.38   285.4 1882.67
   295.2 1885.31   305.2 1885.56   315.1 1885.22   318.4 1885.79   323.7 1889.55
#Mann= 6 ,-1 , 0
       0      .1       0     110     .05       0   123.4    .045       0
   139.9     .05       0     210     .06       0  309.34     .04       0
#XS Ineff= 2 , 0
          112.73 1884.53  157.76         1884.63
Permanent Ineff=
       F       F
Bank Sta=123.4,139.9
XS Rating Curve= 0 ,0
Exp/Cntr(USF)=0,0
Exp/Cntr=0.3,0.1