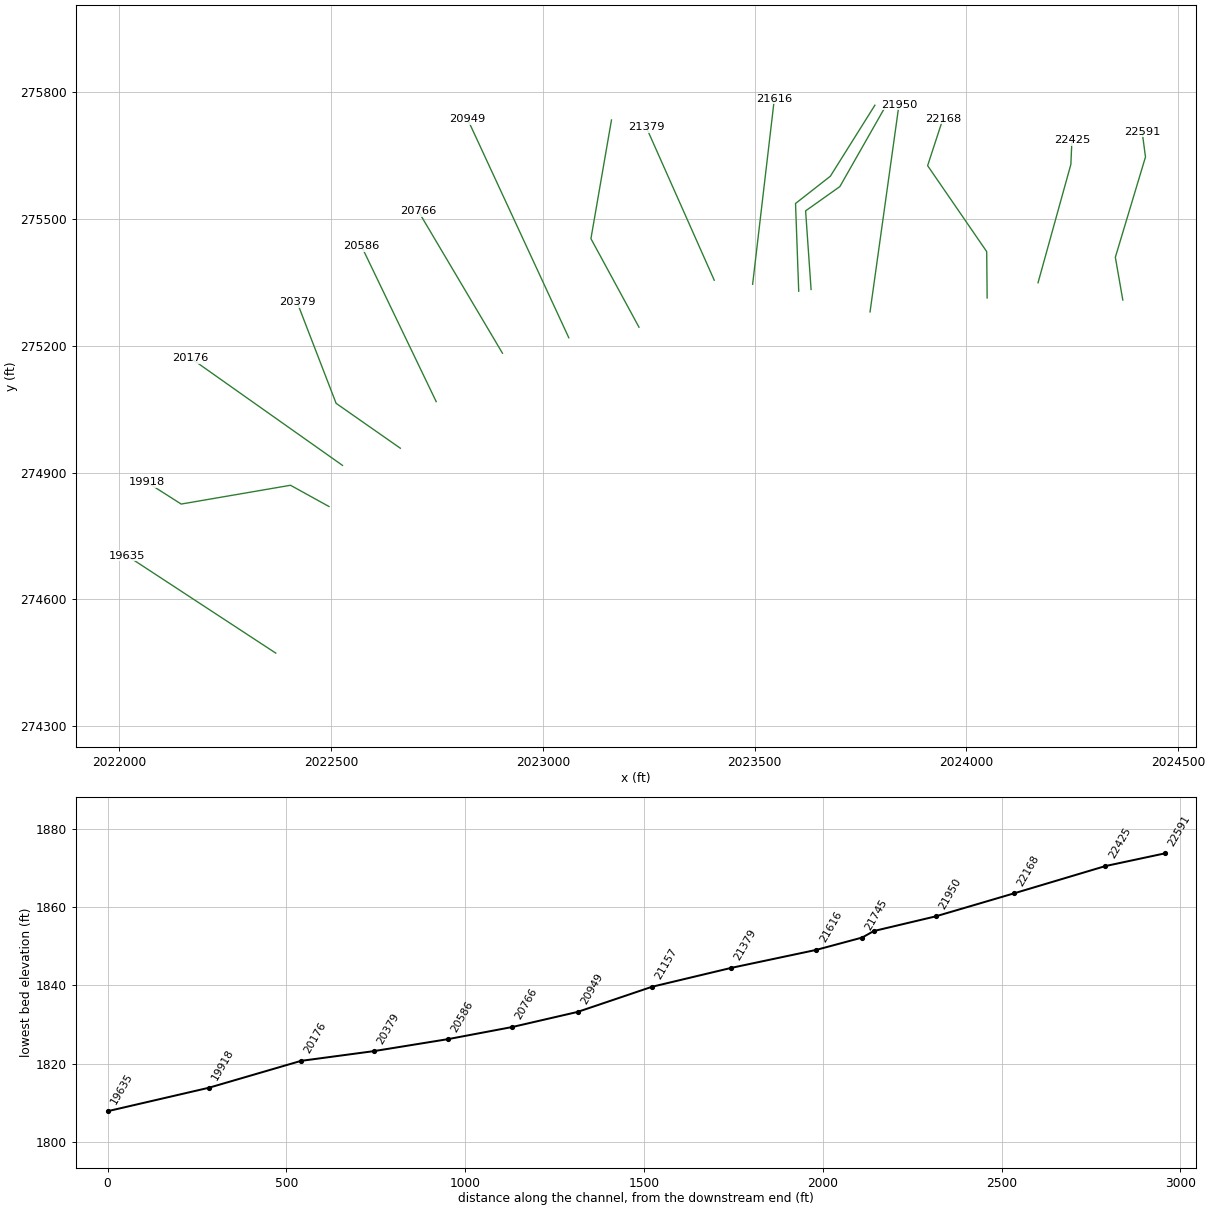
HEC-RAS study LAURELCK_A.prj: LAURELCK_A

--- LAURELCK_A.g01 (geometry) --- (continued)

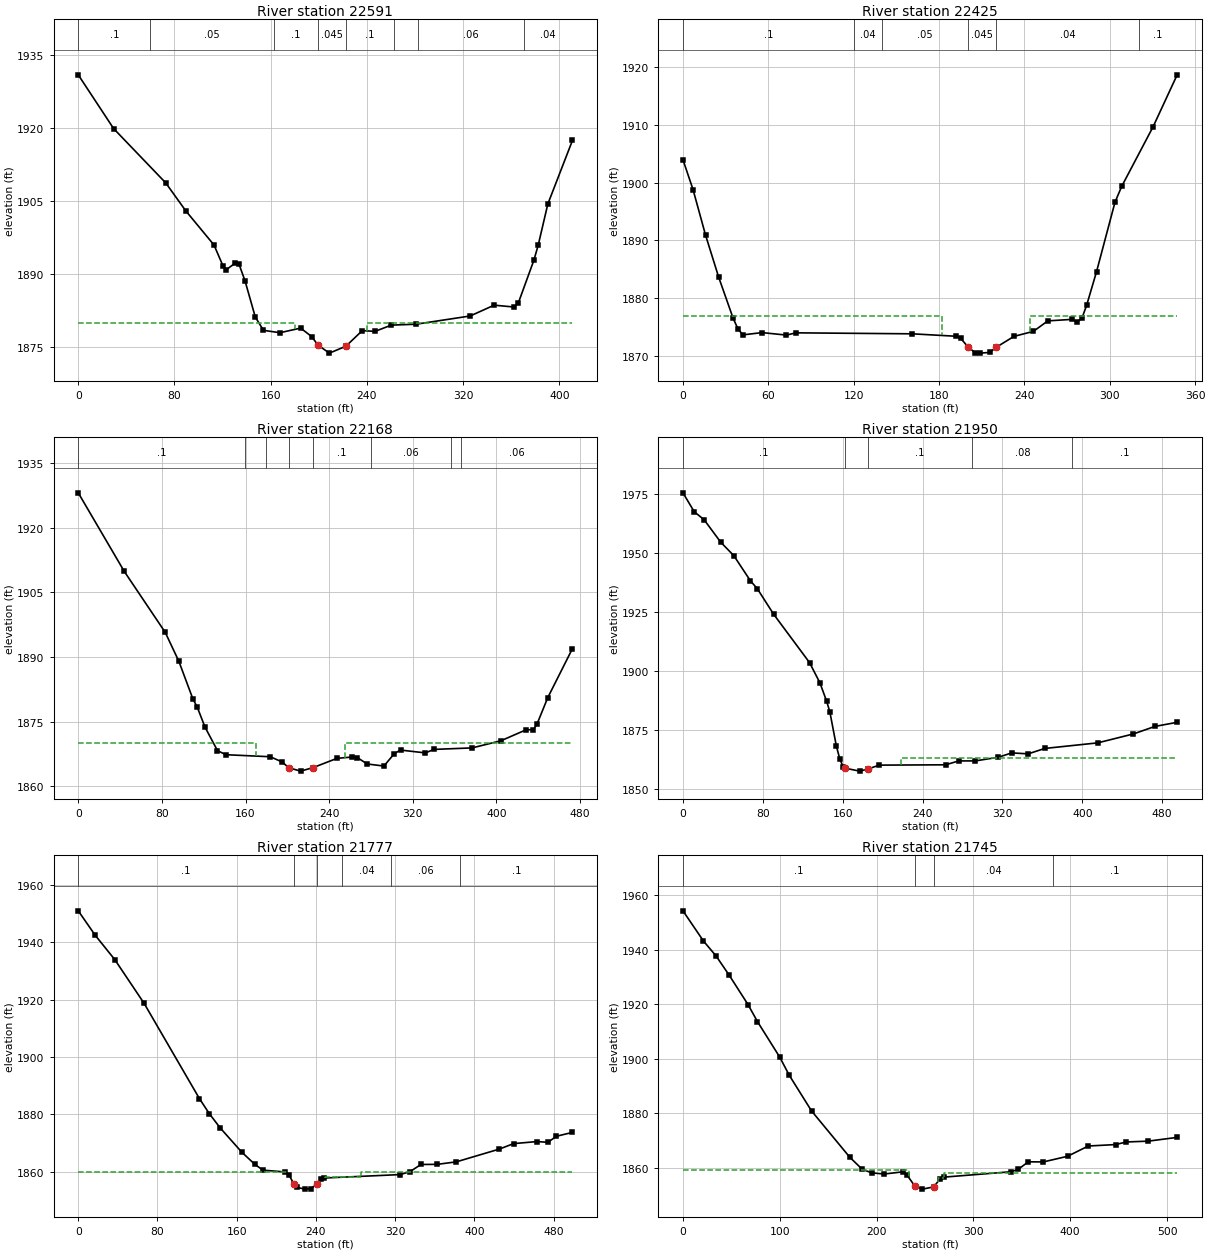
Type RM Length L Ch R = 1 ,22591   ,165.1,166.1,165.8
XS GIS Cut Line= 4
2024369.26724708275308.6434962192024351.64101144275409.834985496
2024422.81410573275647.3135278272024414.87964418275707.010662763
#Sta/Elev= 30
       0 1931.01    29.4 1919.95    72.7 1908.78    89.4 1903.02   112.9 1895.98
   120.3 1891.71   123.2 1890.92   130.1  1892.2   133.5 1892.16   138.7 1888.57
   147.2 1881.16     154 1878.43   167.7 1877.94   184.9 1878.89     194 1877.16
   199.3  1875.4   208.8 1873.74   222.5 1875.16   236.2 1878.38   246.7 1878.21
   260.2  1879.5   280.8 1879.69   325.8 1881.38   345.8 1883.61   362.6 1883.22
   365.9 1884.07   378.8 1892.85   382.4 1895.94   390.4 1904.42   410.9 1917.52
#Mann= 8 ,-1 , 0
       0      .1       0      60     .05       0  162.72      .1       0
   199.3    .045       0   222.5      .1       0  262.72     .04       0
  282.72     .06       0  370.63     .04       0
#XS Ineff= 2 , 0
             180    1880     240            1880
Permanent Ineff=
       F       F
Bank Sta=199.3,222.5
XS Rating Curve= 0 ,0
Exp/Cntr=0.3,0.1

Type RM Length L Ch R = 1 ,22425   ,236.6,256.5,273
XS GIS Cut Line= 3
2024169.13979284275349.5500853362024246.64308026 275629.69642528
2024249.08147488275686.372884372
#Sta/Elev= 30
       0 1903.96     7.1 1898.78    15.9  1890.9    25.1 1883.65    35.3 1876.51
    38.7 1874.68    42.1 1873.66    55.7 1874.05    72.7 1873.62    79.5 1874.01
   161.2 1873.84   191.9 1873.42   195.3 1873.04   200.5 1871.54   205.5 1870.56
   208.9  1870.5   215.7 1870.62   220.4 1871.54   232.7  1873.4   246.3 1874.26
   256.5 1876.08   273.6 1876.34     277 1875.88   280.4  1876.5   283.8 1878.81
   290.7 1884.57   303.7 1896.61   308.4 1899.34   330.5 1909.67   347.4 1918.64
#Mann= 6 ,-1 , 0
       0      .1       0     120     .04       0     140     .05       0
   200.5    .045       0   220.4     .04       0  320.67      .1       0
#XS Ineff= 2 , 0
             182    1877     244            1877
Permanent Ineff=
       F       F
Bank Sta=200.5,220.4
XS Rating Curve= 0 ,0
Exp/Cntr=0.3,0.1

Type RM Length L Ch R = 1 ,22168   ,234.2,217.9,202.7
XS GIS Cut Line= 4
2024048.97380523275313.4922849322024047.92216353275423.223983431
2023908.43401445275626.6275086052023944.52441844275737.339608393
#Sta/Elev= 30
       0 1928.09      44 1909.86    83.2 1895.71    96.3 1888.96   109.7 1880.23
   113.7 1878.43   121.3 1873.69   133.2 1868.26   141.2 1867.31   183.7 1866.84
   195.3  1865.6   201.2 1864.29   212.8  1863.5   224.7 1864.32   247.6 1866.47
   262.3 1866.78   267.1 1866.62   276.4 1865.16   292.4 1864.68   302.5 1867.59
   308.3 1868.39   332.1 1867.73   340.2 1868.54   376.8 1868.89   404.4 1870.55
   428.5  1873.1   435.4  1873.1   438.9 1874.44   449.2 1880.57   472.8 1891.95
#Mann= 8 ,-1 , 0
       0      .1       0  159.74     .04       0  179.74      .1       0
   201.2    .045       0   224.7      .1       0  279.74     .06       0
  356.37     .08       0  366.37     .06       0
#XS Ineff= 2 , 0
             170    1870     255            1870
Permanent Ineff=
       F       F
Bank Sta=201.2,224.7
XS Rating Curve= 0 ,0
Exp/Cntr=0.3,0.1

Type RM Length L Ch R = 1 ,21950   ,191.3,173.1,156.3
XS GIS Cut Line= 2
2023772.49120922275280.5119649052023840.82705241275770.769629479
#Sta/Elev= 30
       0 1975.55    11.3 1967.54    21.2 1964.15    37.8 1954.65      51 1948.91
    67.6 1938.26    74.4 1934.98    90.8 1924.14   126.8 1903.62   137.2 1895.04
   143.8 1887.39   147.1 1882.83   153.7 1868.16     157 1862.97   160.3 1859.61
   162.21858.923   176.9 1857.65   184.9 1858.48   196.5 1860.19     263 1860.33
   276.3 1861.97   292.8 1861.98     316 1863.54   329.3 1865.37   345.8 1864.97
   362.4 1867.26   415.4 1869.62   451.2 1873.41   472.7 1876.59     495 1878.33
#Mann= 5 ,-1 , 0
       0      .1       0   162.2    .045       0   184.9      .1       0
     290     .08       0     390      .1       0
#XS Ineff= 2 , 0
                             218            1863
Permanent Ineff=
       F       F
Bank Sta=162.2,184.9
XS Rating Curve= 0 ,0
Exp/Cntr=0.5,0.3

Type RM Length L Ch R = 1 ,21777   ,30.4,32.3,33.4
XS GIS Cut Line= 4
2023633.28598656275333.5857797022023620.38608893275519.666270368
2023701.31710416275577.1880105242023806.51149664275762.618515232
#Sta/Elev= 30
       0 1950.96    17.2  1942.4    36.9 1933.94    66.5 1918.69   122.4 1885.44
   132.3 1880.24   143.3 1875.25   165.2 1866.76   178.3 1862.54   186.5 1860.52
   208.9 1859.88   212.9 1858.74   217.7 1855.73     221 1854.48     229  1853.9
   234.7  1854.1   240.8 1855.54   245.5 1857.47   247.9 1857.77     325 1858.97
   334.8 1859.98   346.1  1862.5   362.5 1862.54   381.8 1863.42   425.3 1867.88
   439.5 1869.77     463 1870.48   474.3 1870.24   482.8 1872.34     499 1873.69
#Mann= 6 ,-1 , 0
       0      .1       0   217.7    .045       0   240.8      .1       0
  266.53     .04       0  315.82     .06       0  385.82      .1       0
#XS Ineff= 3 ,-1
       0   209.7    1860   248.8     285    1858     285  499.01    1860
Permanent Ineff=
       F       F       F
Bank Sta=217.7,240.8
XS Rating Curve= 0 ,0
Exp/Cntr(USF)=0,0
Exp/Cntr=0.5,0.3

Type RM Length L Ch R = 1 ,21745   ,110.9,128.3,149.4
XS GIS Cut Line= 4
 2023604.1079008275329.5570144792023596.59687736275537.148096805
2023678.80146836275601.6761719662023783.93632855275769.734687982
#Sta/Elev= 30
       0 1954.33    21.2 1943.25    34.3 1937.73    47.5 1930.86    67.2 1919.95
      77 1913.67     100 1900.65   109.8 1894.01   132.8 1880.94   172.2 1863.99
   185.3 1859.47   195.2 1858.21   207.7 1857.78   227.8 1858.61   231.1 1857.57
   239.2 1853.51   247.4 1852.24   259.1 1853.07   265.3 1855.88   269.5 1856.64
     339 1858.62   346.2 1859.49   356.8 1862.26   372.3 1862.22   397.3 1864.29
   418.7 1868.06   446.8 1868.58   458.1 1869.54   480.6 1869.84   510.5 1871.22
#Mann= 4 ,-1 , 0
       0      .1       0   239.2    .045       0   259.1     .04       0
  382.23      .1       0
#XS Ineff= 3 ,-1
       0   233.9  1859.2     263     270  1856.5     270  510.47    1858
Permanent Ineff=
       F       F       F
Bank Sta=239.2,259.1
XS Rating Curve= 0 ,0
Exp/Cntr(USF)=0,0
Exp/Cntr=0.5,0.3

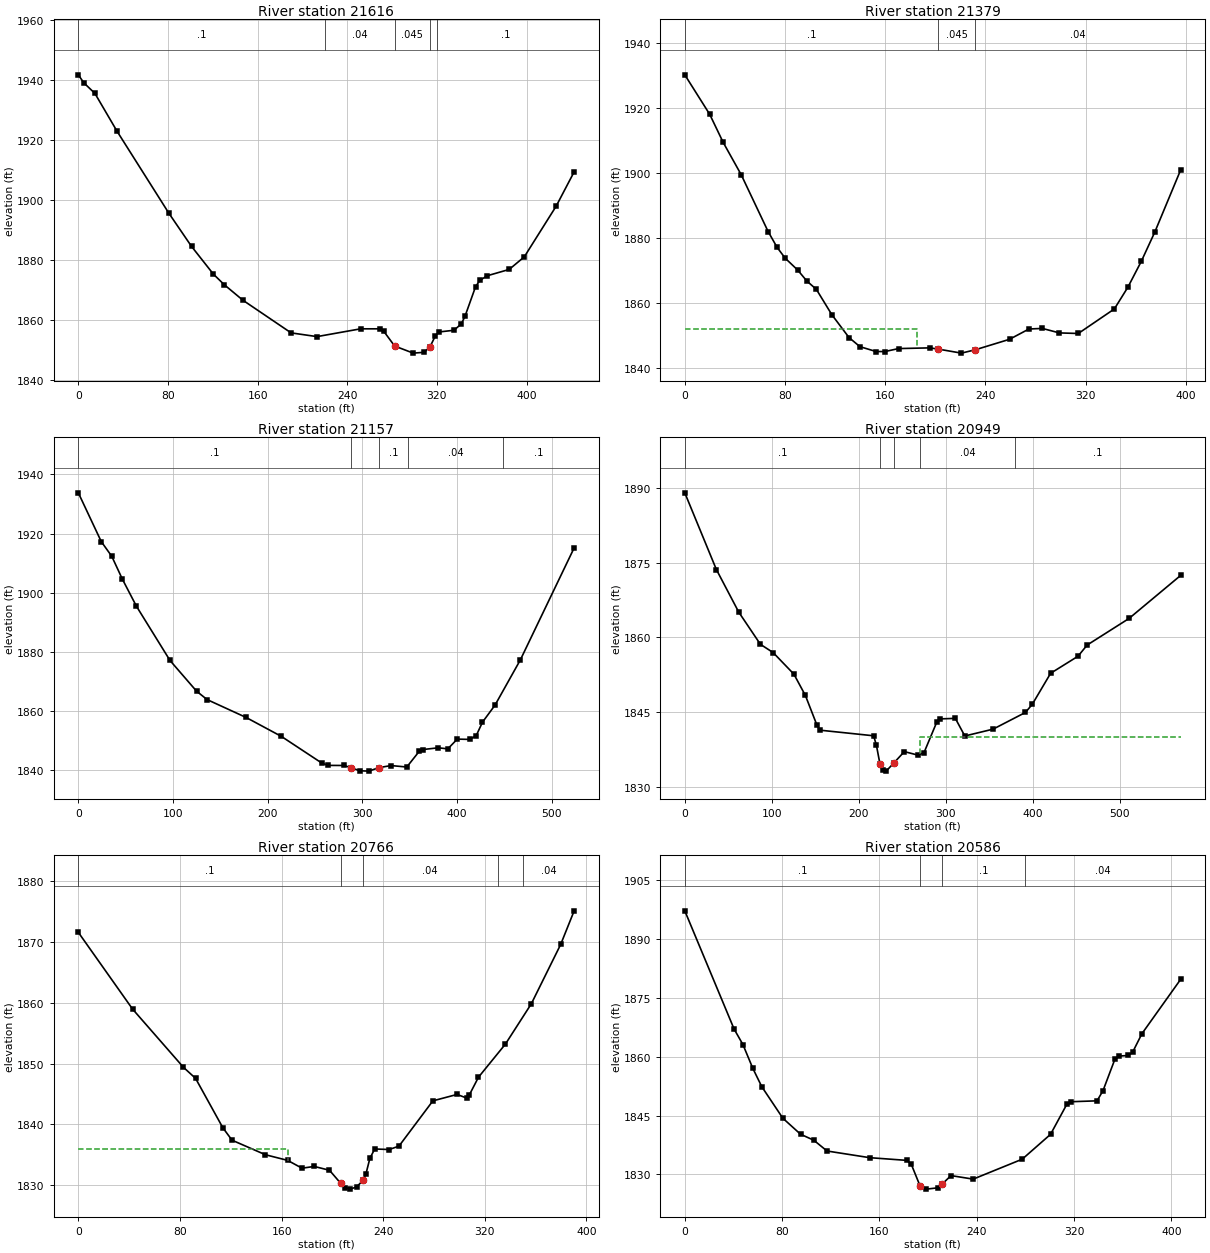
Type RM Length L Ch R = 1 ,21616   ,224.8,237.8,252.5
XS GIS Cut Line= 2
2023495.28726343275345.8979813312023546.65873446275785.409455669
#Sta/Elev= 30
       0 1941.61     4.9 1938.95    14.8 1935.43    34.6 1922.82    80.8  1895.6
     101 1884.58   120.5 1875.36   130.1 1871.88   146.9 1866.67   189.9 1855.82
     213 1854.58   251.9 1857.17   269.1 1857.17   272.6 1856.34   282.3 1851.45
   298.9 1849.09   308.8 1849.37     314 1851.29   318.7 1854.89     322 1856.13
   335.2 1856.69   341.8  1858.8   345.1 1861.36   354.5 1871.16   358.3 1873.26
   364.9 1874.81   384.5 1876.91     398  1881.1   426.4 1897.92   442.5 1909.36
#Mann= 5 ,-1 , 0
       0      .1       0     220     .04       0   282.3    .045       0
     314     .04       0     320      .1       0
Bank Sta=282.3,314
XS Rating Curve= 0 ,0
Exp/Cntr(USF)=0,0
Exp/Cntr=0.3,0.1

Type RM Length L Ch R = 1 ,21379   ,234.4,221.7,208.6
XS GIS Cut Line= 2
 2023404.6483583275355.5321439782023244.26311578275717.388083475
#Sta/Elev= 30
       0  1930.1    19.9 1917.94    30.6 1909.34      45 1899.39    66.5  1881.9
    73.7 1877.01    80.1 1873.71    90.1 1870.05    97.5 1866.64     105 1864.12
   117.4  1856.3   131.1 1849.28   139.8 1846.48   152.7 1844.98   159.7 1844.97
   170.6 1845.89   195.7 1846.11     202 1845.75   220.8 1844.49   231.8 1845.51
   259.2 1848.74   274.7 1851.91   285.4 1852.09     299 1850.71   314.1 1850.53
   342.9 1858.08   353.7 1864.77   364.4 1872.72   375.2 1881.74   395.8 1900.82
#Mann= 3 ,-1 , 0
       0      .1       0     202    .045       0   231.8     .04       0
#XS Ineff= 2 , 0
             185    1852
Permanent Ineff=
       F       F
Bank Sta=202,231.8
XS Rating Curve= 0 ,0
Exp/Cntr=0.3,0.1

Type RM Length L Ch R = 1 ,21157   ,192.1,208.2,220.9
XS GIS Cut Line= 3
 2023227.0310467275244.2502770512023113.53570409275453.813458016
2023162.05449214275734.798878764
#Sta/Elev= 30
       0 1933.79    24.2  1917.3    35.3 1912.32    46.5 1904.59    61.4  1895.4
    96.8 1877.08   124.8 1866.71     136 1863.85   177.1 1857.82   214.4  1851.4
   256.9 1842.42   263.6  1841.6   280.2 1841.57   288.4 1840.81   296.9 1839.78
   306.9 1839.66     317 1840.82   330.2 1841.54   346.8 1841.05   360.1 1846.43
   363.5 1846.95   380.1 1847.55   390.1 1847.19   400.1 1850.49   413.4 1850.39
   420.1 1851.67   426.7 1856.22     440 1862.01   466.7 1877.29   523.5 1915.18
#Mann= 5 ,-1 , 0
       0      .1       0   288.4    .045       0     317      .1       0
  348.32     .04       0  448.32      .1       0
Bank Sta=288.4,317
XS Rating Curve= 0 ,0
Exp/Cntr=0.3,0.1

Type RM Length L Ch R = 1 ,20949   ,180.1,182.9,184.1
XS GIS Cut Line= 2
2023061.26009869275219.3701549852022822.35394178275736.685293598
#Sta/Elev= 30
       0 1888.98    36.3 1873.61      62 1865.08    86.9 1858.63   101.5 1856.98
   125.4 1852.65   138.6 1848.38   151.9 1842.42   155.5 1841.43     217 1840.31
   220.2 1838.41   224.2 1834.74   227.8 1833.48   231.4 1833.23     240 1834.82
   252.3 1837.14   267.6 1836.45   274.8 1836.89   289.4 1842.98   292.9 1843.69
   310.9  1843.8   321.8 1840.27   354.3 1841.64   391.4 1844.98   399.3 1846.61
   420.4 1852.83   451.9 1856.25   462.4 1858.49   510.5 1863.81   569.8 1872.43
#Mann= 5 ,-1 , 0
       0      .1       0   224.2    .045       0     240      .1       0
     270     .04       0     380      .1       0
#XS Ineff= 2 , 0
                             270            1840
Permanent Ineff=
       F       F
Bank Sta=224.2,240
XS Rating Curve= 0 ,0
Exp/Cntr=0.3,0.1

Type RM Length L Ch R = 1 ,20766   ,181.1,180,177.7
XS GIS Cut Line= 2
2022904.68639119275182.706668138 2022706.0966285275518.713704194
#Sta/Elev= 30
       0 1871.57    42.7 1858.96    82.7  1849.4    92.3 1847.57   113.8 1839.44
     121 1837.41   147.3 1835.02   164.7  1834.1   176.1 1832.81   185.7  1833.1
   197.7 1832.47   206.6 1830.31   209.6 1829.61   214.2 1829.37   219.2 1829.76
     224  1830.8   226.4 1831.88   229.5 1834.43   233.3 1835.97   244.7 1835.88
   252.4 1836.44   279.1 1843.88   298.1 1844.93   305.7 1844.34   307.8 1844.86
     315 1847.77   336.2 1853.21   356.6 1859.84   379.7 1869.59   390.3 1875.11
#Mann= 5 ,-1 , 0
       0      .1       0   206.6    .045       0     224     .04       0
     330      .1       0     350     .04       0
#XS Ineff= 2 , 0
             165    1836
Permanent Ineff=
       F       F
Bank Sta=206.6,224
XS Rating Curve= 0 ,0
Exp/Cntr=0.3,0.1

Type RM Length L Ch R = 1 ,20586   ,208.8,207.2,206.3
XS GIS Cut Line= 2
2022748.21406529275068.128635746 2022572.0410559275435.576280605
#Sta/Elev= 30
       0 1897.22    40.5 1867.09    47.8 1863.11    55.9 1857.06    63.3 1852.37
    80.6 1844.34    95.1 1840.27     106 1838.74   116.9 1835.99   151.9 1834.29
   182.4  1833.6   186.1 1832.64   193.3 1827.12   198.6 1826.27   207.9  1826.6
   211.5 1827.56   218.8 1829.72     237 1828.82   277.3  1833.9   300.6 1840.24
   314.2 1848.03   317.1 1848.55   338.8 1848.78   343.7 1851.36   353.5 1859.41
   357.1 1860.19   364.4 1860.34     368 1861.15   375.7  1865.9   407.5 1879.74
#Mann= 4 ,-1 , 0
       0      .1       0   193.3    .045       0   211.5      .1       0
     280     .04       0
Bank Sta=193.3,211.5
XS Rating Curve= 0 ,0
Exp/Cntr=0.3,0.1

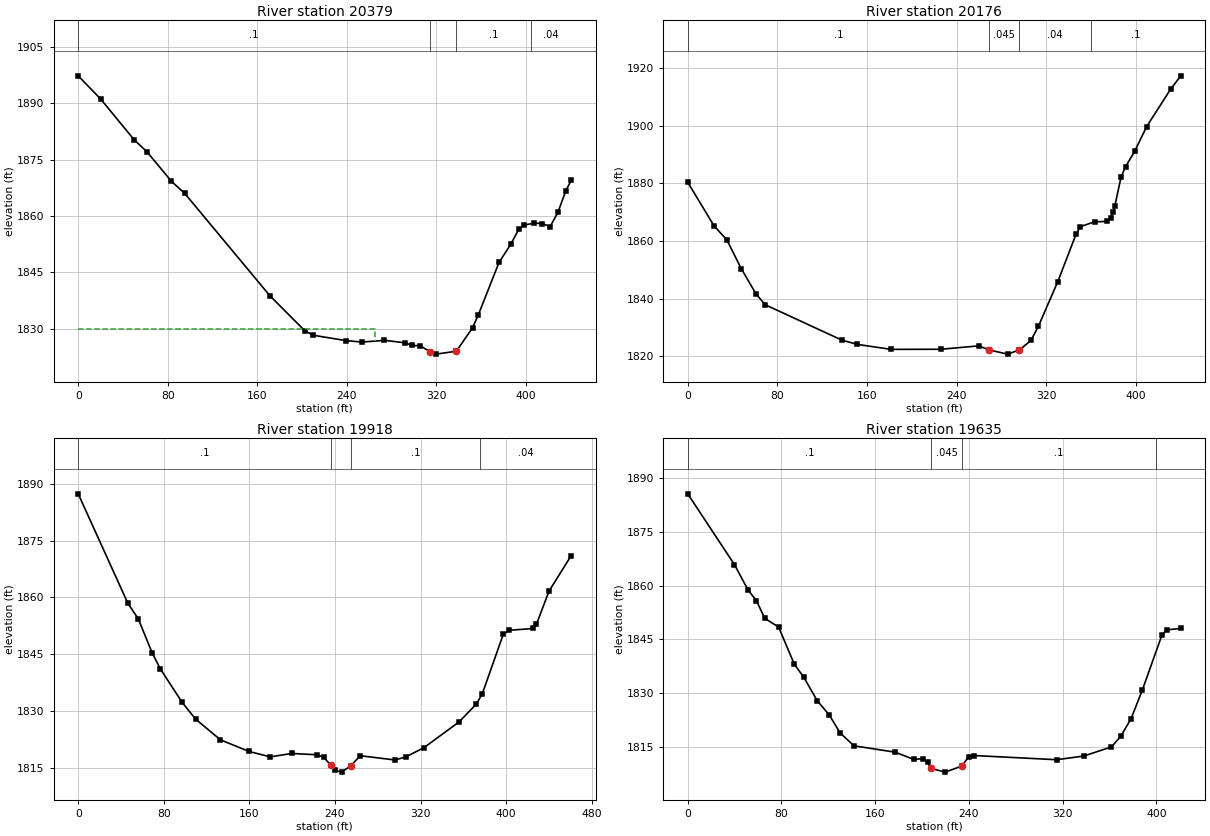
Type RM Length L Ch R = 1 ,20379   ,189.5,203,216.2
XS GIS Cut Line= 3
 2022663.5251216274957.8216073172022511.93411208  275064.0336824
  2022420.076841275302.798533054
#Sta/Elev= 30
       0  1897.3    20.2 1891.09    50.1 1880.25    61.5 1877.08    83.3 1869.24
    95.3 1865.98   171.4 1838.76   202.8 1829.38   210.4 1828.23   239.2 1826.82
   253.6 1826.42   273.9 1826.88   291.9 1826.24   298.9 1825.52     306 1825.43
   314.5 1823.83     320 1823.21   338.2 1823.99   352.6 1830.21   357.7 1833.58
   376.3 1847.62   386.8 1852.45   393.9  1856.4   398.3 1857.55   407.9 1858.07
     415 1857.98     422 1857.15     429 1860.97     436 1866.67   440.9 1869.52
#Mann= 4 ,-1 , 0
       0      .1       0   314.5    .045       0   338.2      .1       0
   405.1     .04       0
#XS Ineff= 2 , 0
             265    1830
Permanent Ineff=
       F       F
Bank Sta=314.5,338.2
XS Rating Curve= 0 ,0
Exp/Cntr=0.3,0.1

Type RM Length L Ch R = 1 ,20176   ,237.8,258.1,272.9
XS GIS Cut Line= 2
2022526.99892546274917.1877381662022167.93068199275171.523850654
#Sta/Elev= 30
       0 1880.37    23.5 1865.23    34.9 1860.39    47.8 1850.38      61 1841.59
    69.1 1837.87   137.4 1825.62   151.4  1824.1   181.6 1822.38   225.9 1822.42
   259.7 1823.59   269.1 1822.17   285.5 1820.73     296 1822.19   306.3 1825.46
     313 1830.44   330.3 1845.91   346.7 1862.48   350.5 1864.98   363.2 1866.64
   374.6 1866.77   377.3 1867.86   379.7 1869.89   381.1 1872.01   386.7 1882.12
   390.7 1885.75   398.8 1891.04   409.5 1899.63   430.9 1912.62     440 1917.28
#Mann= 4 ,-1 , 0
       0      .1       0   269.1    .045       0     296     .04       0
     360      .1       0
Bank Sta=269.1,296
XS Rating Curve= 0 ,0
Exp/Cntr=0.3,0.1

Type RM Length L Ch R = 1 ,19918   ,298.7,283,267.8
XS GIS Cut Line= 4
2022495.11519796274819.8359725922022404.25058125274870.101505235
2022146.15640403274825.6358417432022065.92488077274876.868019245
#Sta/Elev= 30
       0 1887.35    46.5 1858.41    56.2 1854.31    69.2 1845.31    76.7 1841.16
    97.2 1832.26   109.7 1827.86     133 1822.38   159.7 1819.31   179.6 1817.88
   199.6 1818.78   222.9 1818.44   229.6 1817.78   236.2 1815.63   239.6 1814.35
   246.2 1813.85   255.1 1815.58   263.6 1818.18   296.2 1817.06   306.1 1817.86
   323.3 1820.33   356.1 1827.12   372.2 1831.84   377.8 1834.57   397.3 1850.21
   402.6  1851.3   425.5 1851.79   428.4 1852.91   440.1 1861.64   460.9 1871.06
#Mann= 4 ,-1 , 0
       0      .1       0   236.2    .045       0   255.1      .1       0
  375.74     .04       0
Bank Sta=236.2,255.1
XS Rating Curve= 0 ,0
Exp/Cntr(USF)=0,0
Exp/Cntr=0.3,0.1

Type RM Length L Ch R = 1 ,19635   ,289.3,279.7,266.8
XS GIS Cut Line= 2
2022369.45136635274472.8104683772022017.59263784274703.838589567
#Sta/Elev= 30
       0 1885.69    39.9  1865.9    51.5  1858.8    58.6 1855.84    65.8 1850.86
    77.6 1848.43    90.9 1838.11    99.2 1834.33   110.5 1827.87   120.8 1823.84
   130.1 1818.84   141.9 1815.22   177.1 1813.44   192.9 1811.43   200.8 1811.63
   204.7  1810.7   207.9 1808.89   219.8 1807.86     234 1809.56     240 1812.21
     244 1812.51   315.1 1811.33   338.2 1812.37   361.7 1814.91   369.6 1817.84
   378.5 1822.82     388 1830.73   404.9 1846.26   408.8 1847.66   420.9 1848.03
#Mann= 4 ,-1 , 0
       0      .1       0   207.9    .045       0     234      .1       0
     400     .04       0
Bank Sta=207.9,234
XS Rating Curve= 0 ,0
Exp/Cntr(USF)=0,0
Exp/Cntr=0.3,0.1