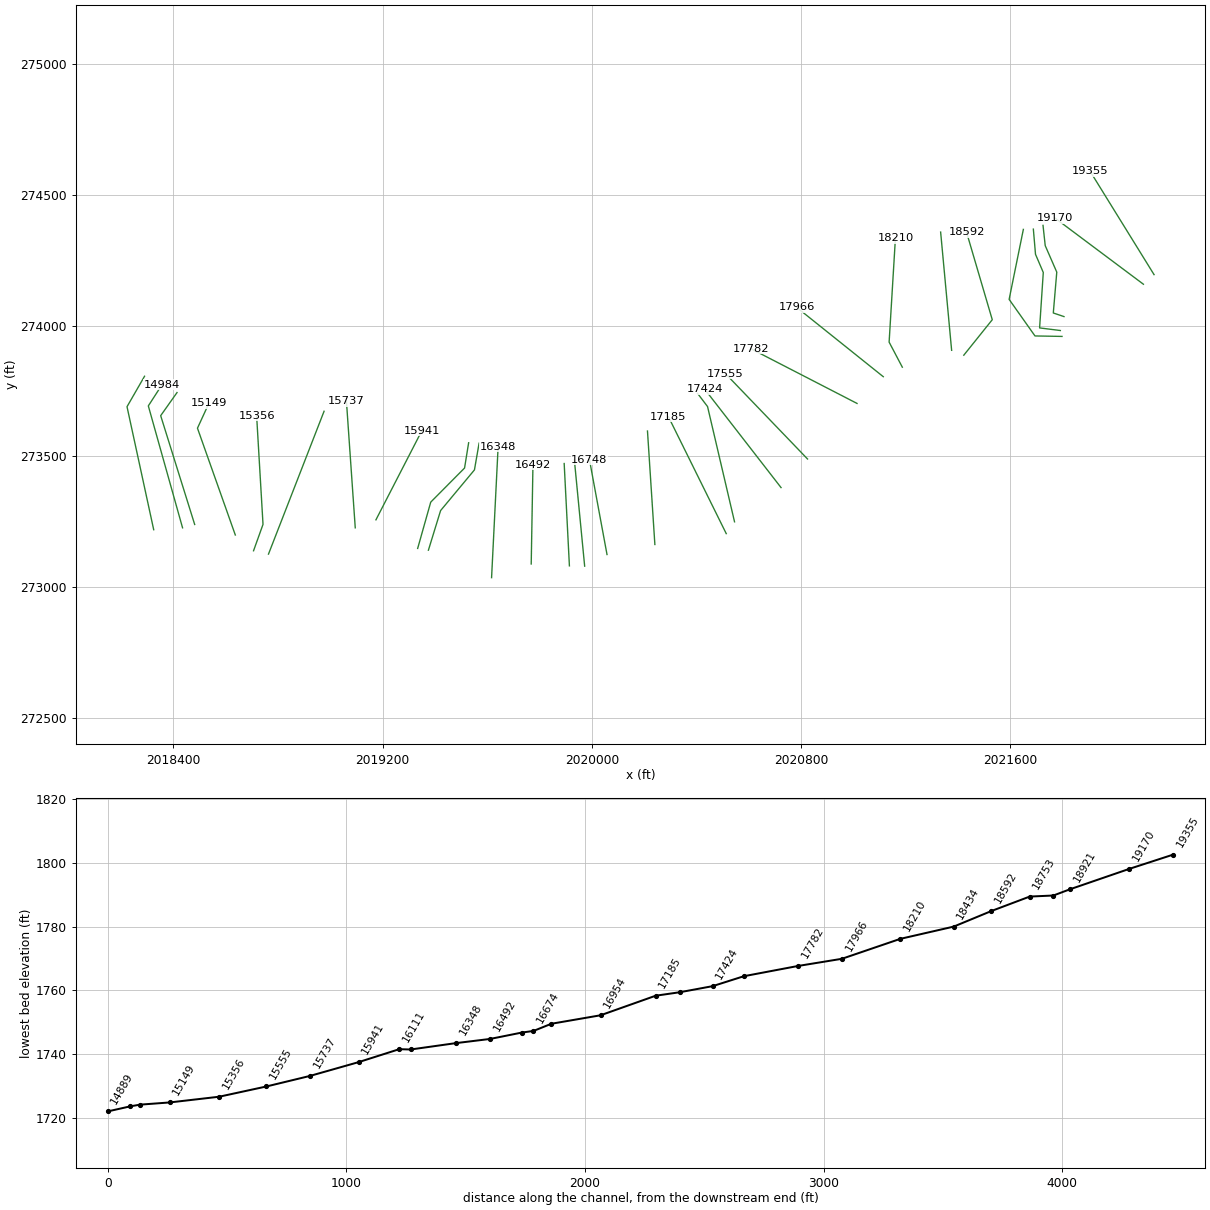
HEC-RAS study LAURELCK_A.prj: LAURELCK_A

--- LAURELCK_A.g01 (geometry) --- (continued)

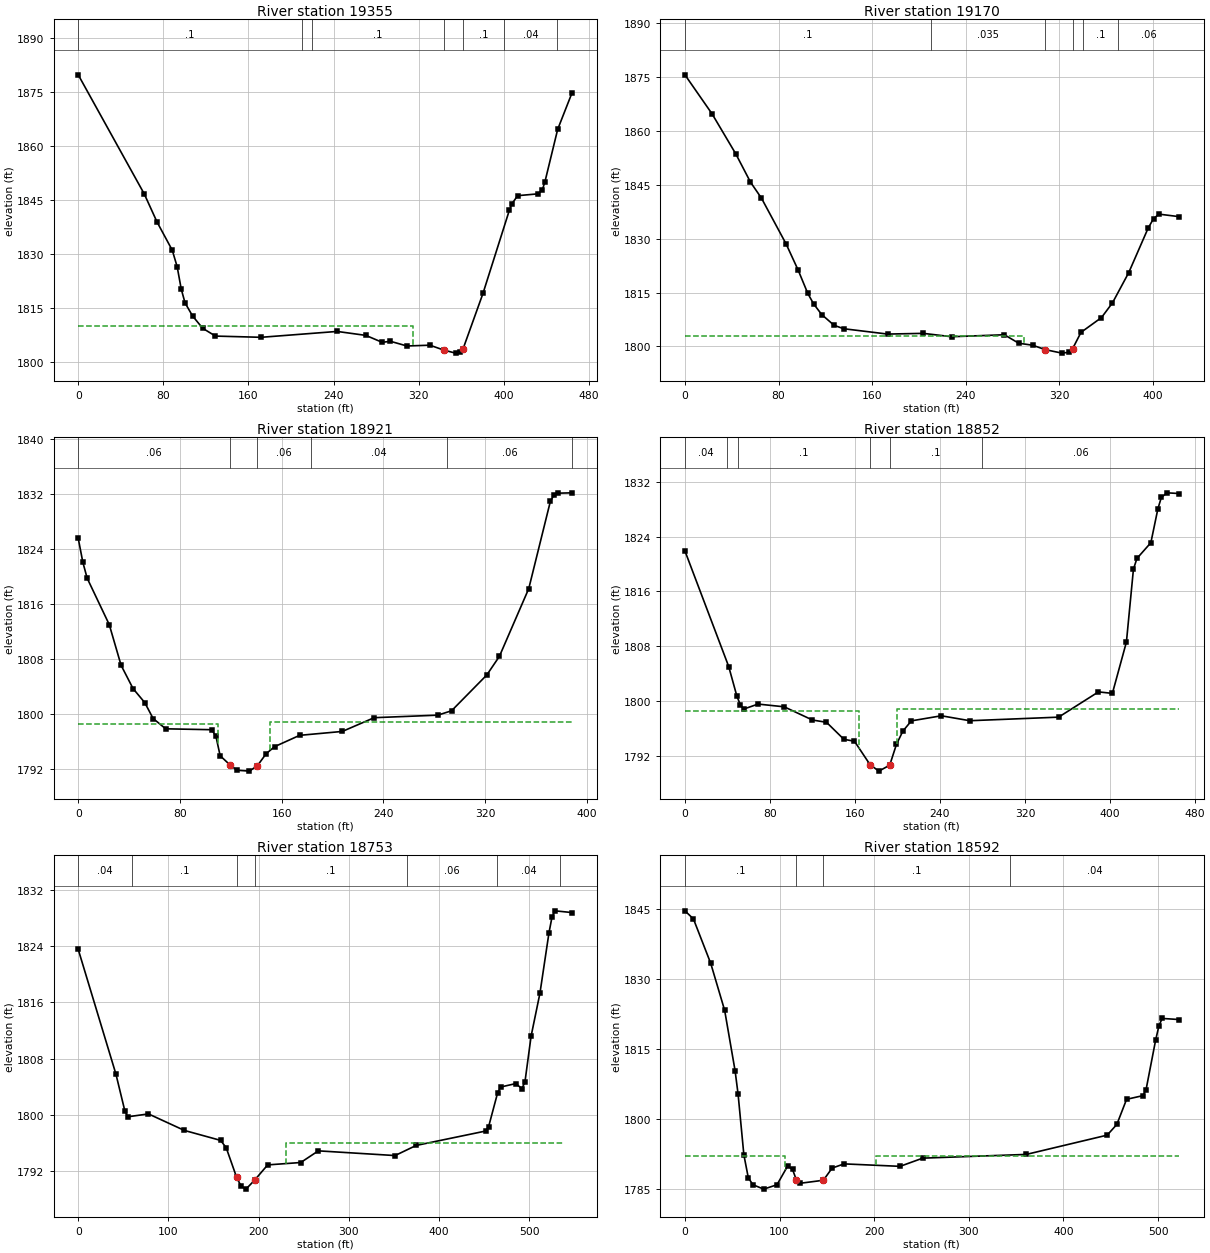
Type RM Length L Ch R = 1 ,19355   ,179.1,184.7,192.9
XS GIS Cut Line= 2
 2022149.1201275274195.5569357292021904.91917916274590.483182272
#Sta/Elev= 30
       0 1879.82    62.1 1846.75    74.1 1838.97    88.4 1831.15      93 1826.58
    96.8 1820.41   100.4 1816.54   107.5 1812.91     117 1809.49     129 1807.33
   171.9 1806.99   243.4 1808.62   270.4 1807.52   285.8 1805.59   293.4 1805.89
     309 1804.58   330.6  1804.8   343.7 1803.44   354.7  1802.6   359.1 1802.82
   361.8 1803.81   380.5 1819.18   405.4 1842.35   407.8 1844.08   413.1 1846.29
   432.4  1846.8   436.3 1847.89   438.8 1850.22   450.7 1864.68   464.3  1874.9
#Mann= 7 ,-1 , 0
       0      .1       0     210    .035       0     220      .1       0
   343.7    .045       0   361.8      .1       0     400     .04       0
     450      .1       0
#XS Ineff= 2 , 0
             315    1810
Permanent Ineff=
       F       F
Bank Sta=343.7,361.8
XS Rating Curve= 0 ,0
Exp/Cntr(USF)=0,0
Exp/Cntr=0.3,0.1

Type RM Length L Ch R = 1 ,19170   ,271.1,248.7,232.1
XS GIS Cut Line= 2
2022108.46850168274158.8785883942021770.57365469274411.785684827
#Sta/Elev= 30
       0 1875.68    23.2  1864.8    43.5 1853.63      56 1845.79    65.4 1841.31
    86.5 1828.53    96.8 1821.23     105 1814.76   109.9 1811.88   116.9 1808.86
   127.5 1805.86   135.7 1804.91   173.2 1803.42   203.7 1803.62   227.9 1802.68
     273 1803.23   285.3 1800.87   297.2 1800.31   308.1 1799.07   322.2 1798.11
   327.9 1798.34   331.3 1799.32   338.5  1803.9     356 1808.02   365.4 1812.12
   379.3 1820.55   395.8 1832.89   400.5  1835.6   405.2 1836.85   422.1 1836.16
#Mann= 6 ,-1 , 0
       0      .1       0     210    .035       0   308.1    .045       0
   331.3    .035       0     340      .1       0     370     .06       0
#XS Ineff= 2 , 0
             290    1803
Permanent Ineff=
       F       F
Bank Sta=308.1,331.3
XS Rating Curve= 0 ,0
Exp/Cntr(USF)=0,0
Exp/Cntr=0.5,0.3

Type RM Length L Ch R = 1 ,18921   ,67.7,69.8,66.9
XS GIS Cut Line= 5
2021804.74579818274035.1663316062021763.88529055274048.914370898
2021777.15113771 274205.232926012021732.99150457274306.542259477
 2021724.5787474274383.977465295
#Sta/Elev= 30
       0  1825.6     3.6 1822.14       7 1819.81    24.4 1813.04    33.7 1807.12
    43.1 1803.73    52.3 1801.69    58.9 1799.37    68.8 1797.87     105 1797.74
   108.3 1796.77   111.6 1793.95   119.6 1792.57   124.8 1791.84   134.6 1791.71
   140.9  1792.5   147.8 1794.25   154.4 1795.27   174.1 1796.92   207.7 1797.49
   232.7 1799.49   282.8 1799.86   293.6  1800.5   321.3 1805.71   331.2 1808.42
   354.3 1818.29   371.3    1831   374.1  1831.9   377.3 1832.18   388.4 1832.23
#Mann= 6 ,-1 , 0
       0     .06       0   119.6    .045       0   140.9     .06       0
  183.11     .04       0  289.99     .06       0   388.4     .04       0
#XS Ineff= 2 , 0
           109.6  1798.5   150.9          1798.8
Permanent Ineff=
       F       F
Bank Sta=119.6,140.9
XS Rating Curve= 0 ,0
Exp/Cntr(USF)=0,0
Exp/Cntr=0.5,0.3

Type RM Length L Ch R = 1 ,18852   ,82.9,99,113.8
XS GIS Cut Line= 5
2021790.82061206273981.8871777982021711.50124221273991.837400389
2021725.59147377274203.896484722 2021695.8388476274273.396261587
2021687.64154877274369.681379686
#Sta/Elev= 30
       0  1821.9    41.2 1805.02    48.9 1800.69    52.2 1799.41    55.5 1798.82
    68.8 1799.54    93.4 1799.14     120 1797.21   133.2 1796.88   149.6 1794.39
   159.5 1794.12   174.2 1790.69   182.5 1789.75   192.7 1790.62     199 1793.65
   205.1  1795.6   213.1 1797.09   241.3 1797.83     268 1797.11   351.6 1797.63
   389.1 1801.32   402.2  1801.1   415.4  1808.6     422 1819.23   425.3  1820.8
   438.4  1823.1     445 1828.04   448.3 1829.73   453.7 1830.38   464.7 1830.28
#Mann= 6 ,-1 , 0
       0     .04       0      40     .06       0      50      .1       0
   174.2    .045       0   192.7      .1       0  279.94     .06       0
#XS Ineff= 2 , 0
           164.1  1798.5   199.4          1798.8
Permanent Ineff=
       F       F
Bank Sta=174.2,192.7
XS Rating Curve= 0 ,0
Exp/Cntr(USF)=0,0
Exp/Cntr=0.5,0.3

Type RM Length L Ch R = 1 ,18753   ,192.5,160.9,132.6
XS GIS Cut Line= 4
2021797.20051003273959.2770426882021693.83158493273961.117814018
 2021595.0013945274100.977071815 2021649.3896781274368.678704351
#Sta/Elev= 30
       0 1823.55    41.8  1805.8    51.6 1800.61    54.9 1799.72    77.9 1800.13
   117.7 1797.78   157.9 1796.36   164.1 1795.32   175.61791.123   180.6 1789.84
     186 1789.42   195.61790.693   210.1 1792.87   246.8 1793.21   266.3 1794.87
   351.4  1794.2   374.8 1795.64   451.8 1797.69   455.2 1798.33   465.2 1803.15
   468.6 1803.96   485.3 1804.45     492 1803.74   495.4 1804.62   502.3 1811.21
   512.1 1817.32   522.1 1825.91   525.5 1828.18   528.8 1829.05   547.8  1828.8
#Mann= 7 ,-1 , 0
       0     .04       0      60      .1       0   175.6    .045       0
   195.6      .1       0  364.64     .06       0  464.64     .04       0
  534.64     .06       0
#XS Ineff= 1 ,-1
     230   537.8    1796
Permanent Ineff=
       F
Bank Sta=175.6,195.6
XS Rating Curve= 0 ,0
Exp/Cntr(USF)=0,0
Exp/Cntr=0.3,0.1

Type RM Length L Ch R = 1 ,18592   ,134.1,157.7,172.2
XS GIS Cut Line= 3
2021421.70786992273887.5203465752021530.53973408274023.182543456
 2021432.4192868274357.093841403
#Sta/Elev= 30
       0 1844.62       9 1842.88    27.3 1833.33      42 1823.25      53 1810.32
    56.2 1805.25    62.3 1792.24      67 1787.31    71.9 1785.82    83.3 1784.88
    97.3 1785.82   108.6 1789.85   113.7 1789.13   117.7  1786.9   121.9 1786.14
   146.3 1786.78   155.6  1789.4   168.2  1790.3   227.4 1789.77   251.3 1791.53
   360.8 1792.33   446.3 1796.47   456.5 1798.77   466.8 1804.16   483.9 1804.94
   487.3 1806.15   497.5 1816.87     501 1819.95   504.4 1821.52     522 1821.29
#Mann= 4 ,-1 , 0
       0      .1       0   117.7    .045       0   146.3      .1       0
  343.92     .04       0
#XS Ineff= 2 , 0
          106.27    1792   201.8         1791.97
Permanent Ineff=
       F       F
Bank Sta=117.7,146.3
XS Rating Curve= 0 ,0
Exp/Cntr(USF)=0,0
Exp/Cntr=0.3,0.1

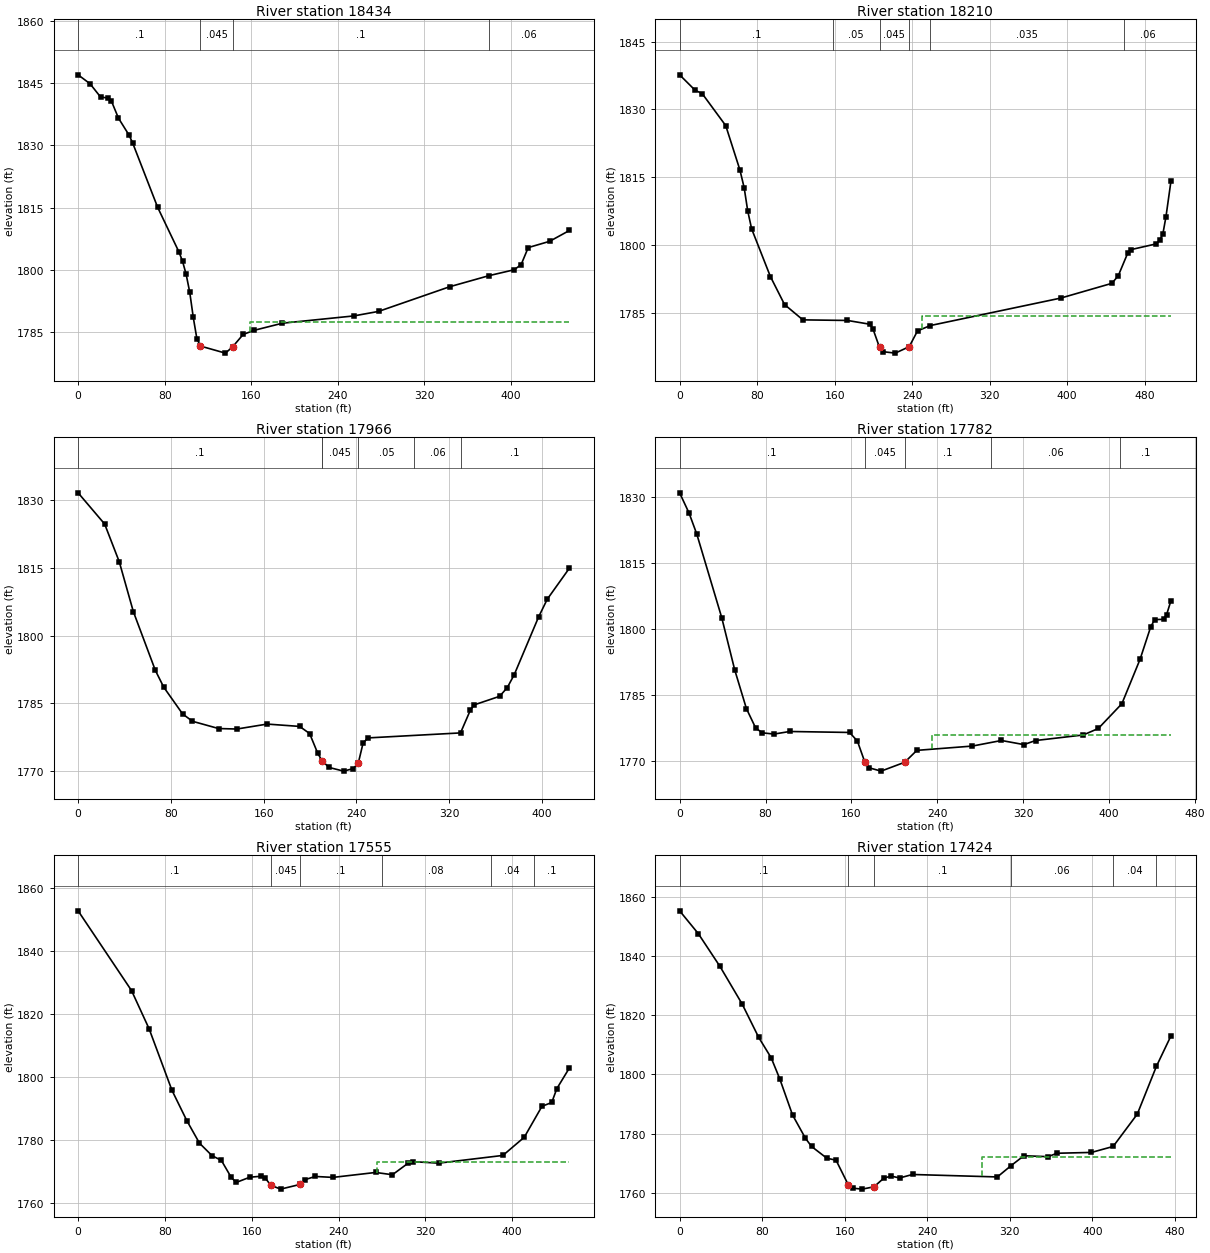
Type RM Length L Ch R = 1 ,18434   ,227.3,223.7,219.7
XS GIS Cut Line= 2
2021375.17812102273906.1103895062021333.14589584274358.440150179
#Sta/Elev= 30
       0 1846.98      11 1844.84    20.8 1841.63    27.4 1841.41    30.7 1840.73
    37.3 1836.56    47.2 1832.43    50.5 1830.54    73.6 1815.06    93.3 1804.32
    96.6 1802.08    99.9 1798.95   103.2 1794.69   106.5 1788.58   109.8  1783.5
   113.1  1781.7   136.2    1780   142.8 1781.49   152.6 1784.49   162.5 1785.47
   188.9  1787.2   254.8 1788.95   277.8 1790.04   343.7 1795.99     380 1798.65
   403.1 1800.06   409.6 1801.28   416.2  1805.4     436 1806.91   454.3 1809.52
#Mann= 4 ,-1 , 0
       0      .1       0   113.1    .045       0   142.8      .1       0
     380     .06       0
#XS Ineff= 2 , 0
                             159          1787.5
Permanent Ineff=
       F       F
Bank Sta=113.1,142.8
XS Rating Curve= 0 ,0
Exp/Cntr(USF)=0,0
Exp/Cntr=0.3,0.1

Type RM Length L Ch R = 1 ,18210   ,220.4,244.6,268.8
XS GIS Cut Line= 3
2021186.60842406273841.6832250022021136.16915871273937.492952214
2021160.26894165274335.495114419
#Sta/Elev= 30
       0 1837.66      16 1834.25    23.3 1833.51    47.6 1826.43    62.2 1816.65
    66.6 1812.72    70.3 1807.56    74.3 1803.63    93.7 1793.07   108.3 1786.89
   127.2 1783.51   173.2 1783.38   196.2 1782.55   199.5 1781.52   206.3 1777.41
   209.4 1776.49   222.5 1776.16   236.9 1777.58   245.5 1781.07   258.6 1782.25
   393.4 1788.33     446 1791.58   452.6 1793.24   462.5 1798.31   465.7 1799.03
     492 1800.31   495.3  1801.1   498.6 1802.41   501.9 1806.35     507 1814.14
#Mann= 6 ,-1 , 0
       0      .1       0  158.28     .05       0   206.3    .045       0
   236.9     .05       0  258.28    .035       0  458.28     .06       0
#XS Ineff= 2 , 0
                          250.14         1784.42
Permanent Ineff=
       F       F
Bank Sta=206.3,236.9
XS Rating Curve= 0 ,0
Exp/Cntr(USF)=0,0
Exp/Cntr=0.3,0.1

Type RM Length L Ch R = 1 ,17966   ,177.7,183.9,188.4
XS GIS Cut Line= 2
2021113.83379583273805.2463209422020783.17625511274070.082091302
#Sta/Elev= 30
       0 1831.66    22.9 1824.73    35.5 1816.35    47.6 1805.32    66.6 1792.26
    73.8 1788.55    90.1  1782.6    98.6 1780.97   121.1 1779.36   136.8 1779.25
     163 1780.35     191 1779.83   199.6 1778.25   206.6 1773.87   210.3 1772.22
   216.3 1770.73   228.9 1769.91   237.3 1770.48   241.6 1771.73   245.7 1776.14
   249.9 1777.28   329.7 1778.39   338.2 1783.45   341.5 1784.61   363.4 1786.51
     370 1788.44     376  1791.3     397 1804.11   404.5 1808.06   423.6 1814.95
#Mann= 6 ,-1 , 0
       0      .1       0     210     .05       0   210.3    .045       0
   241.6     .05       0     290     .06       0     330      .1       0
Bank Sta=210.3,241.6
XS Rating Curve= 0 ,0
Exp/Cntr=0.3,0.1

Type RM Length L Ch R = 1 ,17782   ,234.8,226.8,215.7
XS GIS Cut Line= 2
2021013.43757906273703.0056473812020606.80096857273912.691179625
#Sta/Elev= 30
       0 1831.06     8.8 1826.44      16 1821.65    39.2 1802.64    51.3 1790.73
    62.2  1781.9    70.8  1777.5    76.9 1776.39    87.9  1776.1   102.5 1776.69
   158.2 1776.47   165.5 1774.53   172.4 1769.76   176.6 1768.41   187.6 1767.66
   209.6 1769.68   220.9 1772.39   272.6 1773.37   299.7 1774.64   320.6  1773.7
   331.4 1774.63   375.9  1775.9   389.9 1777.38   411.8 1783.01   428.8 1793.17
   438.7 1800.56   442.4 1802.18   450.7 1802.24   453.5 1803.34   457.5 1806.49
#Mann= 5 ,-1 , 0
       0      .1       0   172.4    .045       0   209.6      .1       0
     290     .06       0     410      .1       0
#XS Ineff= 2 , 0
                             235            1776
Permanent Ineff=
       F       F
Bank Sta=172.4,209.6
XS Rating Curve= 0 ,0
Exp/Cntr=0.3,0.1

Type RM Length L Ch R = 1 ,17555   ,134.6,131.1,128.6
XS GIS Cut Line= 2
2020824.23716884273490.4732973182020510.50308534273816.876801788
#Sta/Elev= 30
       0 1852.72    49.2 1827.44    65.4 1815.32    86.5 1795.77   100.2 1786.15
   111.8 1779.04   123.4 1775.06     132 1773.56   141.1 1768.16   145.7 1766.57
   158.2 1768.23   168.4 1768.53   172.1 1768.13   177.5 1765.68   186.6 1764.45
   204.6 1765.95   209.4 1767.49   218.5 1768.47   234.8 1768.17   274.2 1769.74
   289.6 1769.01   303.8 1772.61     309 1773.15   332.2 1772.69   391.4 1775.14
   411.1 1780.91   427.4 1790.72   436.4 1791.93   441.1 1796.33   452.7  1802.9
#Mann= 6 ,-1 , 0
       0      .1       0   177.5    .045       0   204.6      .1       0
     280     .08       0     380     .04       0     420      .1       0
#XS Ineff= 2 , 0
                             275            1773
Permanent Ineff=
       F       F
Bank Sta=177.5,204.6
XS Rating Curve= 0 ,0
Exp/Cntr=0.3,0.1

Type RM Length L Ch R = 1 ,17424   ,148,137.1,126.8
XS GIS Cut Line= 2
2020722.97046665273381.0682821252020431.22069042 273757.26096524
#Sta/Elev= 30
       0  1855.2    18.1 1847.51    39.1 1836.45    60.6 1823.76    76.6 1812.53
    88.7 1805.64      97 1798.56   109.4 1786.36   121.9  1778.5   127.8 1775.73
   142.6 1771.77   151.6 1771.08   163.4 1762.82   167.6 1761.66   176.9 1761.33
   188.3 1762.11     198 1765.06     205 1765.72   213.2  1765.1   225.7 1766.27
   307.9 1765.44   321.2 1769.26   333.6 1772.59     357 1772.28   365.7 1773.43
   399.1 1773.71   420.1 1775.72   443.5 1786.64   462.1 1802.81   476.1 1813.01
#Mann= 6 ,-1 , 0
       0      .1       0   163.4    .045       0   188.3      .1       0
   321.2     .06       0   420.1     .04       0   462.1      .1       0
#XS Ineff= 2 , 0
                             293            1772
Permanent Ineff=
       F       F
Bank Sta=163.4,188.3
XS Rating Curve= 0 ,0
Exp/Cntr=0.3,0.1

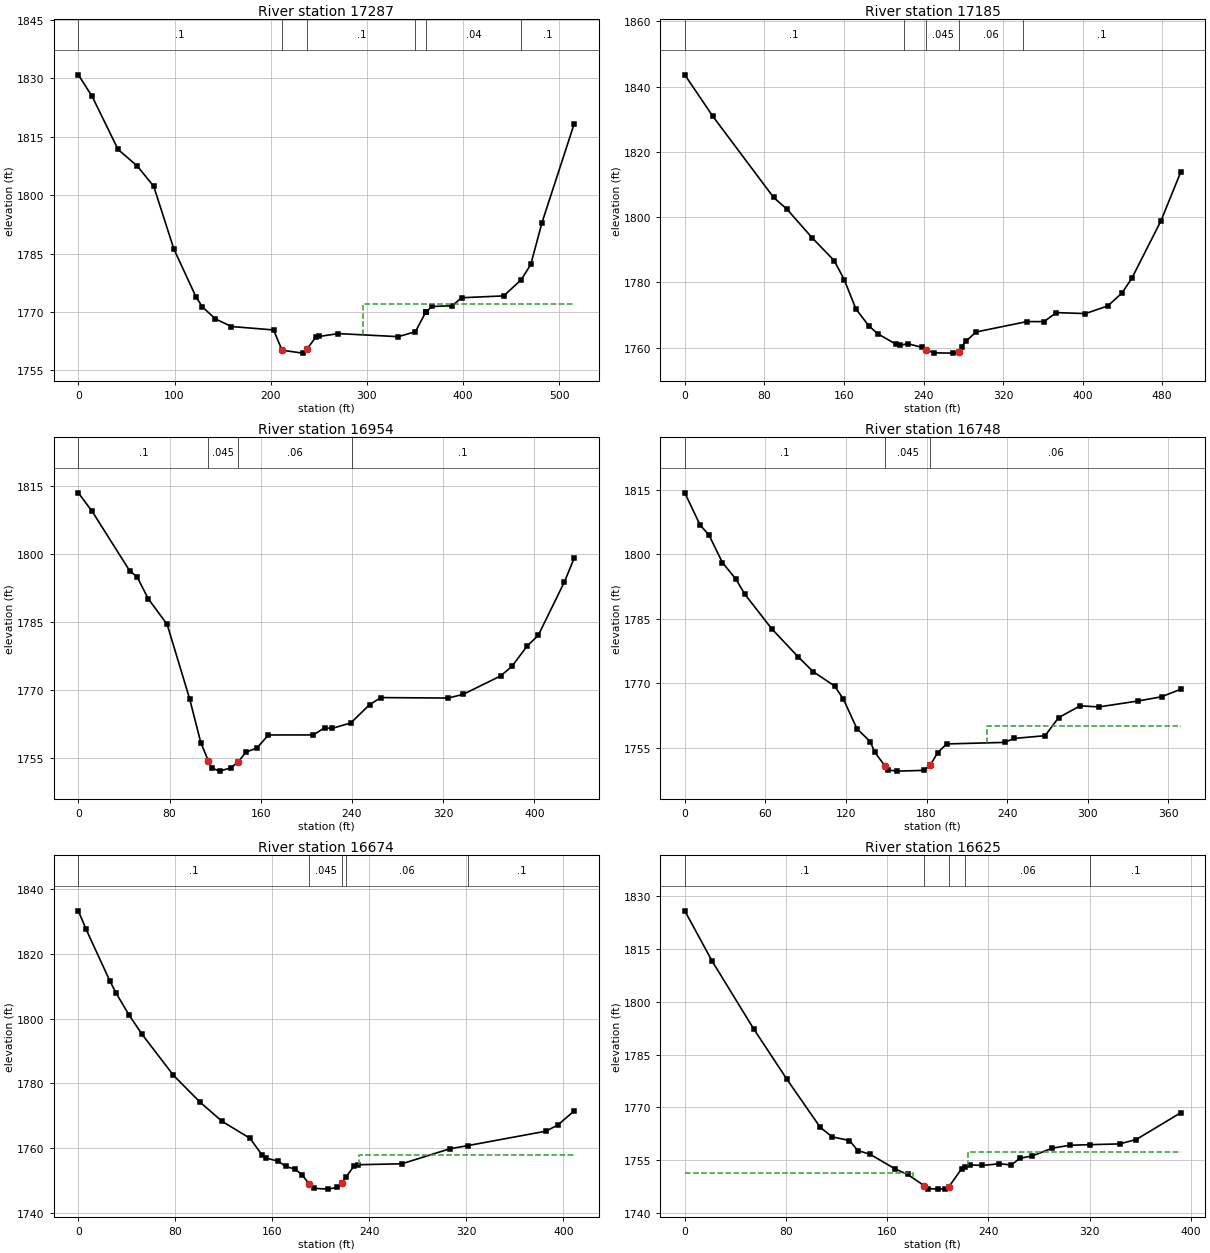
Type RM Length L Ch R = 1 ,17287   ,94.8,101.5,106.8
XS GIS Cut Line= 3
 2020545.1494638 273250.162045632020441.97594333273690.987848537
2020404.05282245273741.056739275
#Sta/Elev= 30
       0 1830.89    14.3 1825.38    41.3 1811.73    61.5 1807.41    78.4 1802.25
    99.3 1786.17   122.2 1773.94   128.9 1771.32   142.4 1768.23   159.2 1766.26
     203 1765.38   211.8 1760.18   233.1 1759.43   238.11760.579   246.8 1763.51
   250.2 1763.71   270.4 1764.44   332.7 1763.66   350.5 1764.93   361.4 1770.06
   361.4 1770.08   361.4 1770.09   368.1 1771.41   388.7 1771.59   398.5 1773.65
   442.3 1774.13   460.5 1778.29   470.4  1782.2   482.1 1792.97   515.5 1818.29
#Mann= 6 ,-1 , 0
       0      .1       0   211.8    .045       0   238.1      .1       0
   350.5     .06       0   361.4     .04       0   460.5      .1       0
#XS Ineff= 2 , 0
                             296            1772
Permanent Ineff=
       F       F
Bank Sta=211.8,238.1
XS Rating Curve= 0 ,0
Exp/Cntr=0.3,0.1

Type RM Length L Ch R = 1 ,17185   ,237.6,230.9,221.7
XS GIS Cut Line= 2
2020513.43915508273204.9748557042020292.55144942273651.895278732
#Sta/Elev= 30
       0 1843.63    28.1 1830.96    89.3 1806.04   102.6 1802.48   128.2 1793.62
   150.2 1786.69   160.4 1780.77   172.1 1771.83   185.1 1766.66   194.1 1764.25
   212.4 1761.04   216.7 1760.73     224 1761.23     238 1760.13     243 1759.18
     251 1758.41   269.9 1758.33   275.5 1758.69   278.2 1760.36   282.8 1762.01
   292.9 1764.82   344.1    1768   361.2 1767.98   373.5 1770.75   402.8 1770.45
   425.4 1772.82   439.6 1776.78   449.4 1781.25   478.8 1798.93   498.5 1813.75
#Mann= 5 ,-1 , 0
       0      .1       0     220     .06       0     243    .045       0
   275.5     .06       0     340      .1       0
Bank Sta=243,275.5
XS Rating Curve= 0 ,0
Exp/Cntr(USF)=0,0
Exp/Cntr=0.3,0.1

Type RM Length L Ch R = 1 ,16954   ,201.8,206,208.6
XS GIS Cut Line= 2
 2020240.5636006273163.4429057182020212.32551227 273597.42218147
#Sta/Elev= 30
       0  1813.4    12.1 1809.33      45 1796.27    51.6 1794.88    61.4 1790.08
    77.9 1784.47    97.6 1768.12   107.5  1758.4     114 1754.47   117.3 1752.86
   123.9  1752.2   133.8 1752.92   140.4 1754.26   146.9 1756.35   156.8 1757.33
   166.7 1760.15   206.1 1760.16     216 1761.72   222.5 1761.59     239  1762.8
   255.4  1766.8   265.3 1768.37   324.5 1768.27   337.6 1769.09   370.5 1773.15
   380.4 1775.26   393.5 1779.66   403.4 1782.05   426.4 1793.84   434.9 1799.02
#Mann= 4 ,-1 , 0
       0      .1       0     114    .045       0   140.4     .06       0
     240      .1       0
Bank Sta=114,140.4
XS Rating Curve= 0 ,0
Exp/Cntr=0.3,0.1

Type RM Length L Ch R = 1 ,16748   ,77.8,74.9,72.8
XS GIS Cut Line= 2
2020057.61106905273125.0110644432019990.43647685273488.086959469
#Sta/Elev= 30
       0 1814.25    11.4 1806.75      18 1804.44      28 1798.03      38 1794.21
    44.7 1790.67    64.7 1782.65    84.2 1776.18    95.5 1772.69   111.5 1769.34
   118.1 1766.28   128.1 1759.44   138.1 1756.38   141.5 1753.91     149 1750.77
   151.5  1749.8   158.2 1749.54   178.2 1749.72   182.8 1750.92   188.2 1753.79
   194.9 1755.86   238.2 1756.22   244.9 1757.13   268.3 1757.78   278.3 1761.96
   294.3 1764.72   308.3 1764.47   337.6 1765.85     355 1766.83   369.2 1768.57
#Mann= 3 ,-1 , 0
       0      .1       0     149    .045       0   182.8     .06       0
#XS Ineff= 2 , 0
                             225            1760
Permanent Ineff=
       F       F
Bank Sta=149,182.8
XS Rating Curve= 0 ,0
Exp/Cntr(USF)=0,0
Exp/Cntr=0.5,0.3

Type RM Length L Ch R = 1 ,16674   ,50,48.9,48
XS GIS Cut Line= 2
2019972.11613353273080.5981109222019932.69963728 273487.53179755
#Sta/Elev= 30
       0 1833.29     6.4 1827.57    26.2 1811.47    31.2 1807.82    41.9 1801.05
    52.5 1795.15    78.4 1782.47   100.3 1774.18   118.5 1768.24   141.5 1763.01
   151.4 1757.88   154.7 1756.91   164.6 1755.94   171.2  1754.3   178.5 1753.48
   184.4 1751.79   190.5 1748.74   194.3 1747.55   205.5 1747.29   213.5 1747.81
   217.4 1749.25   220.5 1750.94   227.2 1754.37   230.5 1754.83   266.8 1755.12
   306.3 1759.76   321.6 1760.77   385.5  1765.2   395.3  1767.1   408.8 1771.44
#Mann= 5 ,-1 , 0
       0      .1       0   190.5    .045       0   217.4      .1       0
   220.5     .06       0   321.6      .1       0
#XS Ineff= 2 , 0
       0   178.5    1753  231.14       0 1757.89
Permanent Ineff=
       F       F
Bank Sta=190.5,217.4
XS Rating Curve= 0 ,0
Exp/Cntr(USF)=0,0
Exp/Cntr=0.5,0.3

Type RM Length L Ch R = 1 ,16625   ,134.8,133,131.5
XS GIS Cut Line= 2
2019913.82413203 273081.708434762019893.83830295273473.097587656
#Sta/Elev= 30
       0 1825.89    21.7 1811.53    54.5  1792.3    80.8 1777.96   107.1 1764.32
   116.5 1761.64   130.1  1760.6   136.7 1757.76   146.5 1756.67   166.2 1752.54
   176.1 1750.96   189.2 1747.76   192.5 1746.93   200.5 1746.78   205.7 1746.84
   208.9 1747.52   218.8 1752.58   221.3 1753.21   225.4 1753.67   235.2  1753.5
   248.4 1753.99   258.2 1753.66   264.8 1755.55   274.6 1756.21   290.5 1758.42
   304.2 1759.25   320.6 1759.42   343.6 1759.63   356.8 1760.88   391.9 1768.47
#Mann= 5 ,-1 , 0
       0      .1       0   189.2    .045       0   208.9      .1       0
   221.3     .06       0   320.6      .1       0
#XS Ineff= 2 , 0
          180.43 1751.47   223.6         1757.37
Permanent Ineff=
       F       F
Bank Sta=189.2,208.9
XS Rating Curve= 0 ,0
Exp/Cntr(USF)=0,0
Exp/Cntr=0.5,0.3

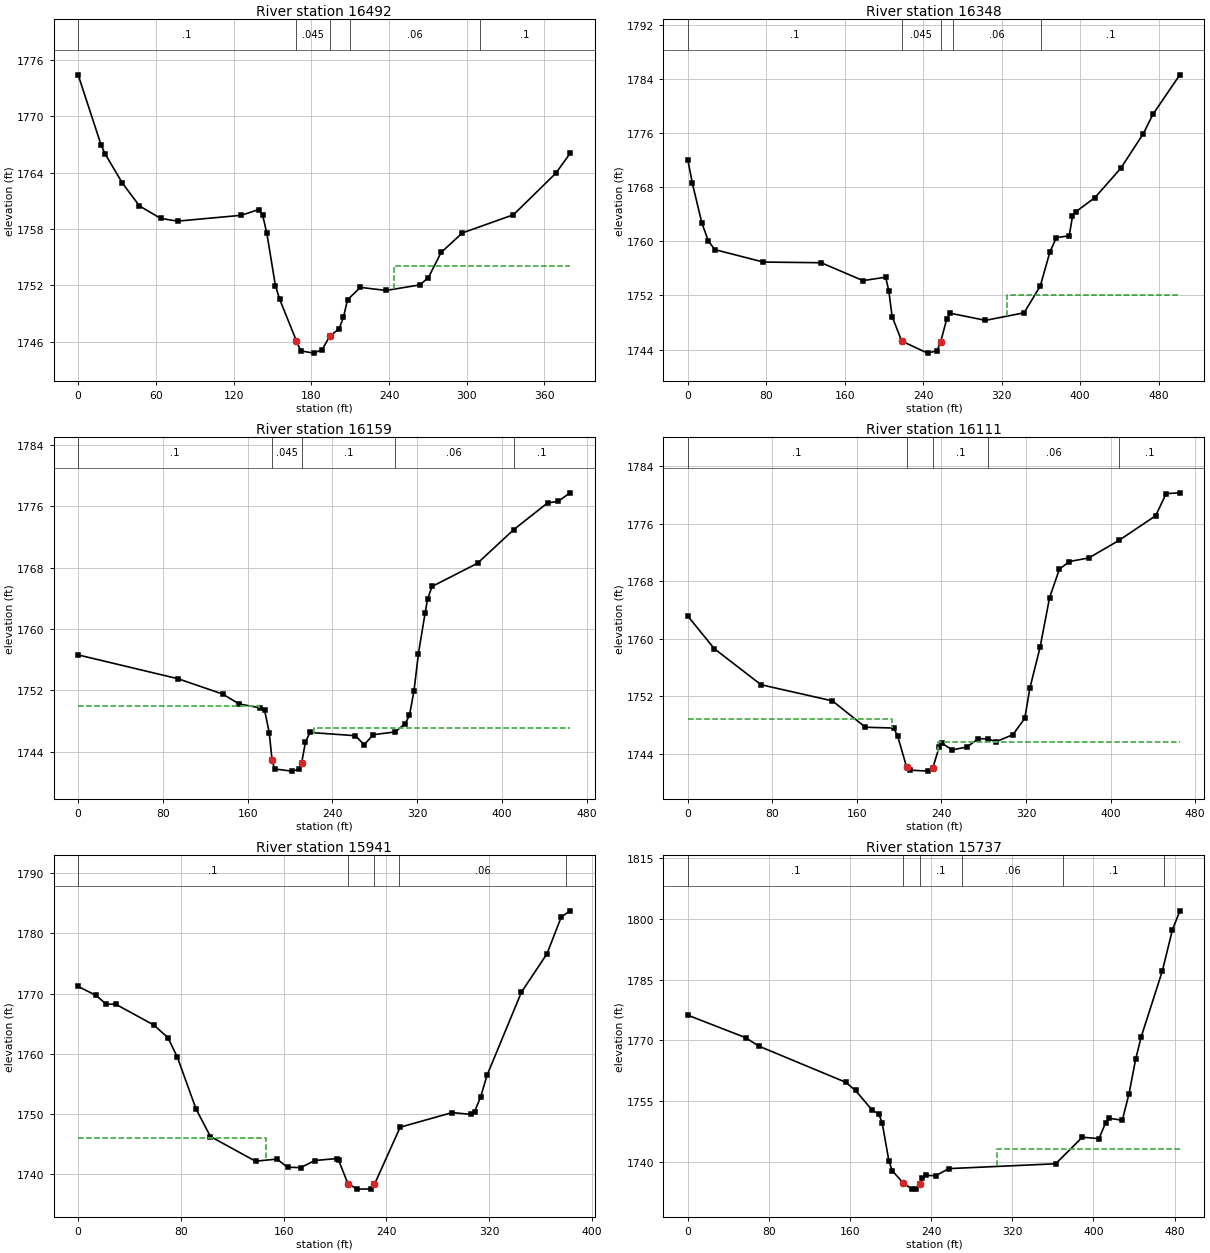
Type RM Length L Ch R = 1 ,16492   ,144,143.2,142.3
XS GIS Cut Line= 2
2019767.81654733273088.9255397072019774.47849036273468.656292304
#Sta/Elev= 30
       0  1774.4    17.7 1766.94      21 1765.94    34.1 1762.89    47.3 1760.45
    63.7 1759.12    76.8 1758.83     126 1759.45   139.4 1760.06   142.4 1759.49
   145.7 1757.52   152.3 1751.96   155.5 1750.54   168.4 1746.12   171.9 1745.02
   181.8 1744.78   188.4 1745.15   194.2 1746.58   201.5 1747.37   204.8 1748.59
     208 1750.46   217.9 1751.78   237.6 1751.45   263.8 1752.04   270.4 1752.82
   280.2 1755.49   296.6 1757.57   336.1 1759.51   368.8 1763.93   379.8 1766.04
#Mann= 5 ,-1 , 0
       0      .1       0   168.4    .045       0   194.2      .1       0
     210     .06       0     310      .1       0
#XS Ineff= 2 , 0
                             244            1754
Permanent Ineff=
       F       F
Bank Sta=168.4,194.2
XS Rating Curve= 0 ,0
Exp/Cntr(USF)=0,0
Exp/Cntr=0.3,0.1

Type RM Length L Ch R = 1 ,16348   ,207.4,189.9,174.1
XS GIS Cut Line= 2
2019616.26939738273036.5468776912019641.29950656273537.551740013
#Sta/Elev= 30
       0 1772.02     4.5 1768.63    14.3 1762.69    20.9 1760.05    27.5 1758.79
    76.8 1756.95   135.9 1756.85   178.6  1754.2   201.6 1754.71   204.9 1752.65
   208.2 1748.89     218 1745.25   244.3 1743.47   254.1 1743.83   257.7 1745.15
     264 1748.57   267.3 1749.38   303.4 1748.32   342.8 1749.44   359.3 1753.41
   369.1 1758.45   375.7 1760.57   388.8 1760.83   392.1 1763.71   395.4 1764.38
   415.1  1766.5   441.4 1770.84   464.4 1775.97   474.2 1778.83   501.6 1784.66
#Mann= 5 ,-1 , 0
       0      .1       0     218    .045       0   257.7      .1       0
     270     .06       0     360      .1       0
#XS Ineff= 2 , 0
                             325            1752
Permanent Ineff=
       F       F
Bank Sta=218,257.7
XS Rating Curve= 0 ,0
Exp/Cntr=0.5,0.3

Type RM Length L Ch R = 1 ,16159   ,48.7,47.4,44.9
XS GIS Cut Line= 4
2019374.76190868273141.6659220132019421.39550988  273293.2251259
  2019550.748237 273448.670463222019568.51341841273550.820256317
#Sta/Elev= 30
       0 1756.62    94.4 1753.51   136.4 1751.52   152.1 1750.22   171.9 1749.72
   176.1 1749.38   180.5 1746.44   183.1 1742.87   185.5 1741.75   201.7 1741.47
   208.8 1741.72   211.1 1742.59   214.6 1745.25   218.9 1746.51   261.6 1746.09
   270.1 1744.91   278.6 1746.22   299.2 1746.58   308.9 1747.67   312.8 1748.75
   317.1 1751.92   321.3 1756.79   327.6 1762.08   329.9 1763.88   334.1 1765.54
   377.1 1768.57   411.1 1772.93   443.2 1776.43   453.2 1776.64   464.5 1777.75
#Mann= 5 ,-1 , 0
       0      .1       0   183.1    .045       0   211.1      .1       0
   299.2     .06       0   411.1      .1       0
#XS Ineff= 2 , 0
       0   171.1    1750   223.1       0  1747.1
Permanent Ineff=
       F       F
Bank Sta=183.1,211.1
XS Rating Curve= 0 ,0
Exp/Cntr(USF)=0,0
Exp/Cntr=0.5,0.3

Type RM Length L Ch R = 1 ,16111   ,164,169.9,176.7
XS GIS Cut Line= 4
2019333.67992667273148.3278650412019383.64449938273325.424517202
2019512.99722651273455.8875681672019528.54176024273552.485742074
#Sta/Elev= 30
       0 1763.14    25.1  1758.6    69.2  1753.6   136.8 1751.35     168 1747.68
   194.7 1747.57   198.5 1746.46   206.9 1742.17   210.1 1741.71   227.1 1741.57
   231.7 1741.97   237.9 1744.98   240.2 1745.46   250.2 1744.53     264 1744.93
     275 1746.09   284.3 1746.06   291.3 1745.65   307.5 1746.64   318.8 1748.91
   323.7 1753.16   333.3 1758.82   342.3 1765.73   351.6 1769.69     361 1770.75
   379.5 1771.26   407.9 1773.69   442.7 1777.13   452.6 1780.21   465.6 1780.32
#Mann= 5 ,-1 , 0
       0      .1       0   206.9    .045       0   231.7      .1       0
   284.3     .06       0   407.9      .1       0
#XS Ineff= 2 , 0
       0  192.76 1748.87  236.44       0 1745.68
Permanent Ineff=
       F       F
Bank Sta=206.9,231.7
XS Rating Curve= 0 ,0
Exp/Cntr(USF)=0,0
Exp/Cntr=0.5,0.3

Type RM Length L Ch R = 1 ,15941   ,193.7,204.5,216
XS GIS Cut Line= 2
2019174.17556688273257.8154596532019349.48168919273598.291547887
#Sta/Elev= 30
       0 1771.19    13.9 1769.71    21.9 1768.24    29.2 1768.25    58.8  1764.8
    69.9 1762.69    77.2 1759.47    91.8 1750.83     103 1746.26   138.1 1742.16
   154.7 1742.51   163.1 1741.16   173.2 1741.09   184.2 1742.27   201.4  1742.6
   202.7 1742.37   210.1 1738.39   217.4 1737.52   228.2 1737.55   230.7 1738.31
   250.7 1747.81   291.2 1750.24     306 1749.93   308.6 1750.37   313.4 1752.87
   318.3 1756.42   345.1 1770.24     365 1776.62   376.1 1782.72     383 1783.76
#Mann= 5 ,-1 , 0
       0      .1       0   210.1    .045       0   230.7      .1       0
     250     .06       0     380      .1       0
#XS Ineff= 2 , 0
             146    1746
Permanent Ineff=
       F       F
Bank Sta=210.1,230.7
XS Rating Curve= 0 ,0
Exp/Cntr=0.3,0.1

Type RM Length L Ch R = 1 ,15737   ,190.7,182.1,175.8
XS GIS Cut Line= 2
2019095.06360745273227.1589175182019061.33621689273711.214827327
#Sta/Elev= 30
       0 1776.18    56.8 1770.64    69.9 1768.54   155.5 1759.62   165.3 1757.57
   181.8  1752.7   188.3 1751.74   191.6 1749.57   198.2 1740.19   201.5 1737.75
   212.6 1734.63   221.2 1733.18   224.5 1733.19   228.7 1734.44   231.1 1735.82
   234.4 1736.58   244.3  1736.5   257.4 1738.25   362.7 1739.45     389 1746.01
   405.4 1745.67     412 1749.58   415.3 1750.71   428.4 1750.21     435 1756.71
   441.6 1765.31     447 1770.76   467.9  1787.1   477.8 1797.25   485.2 1801.99
#Mann= 6 ,-1 , 0
       0      .1       0   212.6    .045       0   228.7      .1       0
     270     .06       0     370      .1       0     470     .05       0
#XS Ineff= 2 , 0
                             305            1743
Permanent Ineff=
       F       F
Bank Sta=212.6,228.7
XS Rating Curve= 0 ,0
Exp/Cntr=0.3,0.1

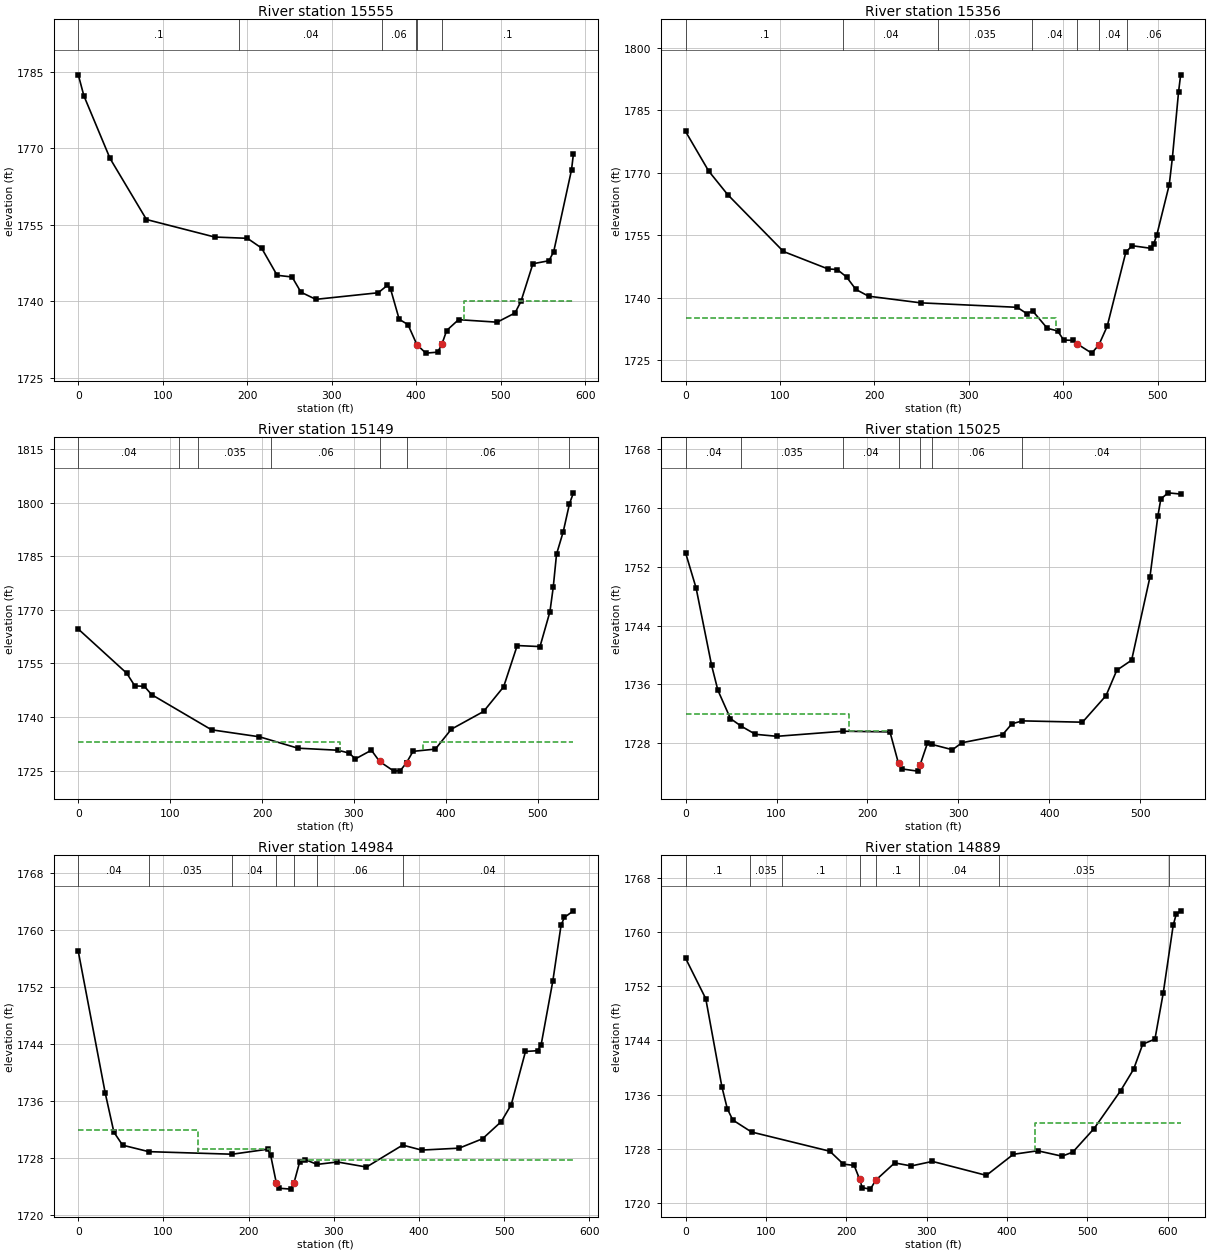
Type RM Length L Ch R = 1 ,15555   ,188.5,198.5,208
XS GIS Cut Line= 2
     2018763.389      273126.7232018975.84388422273673.078004966
#Sta/Elev= 30
       0 1784.37     6.6 1780.27    37.6 1767.99    80.7 1756.04   161.5 1752.61
   200.2 1752.36     217 1750.45   235.4 1745.12   253.1 1744.79   263.6 1741.81
   281.2 1740.41   355.1  1741.7   365.7 1743.13   369.7 1742.43   379.9 1736.51
   390.3 1735.46   400.9 1731.53   411.4 1729.88   425.5 1730.07   430.5 1731.64
   436.1 1734.31   450.2 1736.43   495.9 1735.94     517 1737.74   524.1 1740.02
   538.2 1747.38   557.2 1747.97   562.8 1749.73   583.9 1765.74   586.2 1768.93
#Mann= 6 ,-1 , 0
       0      .1       0     190     .04       0     360     .06       0
     400      .1       0   400.9    .045       0   430.5      .1       0
#XS Ineff= 2 , 0
                             457            1740
Permanent Ineff=
       F       F
Bank Sta=400.9,430.5
XS Rating Curve= 0 ,0
Exp/Cntr=0.3,0.1

Type RM Length L Ch R = 1 ,15356   ,199.7,207,213
XS GIS Cut Line= 3
     2018706.219      273139.3542018742.41254857273240.340163971
2018717.91845044 273656.73994807
#Sta/Elev= 30
       0 1779.89    24.5 1770.38    44.7  1764.7   103.7 1751.06   150.8 1746.88
   160.7 1746.73   170.5 1744.95   180.4 1741.96   193.8 1740.33   249.1 1738.73
   351.3 1737.66   361.2 1736.17   367.7 1736.77   383.2 1732.61     394    1732
   400.6 1729.79   410.5 1729.73   414.2 1728.96   430.2 1726.66   437.7  1728.6
   446.6 1733.11   466.3 1750.86   472.9 1752.45   492.6 1751.83   495.9 1752.87
   499.2 1755.08   512.3 1767.07   515.6 1773.47   522.2 1789.43   524.4 1793.47
#Mann= 7 ,-1 , 0
       0      .1       0  167.28     .04       0  267.28    .035       0
  367.28     .04       0   414.2    .045       0   437.7     .04       0
  467.28     .06       0
#XS Ineff= 2 , 0
             392    1735
Permanent Ineff=
       F       F
Bank Sta=414.2,437.7
XS Rating Curve= 0 ,0
Exp/Cntr=0.3,0.1

Type RM Length L Ch R = 1 ,15149   ,124.6,124,123.3
XS GIS Cut Line= 3
2018636.51950109273199.6169758242018491.79946884273608.264784796
2018535.75742914273704.054165241
#Sta/Elev= 30
       0 1764.61    52.7 1752.26    61.5 1748.71    71.9  1748.6    79.7 1746.29
     145 1736.43   197.2 1734.47     239 1731.29   282.8 1730.71   294.7 1729.92
   301.6 1728.29     319 1730.72   327.9 1727.58   343.4 1724.87   350.4 1724.99
   357.3 1727.25   357.3 1727.26   364.3  1730.4   388.6 1731.03     406  1736.6
   441.1 1741.56   462.9 1748.45   477.7    1760   502.5 1759.71   513.3 1769.45
   516.9 1776.28   520.5 1785.56   527.8 1791.85   534.6 1799.68   538.9 1802.72
#Mann= 7 ,-1 , 0
       0     .04       0     110      .1       0     130    .035       0
     210     .06       0   327.9    .045       0   357.3     .06       0
  533.52      .1       0
#XS Ineff= 2 , 0
             285    1733     375            1733
Permanent Ineff=
       F       F
Bank Sta=327.9,357.3
XS Rating Curve= 0 ,0
Exp/Cntr(USF)=0,0
Exp/Cntr=0.5,0.3

Type RM Length L Ch R = 1 ,15025   ,41.6,41,40.5
XS GIS Cut Line= 3
2018481.15566865273239.9774531492018351.16906207273656.188099927
2018413.61525872273744.526622017
#Sta/Elev= 30
       0 1753.92    11.6 1749.12    28.7 1738.56    35.6 1735.18    49.4 1731.33
    61.2  1730.3    76.9 1729.19   100.5 1728.92   173.1 1729.61   224.7 1729.52
   234.1 1725.22   238.4 1724.47     255 1724.18   257.6 1724.95   265.9 1727.99
   270.7 1727.82   293.4 1727.09   303.7 1728.04   348.4 1729.13   358.7 1730.62
   370.3 1731.02   436.3 1730.84   462.2 1734.46     474 1737.91   490.3 1739.28
   510.4 1750.57   519.1 1758.85   522.4 1761.22   530.4 1762.06   544.2 1761.89
#Mann= 7 ,-1 , 0
       0     .04       0    61.2    .035       0   173.1     .04       0
   234.1    .045       0   257.6     .04       0   270.7     .06       0
   370.3     .04       0
#XS Ineff= 3 ,-1
       0     180    1732     180   224.1  1729.7   267.6     500  1727.7
Permanent Ineff=
       F       F       F
Bank Sta=234.1,257.6
XS Rating Curve= 0 ,0
Exp/Cntr(USF)=0,0
Exp/Cntr=0.5,0.3

Type RM Length L Ch R = 1 ,14984   ,96.1,94.9,93.7
XS GIS Cut Line= 3
2018434.80985205273227.1495702312018303.95364509 273693.50351012
2018356.49983496273774.988181359
#Sta/Elev= 30
       0 1757.01    31.6 1737.14    41.8 1731.64      52 1729.82    82.7 1728.91
   180.7 1728.55   222.4 1729.25   225.8 1728.42   232.6 1724.45     236 1723.77
   249.7 1723.65   253.1 1724.48   259.9 1727.47   266.5 1727.79   280.3 1727.12
   304.2 1727.46   338.3 1726.75   380.8 1729.83     403 1729.13   447.1  1729.4
   474.6 1730.72   496.6 1733.13   508.3 1735.51     525 1742.97   539.3 1743.08
   543.4 1743.93   557.1 1752.86   566.8 1760.72   570.7 1761.79   581.3 1762.71
#Mann= 7 ,-1 , 0
       0     .04       0    82.7    .035       0   180.7     .04       0
   232.6    .045       0   253.1     .04       0   280.3     .06       0
   380.8     .04       0
#XS Ineff= 3 ,-1
       0     140    1732     140   224.6  1729.3   261.1     600  1727.7
Permanent Ineff=
       F       F       F
Bank Sta=232.6,253.1
XS Rating Curve= 0 ,0
Exp/Cntr(USF)=0,0
Exp/Cntr=0.5,0.3

Type RM Length L Ch R = 1 ,14889   ,280.7,266.2,246.6
XS GIS Cut Line= 3
2018324.51519765273219.8262623572018222.46897386273690.457354186
2018289.48440441273806.972818668
#Sta/Elev= 30
       0 1756.14    25.2 1750.15    45.3 1737.13      52 1733.91    58.8 1732.25
    82.1 1730.48   179.6 1727.64   196.4 1725.74   209.8 1725.55   216.5 1723.54
   219.9 1722.26     230 1722.05   236.7 1723.37   260.2 1725.92   280.8 1725.47
   307.2 1726.14   374.3 1724.08   407.9 1727.19   438.1 1727.71   468.4 1726.91
   481.8 1727.51   508.3 1730.99   541.4 1736.59   557.5 1739.75   568.8 1743.44
     584 1744.19   594.3 1750.97   606.7 1760.97   610.5 1762.64     616 1763.12
#Mann= 8 ,-1 , 0
       0      .1       0      80    .035       0     120      .1       0
   216.5    .045       0   236.7      .1       0     290     .04       0
     390    .035       0  601.57     .04       0
#XS Ineff= 2 , 0
                           435.4         1731.75
Permanent Ineff=
       F       F
Bank Sta=216.5,236.7
XS Rating Curve= 0 ,0
Exp/Cntr(USF)=0,0
Exp/Cntr=0.3,0.1