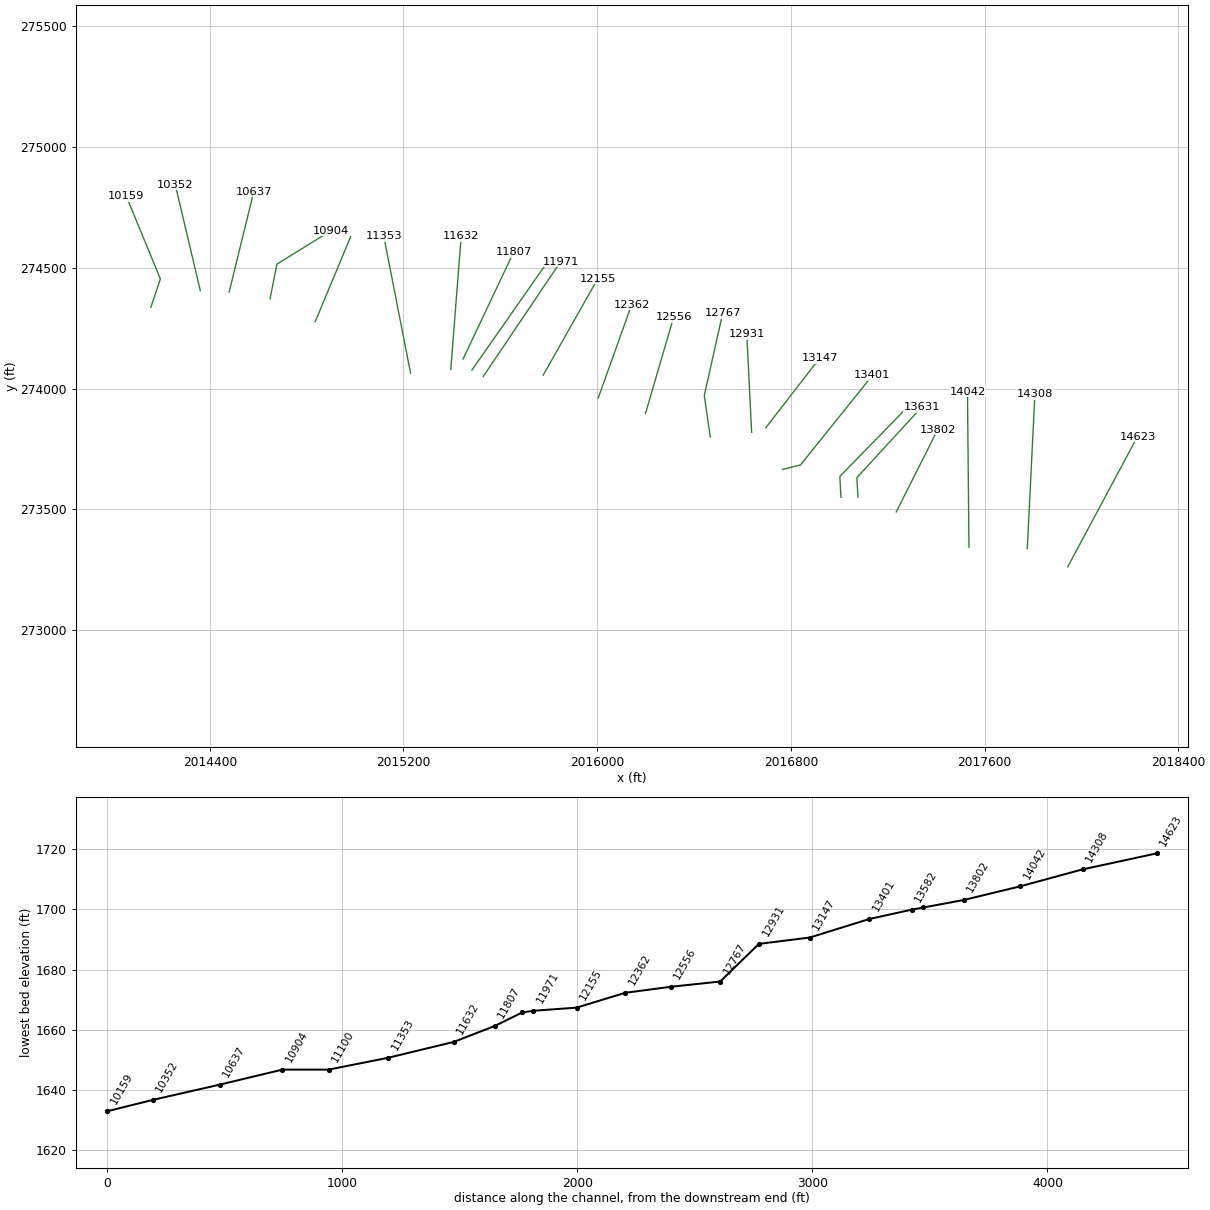
HEC-RAS study LAURELCK_A.prj: LAURELCK_A

--- LAURELCK_A.g01 (geometry) --- (continued)

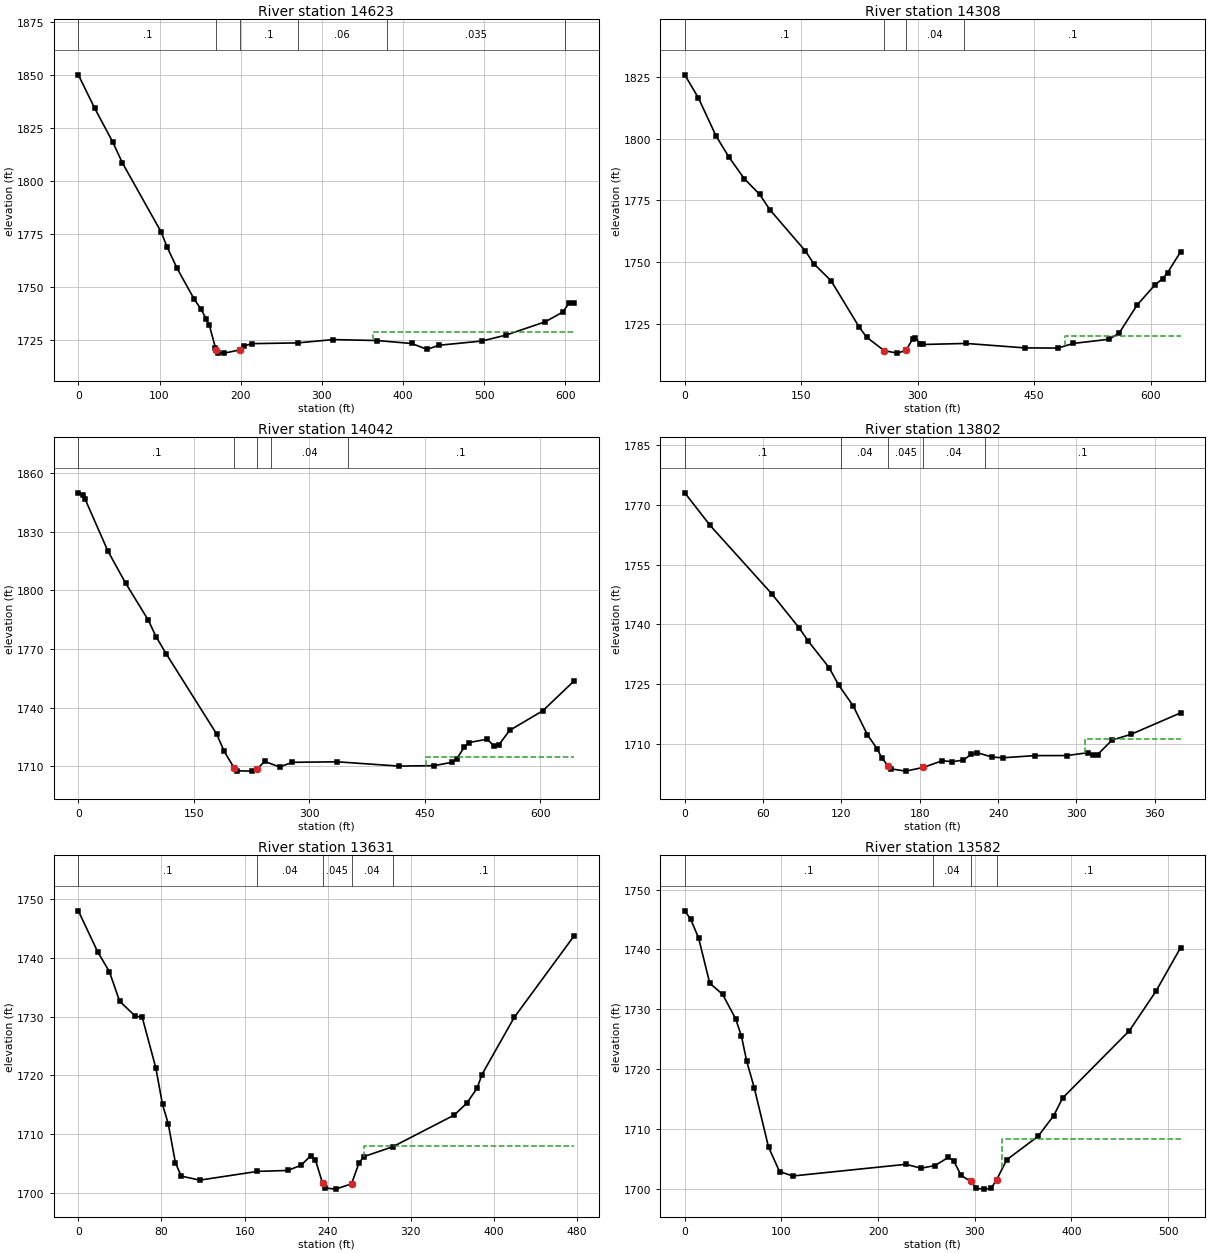
Type RM Length L Ch R = 1 ,14623   ,298.4,315,319.8
XS GIS Cut Line= 2
2017943.71183405273262.882576841 2018231.6753374273801.400427532
#Sta/Elev= 30
       0 1850.04      20 1834.37    42.3 1818.36    54.3 1808.41   101.9 1775.86
   109.5 1768.55   121.7 1758.59   142.8 1743.98   150.8 1739.52   157.7 1734.63
   161.4 1731.68   168.8 1721.21   170.1 1720.24   172.6 1718.69   179.6 1718.57
   199.2  1720.1   204.1  1721.9   213.5 1723.05     270  1723.4   313.9 1724.97
   367.4 1724.52   410.7 1723.12   429.5 1720.33   444.1 1722.28   497.4  1724.3
   526.5 1727.07     575 1733.35   596.7 1737.97   604.1 1742.02   610.7  1742.3
#Mann= 6 ,-1 , 0
       0      .1       0   170.1    .045       0   199.2      .1       0
     270     .06       0     380    .035       0     600     .04       0
#XS Ineff= 2 , 0
                          362.42         1728.34
Permanent Ineff=
       F       F
Bank Sta=170.1,199.2
XS Rating Curve= 0 ,0
Exp/Cntr(USF)=0,0
Exp/Cntr=0.3,0.1

Type RM Length L Ch R = 1 ,14308   ,262.2,266,265.2
XS GIS Cut Line= 2
2017776.67560249273338.5708692642017807.99489591273976.266482441
#Sta/Elev= 30
       0 1825.81    17.4 1816.53    40.4 1800.99    56.9 1792.51    76.6  1783.8
    96.3  1777.5   109.4 1771.31   155.4 1754.51     166 1749.46   188.3 1742.55
   224.4 1723.89   234.2 1719.69   256.8 1714.25   273.7 1713.26     285  1714.4
   293.4    1719   296.7 1719.43   303.2 1716.99   306.5 1716.75   362.3 1717.18
   437.9 1715.38   480.6  1715.3   500.3 1717.18   546.3 1718.87   559.4  1721.4
   582.4 1732.67   605.4 1740.86   615.3 1743.34   621.8 1745.86   638.5 1754.25
#Mann= 4 ,-1 , 0
       0      .1       0   256.8    .045       0     285     .04       0
     360      .1       0
#XS Ineff= 2 , 0
                             490            1720
Permanent Ineff=
       F       F
Bank Sta=256.8,285
XS Rating Curve= 0 ,0
Exp/Cntr(USF)=0,0
Exp/Cntr=0.3,0.1

Type RM Length L Ch R = 1 ,14042   ,251.3,239.8,228.1
XS GIS Cut Line= 2
2017535.69103926273343.7907515012017529.60117665273987.576227286
#Sta/Elev= 30
       0 1849.83     5.6 1848.65     8.9  1846.5    38.5 1819.99    61.4 1803.67
    90.9 1784.75   100.8  1776.4   113.9  1767.7   179.5 1726.65   189.4 1717.72
   202.5  1709.1   205.8 1707.79   224.9 1707.62     232 1708.69   241.9 1712.59
   261.3 1709.76     278 1712.13   336.5 1712.38   415.8  1710.2   461.7 1710.41
   484.7 1712.09   491.2 1713.82   501.1 1719.83   507.6 1722.24   530.6 1723.92
   539.6 1720.64   546.2 1721.17   560.1 1728.46   603.1 1738.47   643.8 1753.75
#Mann= 5 ,-1 , 0
       0      .1       0   202.5    .045       0     232      .1       0
     250     .04       0     350      .1       0
#XS Ineff= 2 , 0
                             451            1715
Permanent Ineff=
       F       F
Bank Sta=202.5,232
XS Rating Curve= 0 ,0
Exp/Cntr(USF)=0,0
Exp/Cntr=0.3,0.1

Type RM Length L Ch R = 1 ,13802   ,176.5,171.3,163.5
XS GIS Cut Line= 2
2017235.52941526 273490.174471542017406.19030147273829.440088708
#Sta/Elev= 30
       0 1773.01    19.4 1764.82    66.5 1747.68    87.4 1739.16    94.7 1735.69
   110.5 1729.11   117.9 1724.71   128.9 1719.53   139.9 1712.22   147.3 1708.71
   150.9 1706.43   155.8 1704.37   158.3 1703.65   169.3  1703.1   182.7 1704.04
   197.3 1705.72   204.7 1705.46   213.4 1705.87   219.3 1707.32   224.2 1707.72
   235.4 1706.62   243.8 1706.46   268.5    1707   292.6 1707.01   308.9 1707.73
   312.5 1707.04   316.2 1707.27   327.2 1710.87   341.9 1712.36   379.8 1717.73
#Mann= 5 ,-1 , 0
       0      .1       0     120     .04       0   155.8    .045       0
   182.7     .04       0     230      .1       0
#XS Ineff= 2 , 0
                          306.65         1711.09
Permanent Ineff=
       F       F
Bank Sta=155.8,182.7
XS Rating Curve= 0 ,0
Exp/Cntr(USF)=0,0
Exp/Cntr=0.5,0.3

Type RM Length L Ch R = 1 ,13631   ,50.5,49.4,48.9
XS GIS Cut Line= 3
2017077.30492671273550.6058252472017072.60996966273631.423314325
 2017340.3933333273923.337845378
#Sta/Elev= 30
       0 1748.01    18.7    1741    29.9 1737.64    39.7 1732.63    54.8 1730.08
    61.5 1729.87    74.5  1721.3      81 1715.04    86.5 1711.76    93.4 1705.12
      99 1702.84   116.8 1702.15   172.4 1703.64   201.4  1703.8   214.2 1704.67
   223.6 1706.29   228.1  1705.6   235.1 1701.58   237.8 1700.81   247.5 1700.62
   262.9 1701.52   269.9    1705   274.5 1706.15   302.4 1707.82   361.7 1713.23
   373.7 1715.25   383.7  1717.8   388.3 1720.11   419.5 1729.88   477.1 1743.76
#Mann= 5 ,-1 , 0
       0      .1       0   172.4     .04       0   235.1    .045       0
   262.9     .04       0   302.4      .1       0
#XS Ineff= 2 , 0
       0   230.5  1704.1   274.6       0  1707.9
Permanent Ineff=
       F       F
Bank Sta=235.1,262.9
XS Rating Curve= 0 ,0
Exp/Cntr(USF)=0,0
Exp/Cntr=0.5,0.3

Type RM Length L Ch R = 1 ,13582   ,178.9,181,182.8
XS GIS Cut Line= 3
2017007.06916066273550.0904945292017002.40229259273636.560461427
2017299.95561327273941.843242679
#Sta/Elev= 30
       0 1746.47       6 1745.07    14.2 1741.97    25.8 1734.36    39.1  1732.5
    52.6  1728.4    58.6 1725.49      64 1721.33    71.8 1716.89    86.6 1706.95
      98 1702.84   111.7  1702.1   228.6 1704.05   244.6  1703.4   258.8 1703.85
   272.7 1705.22     278 1704.69   285.8 1702.19   295.9 1701.19   301.5 1700.04
   309.8  1699.9   316.8 1700.02   322.5 1701.44     333 1704.81   365.5 1708.75
   381.7 1712.22   390.8 1715.14   459.9 1726.41   487.4 1733.02   512.9 1740.32
#Mann= 4 ,-1 , 0
       0      .1       0   256.6     .04       0   295.9    .045       0
   322.5      .1       0
#XS Ineff= 2 , 0
                          328.48         1708.32
Permanent Ineff=
       F       F
Bank Sta=295.9,322.5
XS Rating Curve= 0 ,0
Exp/Cntr(USF)=0,0
Exp/Cntr=0.5,0.3

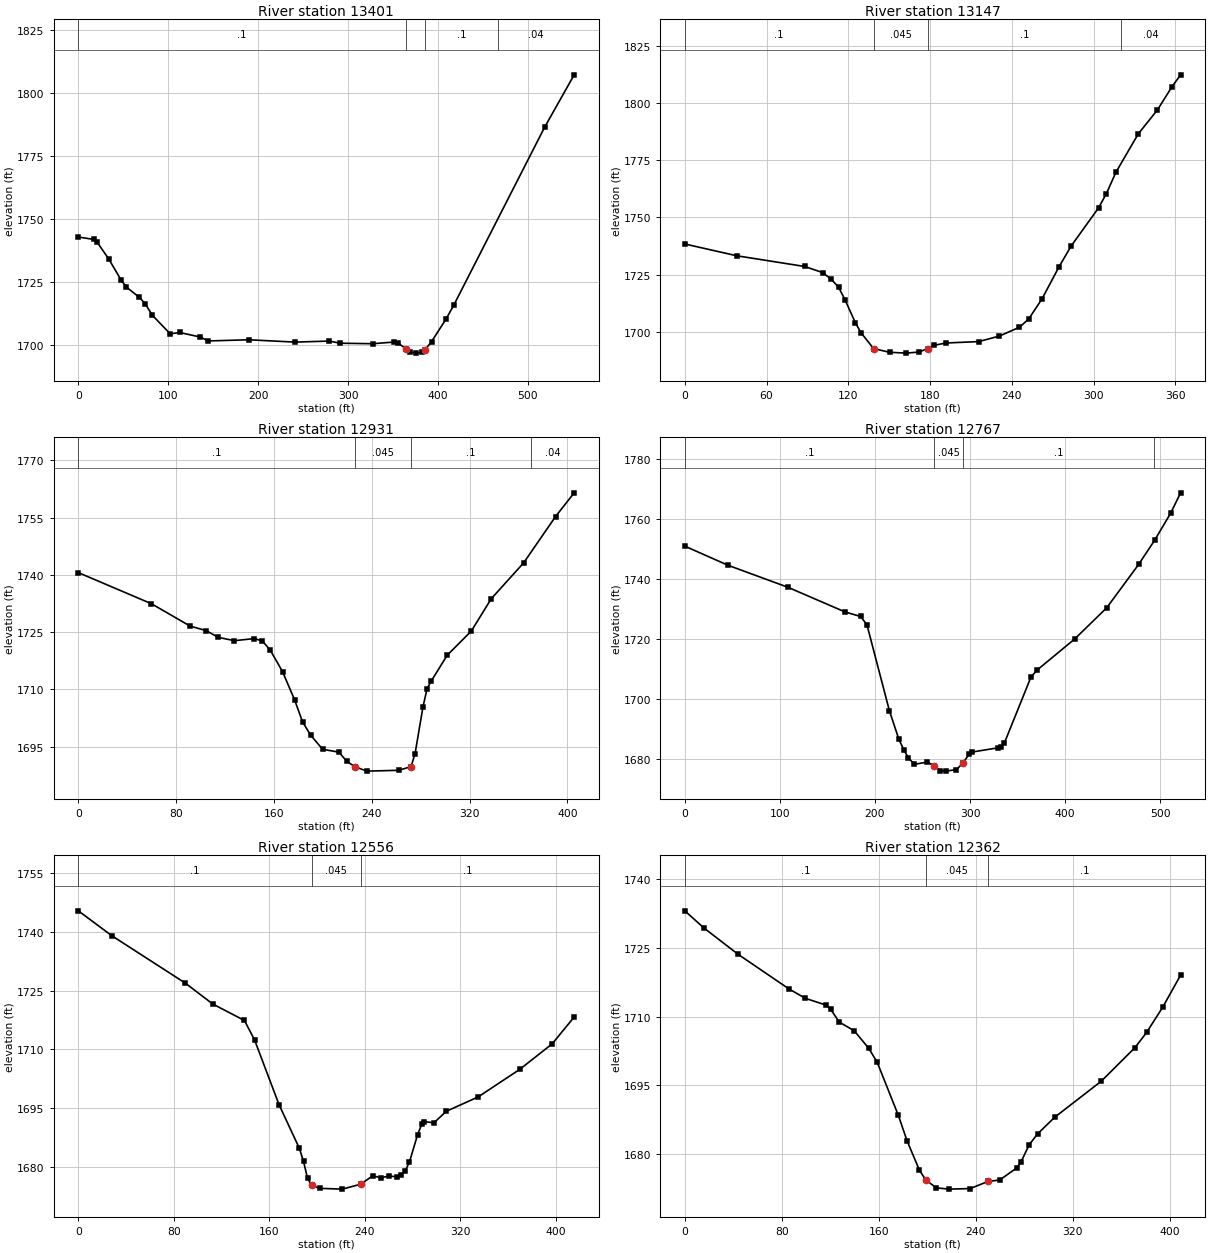
Type RM Length L Ch R = 1 ,13401   ,260.6,253.4,249.8
XS GIS Cut Line= 3
2016765.15774923273665.3047983992016839.70674111 273683.95307722
 2017136.9018875274054.203965925
#Sta/Elev= 30
       0 1742.83      17 1741.87    20.4 1741.04    33.9 1734.07    47.5 1725.82
    53.4 1722.98    67.8 1718.93    74.5 1716.33    82.3 1711.82   102.2 1704.44
   112.7 1704.97   135.9 1703.15   144.3 1701.62   189.7 1702.08   241.1 1701.16
   278.9 1701.57   291.6 1700.72   327.4 1700.52     351 1701.18   355.4 1700.86
   364.7 1698.44   369.5 1697.23   375.7 1696.79   382.5 1697.08   385.7 1698.07
   392.9 1701.33   409.1 1710.31   417.8 1715.89   518.7 1786.31   551.6 1807.12
#Mann= 4 ,-1 , 0
       0      .1       0   364.7    .045       0   385.7      .1       0
  466.85     .04       0
Bank Sta=364.7,385.7
XS Rating Curve= 0 ,0
Exp/Cntr=0.3,0.1

Type RM Length L Ch R = 1 ,13147   ,185.7,215.7,233
XS GIS Cut Line= 2
2016696.21373205273837.6463188852016918.79633173274125.451016742
#Sta/Elev= 30
       0 1738.39    38.1 1733.24    87.9 1728.55   101.1 1725.89   107.5 1722.93
   112.8  1719.5   117.5 1714.06   125.2 1703.88   129.2 1699.63   138.5 1692.64
   150.2 1691.01   162.5 1690.64   171.9 1691.13   178.3 1692.66   182.6 1694.02
   191.6 1695.07   215.7 1695.69   230.9 1698.13   245.5 1701.95   252.3 1705.55
   262.1 1714.38   274.5 1728.32   283.5 1737.53   303.6 1754.21   309.3  1760.4
   316.3 1769.74   332.7 1786.55   346.7 1796.98   357.5 1807.24   363.8  1812.4
#Mann= 4 ,-1 , 0
       0      .1       0   138.5    .045       0   178.3      .1       0
     320     .04       0
Bank Sta=138.5,178.3
XS Rating Curve= 0 ,0
Exp/Cntr=0.3,0.1

Type RM Length L Ch R = 1 ,12931   ,171.7,164.8,157.4
XS GIS Cut Line= 2
2016638.09299702273819.1392374432016618.17085868 274224.17474099
#Sta/Elev= 30
       0 1740.57    59.7 1732.43    91.4 1726.56   104.6 1725.37   114.4 1723.61
   127.6 1722.73     144 1723.29   150.6 1722.64   157.1 1720.18     167 1714.62
   176.8 1707.29   183.4 1701.44     190 1697.97   199.8 1694.27   213.1 1693.52
   219.5 1691.14   226.1 1689.71     236 1688.55   262.2 1688.77   272.1 1689.74
   275.4 1693.14   281.9 1705.45   285.2 1710.14   288.5  1712.1   301.7 1718.93
   321.4 1725.26   337.8 1733.77   364.1 1743.09   390.3 1755.27   405.5 1761.48
#Mann= 4 ,-1 , 0
       0      .1       0   226.1    .045       0   272.1      .1       0
     370     .04       0
Bank Sta=226.1,272.1
XS Rating Curve= 0 ,0
Exp/Cntr=0.3,0.1

Type RM Length L Ch R = 1 ,12767   ,212.7,211.1,207.9
XS GIS Cut Line= 3
2016467.26426887273799.8660853432016442.59341224273971.543011006
2016518.45915898 274311.17885088
#Sta/Elev= 30
       0 1750.91    45.4 1744.55   108.4 1737.23   168.5 1729.02   184.8 1727.51
   191.5 1724.81   215.1 1696.21   225.1 1686.64   230.4 1683.07   235.2 1680.44
   241.4 1678.31   255.1 1679.07   262.1 1677.76   268.8 1676.25   274.4 1676.05
   285.7 1676.55   292.4 1678.71   299.1 1681.72   302.5 1682.42   329.4 1683.81
   332.7 1684.19   336.1 1685.42     364 1707.34   370.5 1709.68     410 1720.02
   443.7 1730.41   477.3 1744.85   494.1 1752.88   510.9 1761.87   521.4 1768.65
#Mann= 4 ,-1 , 0
       0      .1       0   262.1    .045       0   292.4      .1       0
  493.44     .04       0
Bank Sta=262.1,292.4
XS Rating Curve= 0 ,0
Exp/Cntr=0.3,0.1

Type RM Length L Ch R = 1 ,12556   ,194.9,193.4,191.3
XS GIS Cut Line= 2
2016199.65009222273896.6580961272016315.96167814274295.589592792
#Sta/Elev= 30
       0 1745.44      28 1739.09    89.6 1726.97   112.7 1721.61   139.2 1717.41
   147.7 1712.43   168.2 1695.88   185.2 1684.75   188.7 1681.37   192.1 1677.06
   195.5 1675.28   202.3  1674.5   221.2  1674.3   236.5 1675.55   246.8 1677.71
   253.6 1677.19   260.4 1677.68   267.3 1677.41   270.7 1677.96   274.1 1679.06
   277.5 1681.26   284.3 1688.22   287.8 1690.91     290 1691.55     298 1691.25
   308.3 1694.19     335 1697.86   369.8 1704.89   397.1 1711.44   415.5 1718.29
#Mann= 3 ,-1 , 0
       0      .1       0   195.5    .045       0   236.5      .1       0
Bank Sta=195.5,236.5
XS Rating Curve= 0 ,0
Exp/Cntr=0.3,0.1

Type RM Length L Ch R = 1 ,12362   ,213.2,206.7,201.9
XS GIS Cut Line= 2
2016004.41674581273961.118202114 2016142.3033955274346.242069736
#Sta/Elev= 30
       0 1733.08    15.9 1729.31    43.8 1723.62    85.9 1716.03    99.5 1713.97
   116.9 1712.46   120.4 1711.57   127.4 1708.79   139.8 1706.88   151.8 1703.05
   158.8 1699.97   176.2 1688.41   183.4 1682.84   193.6 1676.43   198.8 1674.32
   207.5 1672.58     218  1672.3   235.4 1672.42   250.1 1673.97   259.8 1674.29
   273.8 1676.91   277.2 1678.13   284.2 1682.02   291.2 1684.39   305.1 1687.98
   343.5 1695.84   371.3 1703.16     381 1706.51   394.4 1712.07   409.1 1719.04
#Mann= 3 ,-1 , 0
       0      .1       0   198.8    .045       0   250.1      .1       0
Bank Sta=198.8,250.1
XS Rating Curve= 0 ,0
Exp/Cntr=0.3,0.1

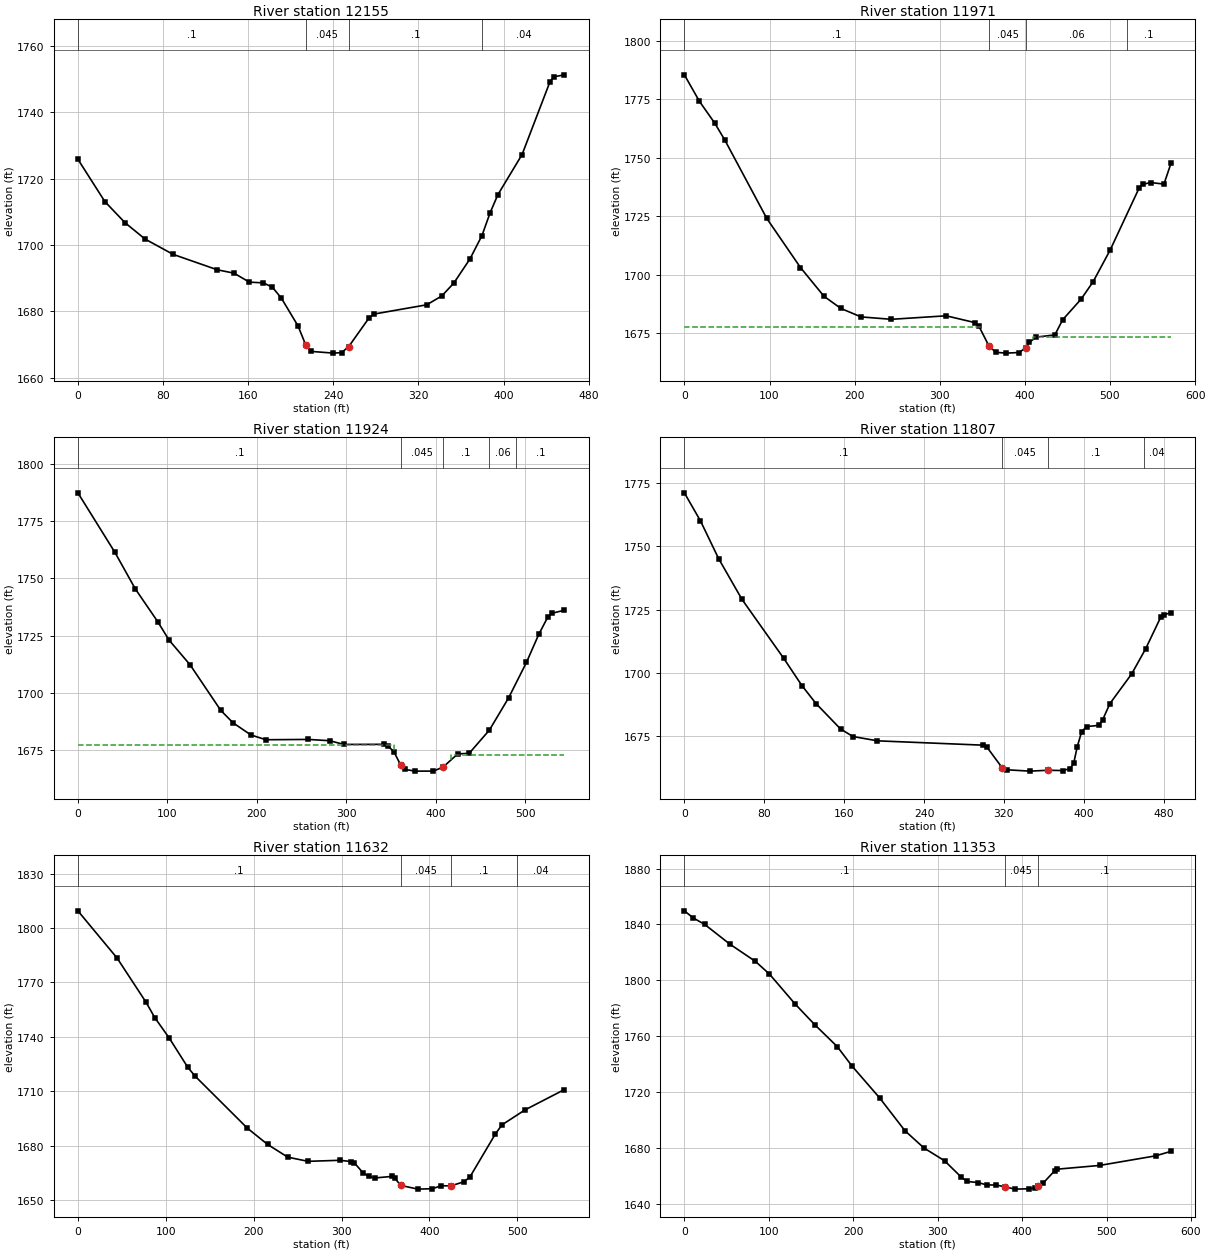
Type RM Length L Ch R = 1 ,12155   ,186.5,184.1,181.9
XS GIS Cut Line= 2
2015777.21344262274055.6316422822016002.16016755274453.685041326
#Sta/Elev= 30
       0 1725.89    25.4  1713.1    44.3 1706.74    63.1 1701.81    89.5 1697.18
     131 1692.53   146.7 1691.51   161.1 1688.81   174.4 1688.57   182.8 1687.27
   191.2 1683.98   206.9 1675.57   214.1 1669.86   218.9 1667.91   240.2 1667.38
   247.8 1667.53   254.5 1669.35   273.7 1678.04   277.9 1679.15   327.8 1681.96
     342 1684.64   353.3 1688.53   368.4 1695.78   379.7 1702.84   387.4 1709.76
   394.7 1715.21   417.4  1727.3   443.7 1749.33   447.6 1750.78   457.2 1751.36
#Mann= 4 ,-1 , 0
       0      .1       0   214.1    .045       0   254.5      .1       0
     380     .04       0
Bank Sta=214.1,254.5
XS Rating Curve= 0 ,0
Exp/Cntr=0.5,0.3

Type RM Length L Ch R = 1 ,11971   ,47.7,47.2,46.6
XS GIS Cut Line= 2
2015529.56214338274049.9504138072015848.66153134274524.145592694
#Sta/Elev= 30
       0 1785.49    17.7 1774.14    35.8 1764.73    47.6 1757.51    96.8 1724.01
   136.4 1702.98     164 1690.68   183.8 1685.49   207.5 1681.85   243.1 1680.82
   307.6 1682.32     342 1679.34   345.9 1677.95   357.8  1669.4   365.7 1666.71
   377.6 1666.34   392.7 1666.59   401.3 1668.56   405.3 1670.93   413.2 1673.19
   435.2 1674.14   444.5 1680.66     466 1689.43   480.2 1696.91   500.2 1710.47
   534.5 1737.23   539.2 1738.64   547.6 1739.39   563.4  1738.7   571.6 1747.54
#Mann= 4 ,-1 , 0
       0      .1       0   357.8    .045       0   401.3     .06       0
     520      .1       0
#XS Ineff= 2 , 0
          347.91 1677.69  409.05         1673.24
Permanent Ineff=
       F       F
Bank Sta=357.8,401.3
XS Rating Curve= 0 ,0
Exp/Cntr(USF)=0,0
Exp/Cntr=0.5,0.3

Type RM Length L Ch R = 1 ,11924   ,112.4,117,123.7
XS GIS Cut Line= 2
2015482.85675491274076.5667058632015794.15705291274522.677850115
#Sta/Elev= 30
       0 1787.36    41.5  1761.3    64.2  1745.4    89.5 1730.95   101.9 1723.05
   125.5 1712.21   159.8  1692.3   173.5 1686.88   193.5 1681.58   210.3 1679.49
   257.5 1679.63   281.5 1679.07   297.5 1677.44   342.3 1677.49     347  1676.7
   353.5 1674.13   361.1 1668.31   365.8 1666.51   377.2 1665.78   397.5 1665.79
   408.2 1667.51   424.7  1673.3   437.5 1673.55   460.1  1683.7   481.6 1697.79
   501.6 1713.32   515.3 1725.51   525.6 1733.23   529.6 1734.68     544 1736.09
#Mann= 5 ,-1 , 0
       0      .1       0   361.1    .045       0   408.2      .1       0
     460     .06       0     490      .1       0
#XS Ineff= 2 , 0
          353.52 1677.06  417.18         1672.71
Permanent Ineff=
       F       F
Bank Sta=361.1,408.2
XS Rating Curve= 0 ,0
Exp/Cntr(USF)=0,0
Exp/Cntr=0.5,0.3

Type RM Length L Ch R = 1 ,11807   ,160.3,174.9,186.2
XS GIS Cut Line= 2
2015446.18606108274122.2714256792015654.51939443274562.809620127
#Sta/Elev= 30
       0 1771.16    16.1 1760.09    34.3 1745.18    57.7 1729.08    99.6 1705.76
   117.7 1695.06   131.8 1687.98   156.4 1677.93   168.8 1674.94   193.4 1673.24
   299.2 1671.53   302.8 1670.88   318.41662.533   322.8 1661.81   345.8 1661.28
     3641661.615     379 1661.51   386.3 1662.27   389.9 1664.35   393.5 1670.97
   397.9 1676.87   402.8 1678.87   415.3 1679.35   418.9 1681.54   426.2 1687.95
     448 1699.68     462 1709.59     477    1722   480.6  1723.1   487.3 1723.78
#Mann= 4 ,-1 , 0
       0      .1       0   318.4    .045       0     364      .1       0
     460     .04       0
Bank Sta=318.4,364
XS Rating Curve= 0 ,0
Exp/Cntr(USF)=0,0
Exp/Cntr=0.3,0.1

Type RM Length L Ch R = 1 ,11632   ,267.9,279.5,286.6
XS GIS Cut Line= 2
2015395.39409798274079.1650390012015438.64199087274631.045759173
#Sta/Elev= 30
       0 1809.47    44.7 1783.37    77.6 1759.03    87.5 1750.58   103.9 1739.35
   125.1 1723.14   133.5 1718.25   192.8 1689.63   215.8 1680.67   238.8 1673.62
   261.9 1671.32   298.1 1671.89   311.2 1671.18   314.7 1670.41   324.4 1665.02
     331 1662.99   337.6 1662.14   357.3    1663   360.6 1662.09   367.2 1658.06
   386.9 1655.99   403.4 1656.22   413.3 1657.85   424.31657.777   439.6 1660.09
   446.2 1662.79     475 1686.38   482.5 1691.41   508.7 1699.67   553.6  1710.9
#Mann= 4 ,-1 , 0
       0      .1       0   367.2    .045       0   424.3      .1       0
     500     .04       0
Bank Sta=367.2,424.3
XS Rating Curve= 0 ,0
Exp/Cntr(USF)=0,0
Exp/Cntr=0.3,0.1

Type RM Length L Ch R = 1 ,11353   ,266.6,252.3,236.1
XS GIS Cut Line= 3
     2015229.269      274064.1182015175.06159728274341.799619478
2015118.73154383274629.665707285
#Sta/Elev= 30
       0 1849.75    10.6 1844.59    23.9  1840.1      54 1825.87    84.1  1813.6
   100.8 1804.48   131.4 1782.94   154.3 1768.38   181.1 1752.61   198.5 1738.75
   231.2 1715.98   261.3 1692.42   283.8 1680.12   308.1 1671.01   328.1 1659.18
   334.8 1656.22   348.2 1655.37   358.2 1653.69   369.1 1653.68   379.4 1652.41
   391.5 1650.72   408.4 1650.97   415.1 1651.57   418.51652.676   425.2 1655.24
   438.5 1663.83   441.8    1665   491.7 1667.66   558.2 1674.54   576.2 1677.73
#Mann= 3 ,-1 , 0
       0      .1       0   379.4    .045       0   418.5      .1       0
Bank Sta=379.4,418.5
XS Rating Curve= 0 ,0
Exp/Cntr=0.3,0.1

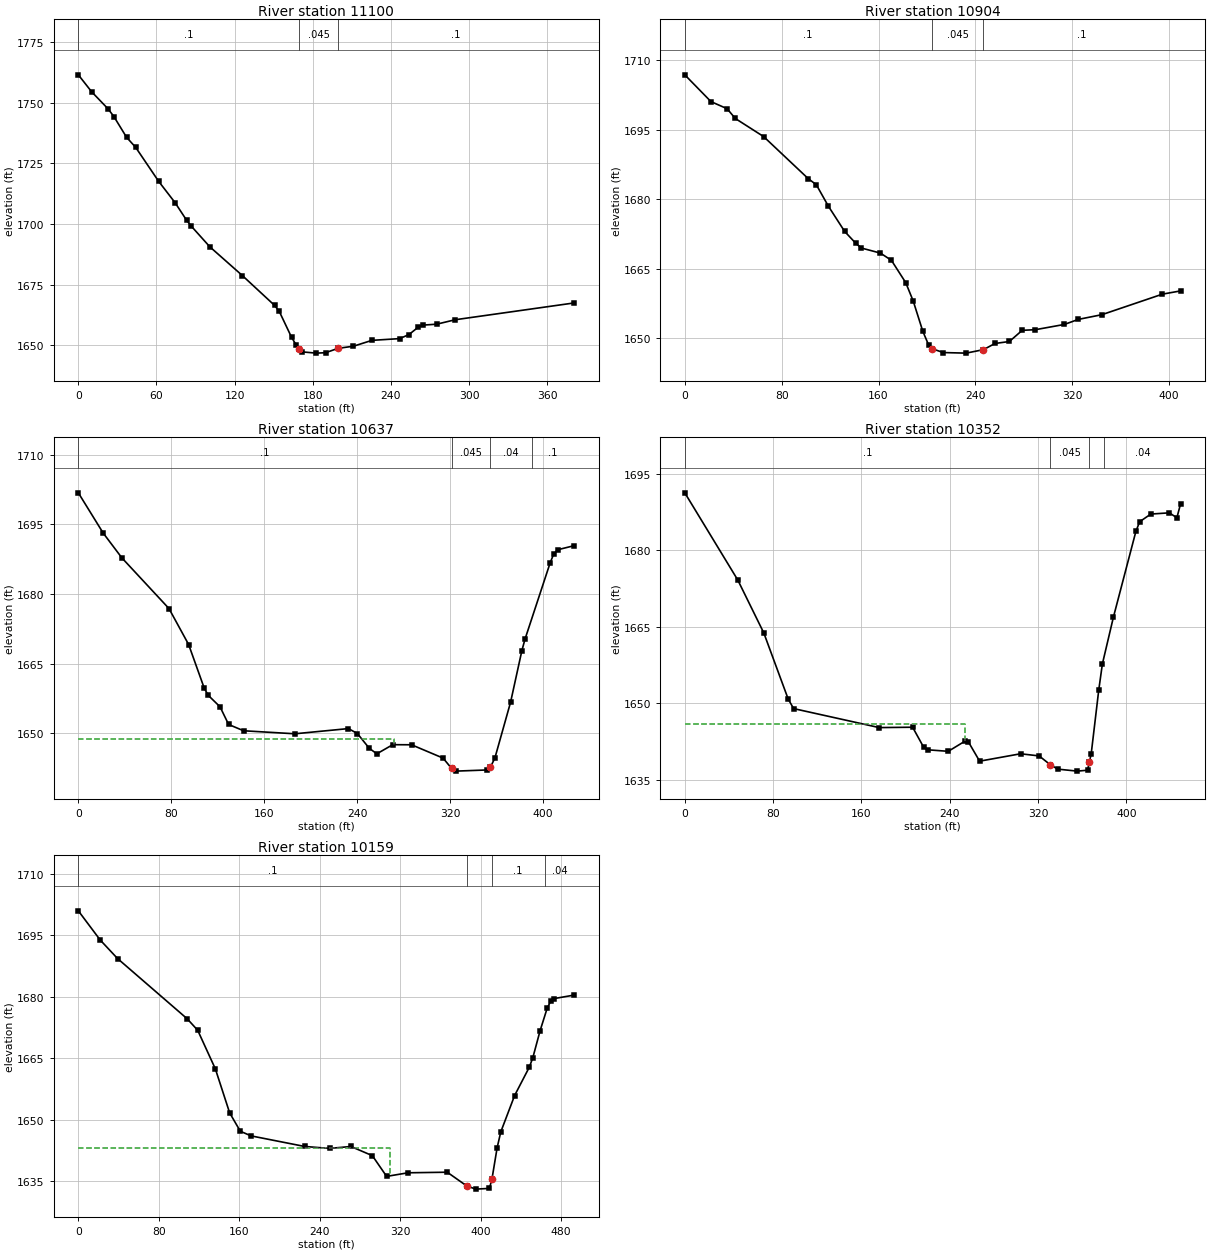
Type RM Length L Ch R = 1 ,11100   ,216.5,196.4,180.1
XS GIS Cut Line= 2
2014835.49617379274276.5578512752014981.90486622274627.938713096
#Sta/Elev= 30
       0 1761.48    10.2 1754.51    22.8 1747.47    27.3 1744.29      37 1735.77
    44.1 1731.54    61.7 1717.57    74.3 1708.79    83.2 1701.51    86.6  1699.2
     101  1690.6   125.9 1678.79   150.7 1666.46   154.3 1663.98   163.7 1653.35
   167.1 1650.29   169.6 1648.53   172.1 1647.31   182.7 1646.81   189.8 1646.98
   199.51648.794   211.2 1649.65   225.4 1652.07   246.7 1652.79   253.8 1654.44
   260.9 1657.47   264.5 1658.35   275.1 1658.73   289.4 1660.57   380.7 1667.49
#Mann= 3 ,-1 , 0
       0      .1       0   169.6    .045       0   199.5      .1       0
Bank Sta=169.6,199.5
XS Rating Curve= 0 ,0
Exp/Cntr(USF)=0,0
Exp/Cntr=0.3,0.1

Type RM Length L Ch R = 1 ,10904   ,243.4,267.5,287.6
XS GIS Cut Line= 3
2014649.11145695274371.5020543722014677.29882102274514.552927053
2014901.38836542274653.375695122
#Sta/Elev= 30
       0 1706.87    21.6 1701.09    34.9 1699.56    41.7 1697.45    65.1 1693.54
   101.9 1684.47   108.6 1683.15   118.6  1678.5     132 1673.07     141 1670.56
   145.8 1669.49   161.5  1668.4   170.6 1666.84   182.4 1662.03   188.6 1658.06
   196.5 1651.54   201.4 1648.52   203.7  1647.8   213.5 1646.93   232.3 1646.81
   246.6 1647.56   256.1 1648.89     268 1649.32   278.6 1651.73   289.5 1651.87
   313.4    1653   324.9 1654.09   344.3  1655.1   394.4 1659.54   409.4 1660.24
#Mann= 3 ,-1 , 0
       0      .1       0   203.7    .045       0   246.6      .1       0
Bank Sta=203.7,246.6
XS Rating Curve= 0 ,0
Exp/Cntr(USF)=0,0
Exp/Cntr=0.3,0.1

Type RM Length L Ch R = 1 ,10637   ,269,284.4,294.8
XS GIS Cut Line= 2
 2014479.9872725274398.9847343462014581.46178317274813.338986247
#Sta/Elev= 30
       0  1701.8    21.4 1693.12    37.5 1687.77      78 1676.85    94.9  1669.1
   108.4 1659.64   111.8 1658.14   121.9 1655.68   129.3 1651.87   142.2 1650.51
   186.3 1649.86   232.4 1650.98   240.1 1649.91   250.3 1646.74   256.8 1645.54
   270.5 1647.51   286.7 1647.49   313.8 1644.62   321.2 1642.38   324.6 1641.81
   351.6 1642.06   354.5 1642.63   358.4 1644.64   371.9 1656.67   381.6 1667.77
   384.3 1670.25     406 1686.75     409  1688.6   412.4 1689.53   426.6 1690.41
#Mann= 4 ,-1 , 0
       0      .1       0   321.2    .045       0   354.5     .04       0
     390      .1       0
#XS Ineff= 2 , 0
          271.18 1648.79
Permanent Ineff=
       F       F
Bank Sta=321.2,354.5
XS Rating Curve= 0 ,0
Exp/Cntr(USF)=0,0
Exp/Cntr=0.3,0.1

Type RM Length L Ch R = 1 ,10352   ,190.2,193.2,196.9
XS GIS Cut Line= 2
2014360.81941432274405.0617763272014257.76300206274842.255679278
#Sta/Elev= 30
       0 1691.27      48 1674.19    71.6 1663.81    93.7 1650.85    98.6    1649
   176.1 1645.28   206.4 1645.35   216.5 1641.39   219.9 1640.93   238.7 1640.63
   253.6 1642.59     257 1642.45   267.1  1638.7   304.2 1640.15     321 1639.73
   331.2 1637.99   337.9 1637.14   355.6 1636.75   364.9 1636.93   366.5 1638.53
   368.2 1640.16     375  1652.6   378.3 1657.73   388.3 1666.91   408.7 1683.74
   412.1 1685.61   422.2 1687.11     439 1687.35   445.8 1686.38   449.2 1689.15
#Mann= 4 ,-1 , 0
       0      .1       0   331.2    .045       0   366.5      .1       0
     380     .04       0
#XS Ineff= 2 , 0
          253.52 1645.92
Permanent Ineff=
       F       F
Bank Sta=331.2,366.5
XS Rating Curve= 0 ,0
Exp/Cntr=0.3,0.1

Type RM Length L Ch R = 1 ,10159   ,196.9,188.8,175.5
XS GIS Cut Line= 3
2014156.54443702274336.0490481772014195.99957945 274453.24541019
2014055.44282244274794.861675149
#Sta/Elev= 30
       0 1700.95    21.7 1693.84      39  1689.3   108.3 1674.58   118.7 1671.79
   136.3 1662.34   150.5 1651.61   161.1 1647.13   171.8    1646     225 1643.42
   249.8 1642.94   271.1 1643.41   292.4 1641.17   306.6 1636.11   327.9 1636.99
   366.9 1637.13   386.2 1633.79   395.3    1633   408.8 1633.18   411.3 1635.38
   416.5 1643.11   420.1 1646.95   433.9 1655.86   448.5 1662.78     452 1665.09
   459.2 1671.66   466.2 1677.12   469.8 1678.92   473.3 1679.53   493.1 1680.38
#Mann= 4 ,-1 , 0
       0      .1       0   386.2    .045       0   411.3      .1       0
  463.66     .04       0
#XS Ineff= 2 , 0
             310    1643
Permanent Ineff=
       F       F
Bank Sta=386.2,411.3
XS Rating Curve= 0 ,0
Exp/Cntr=0.3,0.1