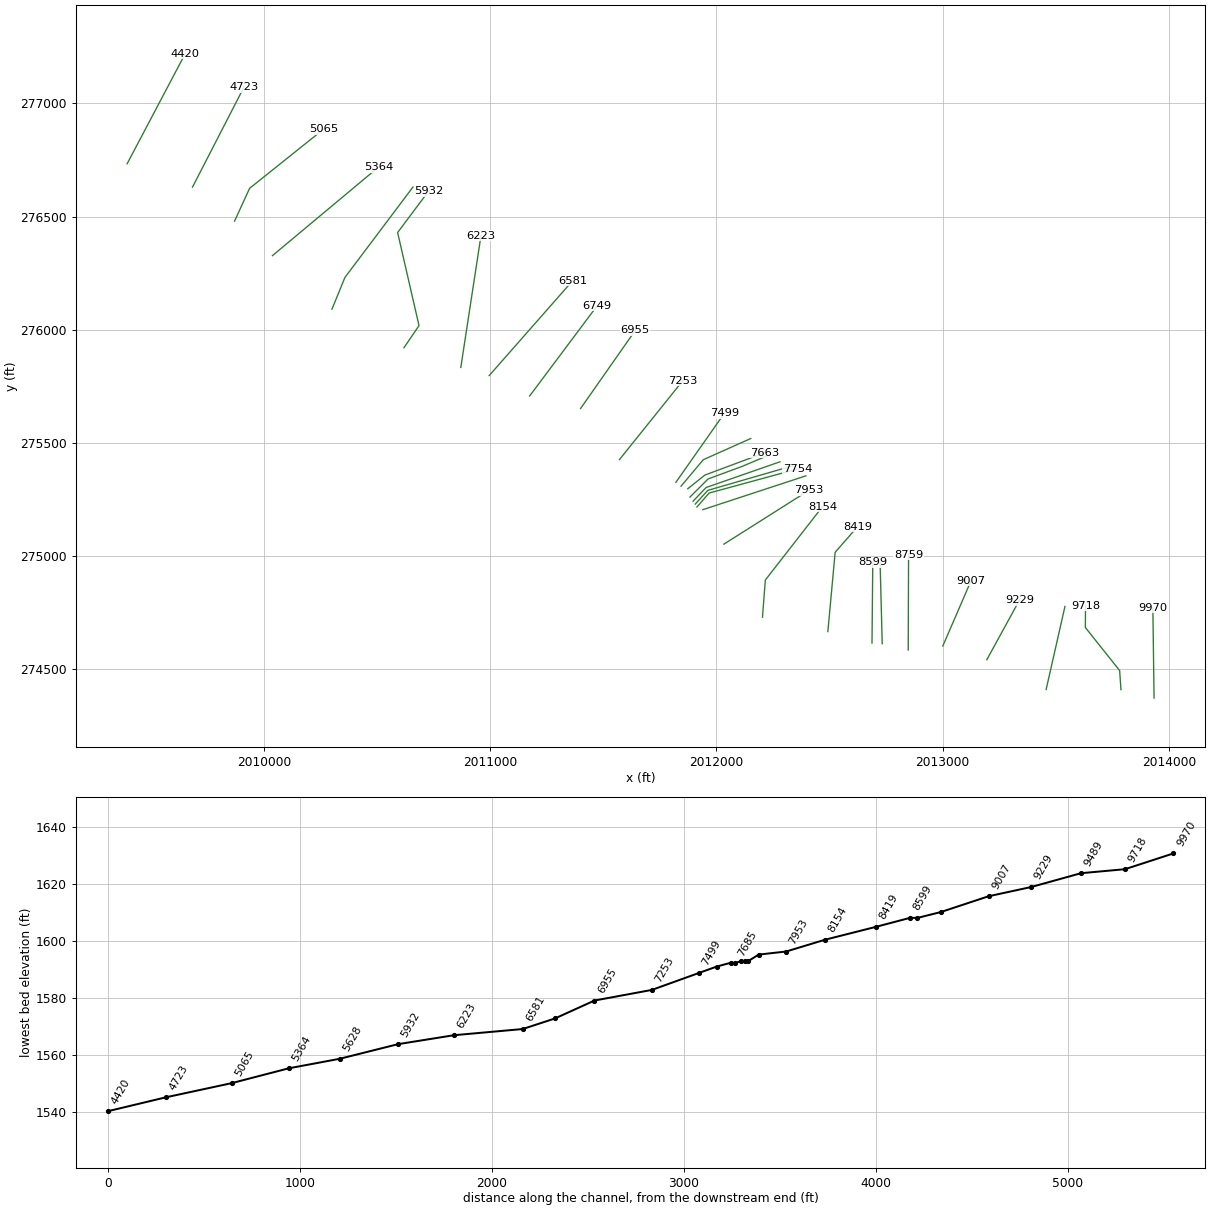
HEC-RAS study LAURELCK_A.prj: LAURELCK_A

--- LAURELCK_A.g01 (geometry) --- (continued)

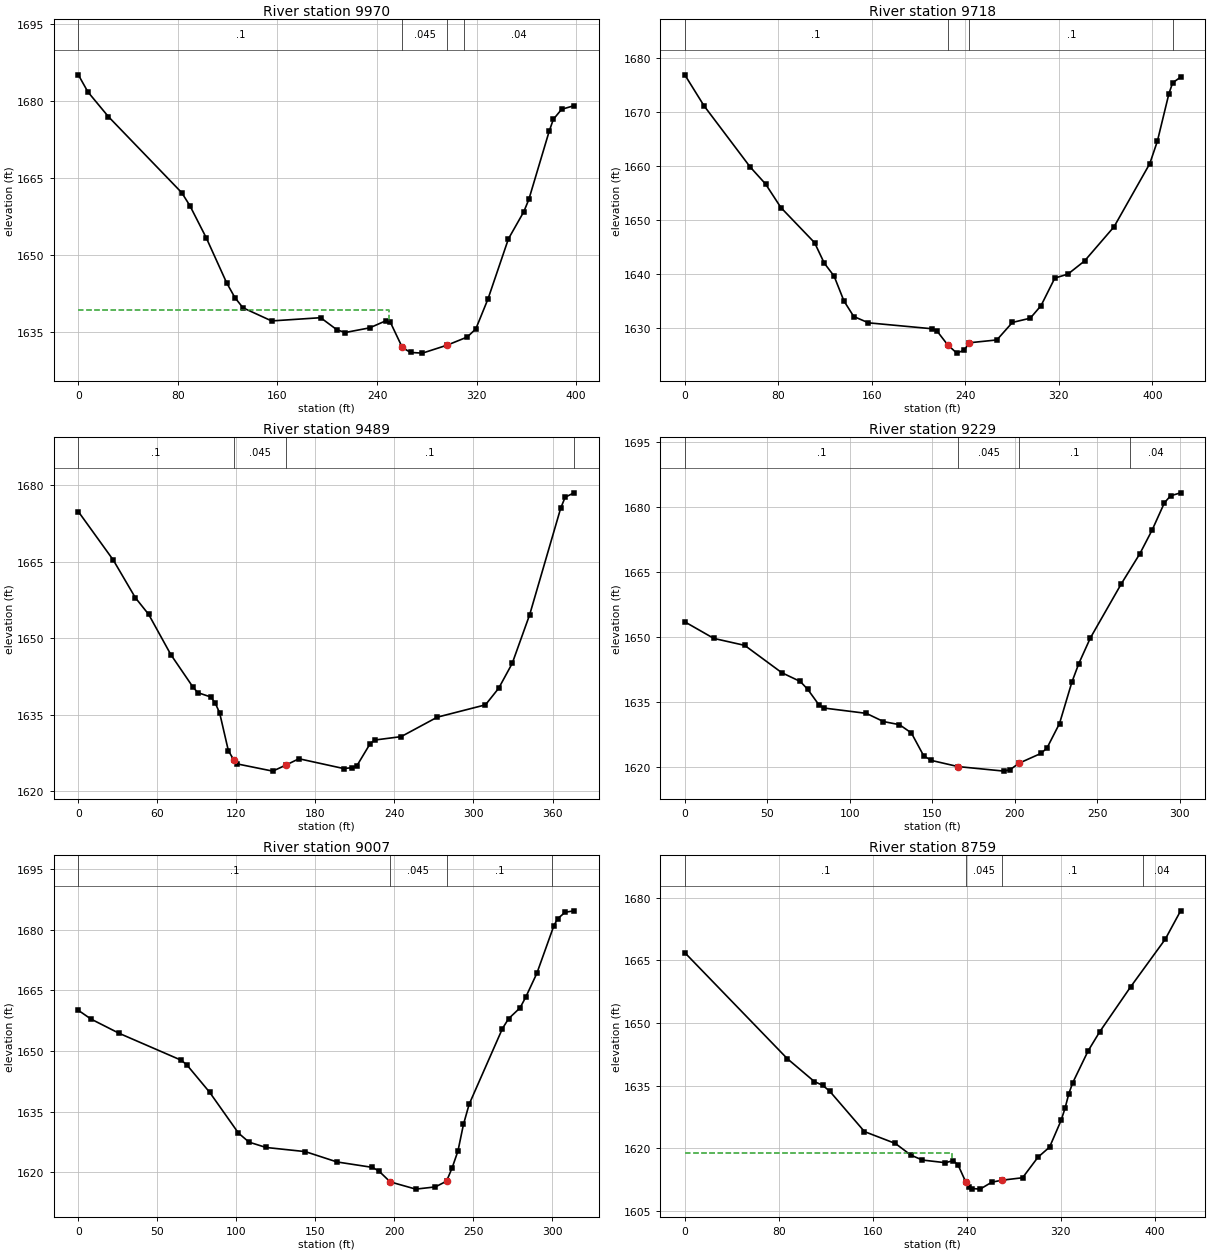
Type RM Length L Ch R = 1 ,9970    ,237.7,252.5,265.3
XS GIS Cut Line= 2
2013934.50215898274371.9492952542013929.19588507274770.291465926
#Sta/Elev= 30
       0 1685.16     7.7 1681.82    24.1 1677.02    83.1 1662.17    89.7 1659.61
   102.8 1653.36   119.2 1644.58   125.8 1641.71   132.3 1639.72   155.3 1637.16
   194.7 1637.79   207.8 1635.43   214.4  1634.9   234.1 1635.81   247.2  1637.2
   250.5 1637.01   260.3 1631.99   266.9 1631.01   276.5 1630.88   296.3 1632.43
   312.5 1634.02   319.4 1635.61   329.2 1641.47   345.6 1653.18   357.9 1658.44
     362 1660.87   378.4 1674.21   381.7 1676.49   388.3 1678.43   398.4 1679.15
#Mann= 4 ,-1 , 0
       0      .1       0   260.3    .045       0   296.3      .1       0
     310     .04       0
#XS Ineff= 2 , 0
           249.5 1639.29
Permanent Ineff=
       F       F
Bank Sta=260.3,296.3
XS Rating Curve= 0 ,0
Exp/Cntr=0.3,0.1

Type RM Length L Ch R = 1 ,9718    ,255.6,228.7,210.3
XS GIS Cut Line= 4
2013788.21496215274409.1347618762013782.35001165274493.412403997
2013630.84292974274683.6771115022013631.50615692274780.031407427
#Sta/Elev= 30
       0 1676.86    16.4 1671.14    55.9  1659.8    69.1 1656.64    82.2 1652.28
     111 1645.78   119.3 1641.99   127.7 1639.59   136.1    1635   144.5 1632.11
   157.1 1630.94   211.6 1629.84   215.8  1629.4   224.8 1626.88   232.6 1625.33
   238.9 1625.87   243.5 1627.25   266.9 1627.77   280.2 1631.01   295.5  1631.8
   304.7 1634.12   316.5 1639.23   327.7 1639.96   341.9 1642.39   367.2 1648.74
   397.7 1660.41   404.2 1664.56   414.1 1673.39   417.3 1675.39   424.1 1676.43
#Mann= 4 ,-1 , 0
       0      .1       0   224.8    .045       0   243.5      .1       0
   417.7     .04       0
Bank Sta=224.8,243.5
XS Rating Curve= 0 ,0
Exp/Cntr=0.3,0.1

Type RM Length L Ch R = 1 ,9489    ,271.4,259.6,254.7
XS GIS Cut Line= 2
2013457.49064068274409.554995874 2013540.6433647 274776.69541295
#Sta/Elev= 30
       0 1674.87    26.5 1665.37    43.3 1657.96    53.4 1654.69    70.2 1646.81
      87 1640.44    90.7 1639.33   100.5 1638.49   103.9 1637.31   107.3 1635.34
   113.9 1627.95   118.2 1626.05   120.7 1625.34   147.6 1623.93   157.7 1625.13
   167.5 1626.36   201.4 1624.44   208.1 1624.61   211.5 1624.99   221.6 1629.34
     225 1630.03   245.1  1630.7   272.5 1634.52   309.1 1636.94   319.1 1640.18
   329.4 1645.07   342.7 1654.66   366.2 1675.52   369.6 1677.69   376.4 1678.55
#Mann= 4 ,-1 , 0
       0      .1       0   118.2    .045       0   157.7      .1       0
  376.44     .04       0
Bank Sta=118.2,157.7
XS Rating Curve= 0 ,0
Exp/Cntr(USF)=0,0
Exp/Cntr=0.3,0.1

Type RM Length L Ch R = 1 ,9229    ,219.4,222.3,224.5
XS GIS Cut Line= 2
2013195.34815478274541.3309229242013339.80839567274804.882777025
#Sta/Elev= 30
       0 1653.46    17.6 1649.64    36.3 1648.04    58.8 1641.74      70 1639.72
    74.5 1637.91    81.2 1634.39    84.2 1633.61     110 1632.38   120.4 1630.49
   130.1 1629.77   137.3 1627.87   144.8 1622.59   149.4 1621.54   165.61620.117
   193.5 1619.07   197.2 1619.42   202.6  1620.9   215.9 1623.16   219.5 1624.39
   227.1 1630.04   234.6 1639.58   238.8 1643.86   245.8 1649.75   264.5 1662.19
   275.8 1669.16   283.3 1674.66   290.7  1680.9   294.4 1682.49   300.5 1683.18
#Mann= 4 ,-1 , 0
       0      .1       0   165.6    .045       0   202.6      .1       0
     270     .04       0
Bank Sta=165.6,202.6
XS Rating Curve= 0 ,0
Exp/Cntr(USF)=0,0
Exp/Cntr=0.3,0.1

Type RM Length L Ch R = 1 ,9007    ,236.2,248.4,257.9
XS GIS Cut Line= 2
2013000.85534267274601.933755685 2013125.5844287274890.149553351
#Sta/Elev= 30
       0 1660.04       8 1657.88    25.9 1654.34    65.2 1647.69    68.8 1646.51
    83.1  1639.8   101.4 1629.68   108.1 1627.44   118.9 1626.12   143.7  1625.1
   163.8 1622.54   186.2  1621.2   190.3 1620.31   197.5 1617.61   213.7 1615.82
   226.1 1616.37   233.2 1617.79   236.8 1621.16   240.4 1625.24   243.9 1631.83
   247.5 1636.81   268.6 1655.54   272.5 1657.98   279.7 1660.63   283.3 1663.26
   290.4 1669.21   301.1  1680.9   303.5 1682.67   308.3 1684.29     314 1684.64
#Mann= 4 ,-1 , 0
       0      .1       0   197.5    .045       0   233.2      .1       0
     300     .04       0
Bank Sta=197.5,233.2
XS Rating Curve= 0 ,0
Exp/Cntr(USF)=0,0
Exp/Cntr=0.3,0.1

Type RM Length L Ch R = 1 ,8759    ,121.3,122.3,123
XS GIS Cut Line= 2
2012847.97144612274584.3161609332012849.49452408275006.208757815
#Sta/Elev= 30
       0 1666.84    87.3 1641.46   110.3 1635.99   117.3 1635.12   123.4 1633.67
   152.9 1624.03   179.2 1621.19   192.3 1618.42   202.1 1617.23   221.8 1616.59
   228.4 1617.09   232.5 1616.06   239.1 1611.97   241.5 1610.89   244.8 1610.41
   251.3 1610.27   261.2 1611.93     270 1612.41   287.4 1612.99   300.5  1617.9
   310.4 1620.33   320.2 1626.72   323.5 1629.57   326.8 1633.14   330.1 1635.73
   343.2 1643.35     353 1647.89   379.3 1658.64   408.8 1670.05   421.9 1676.85
#Mann= 4 ,-1 , 0
       0      .1       0   239.1    .045       0     270      .1       0
     390     .04       0
#XS Ineff= 2 , 0
          227.72 1618.96
Permanent Ineff=
       F       F
Bank Sta=239.1,270
XS Rating Curve= 0 ,0
Exp/Cntr=0.5,0.3

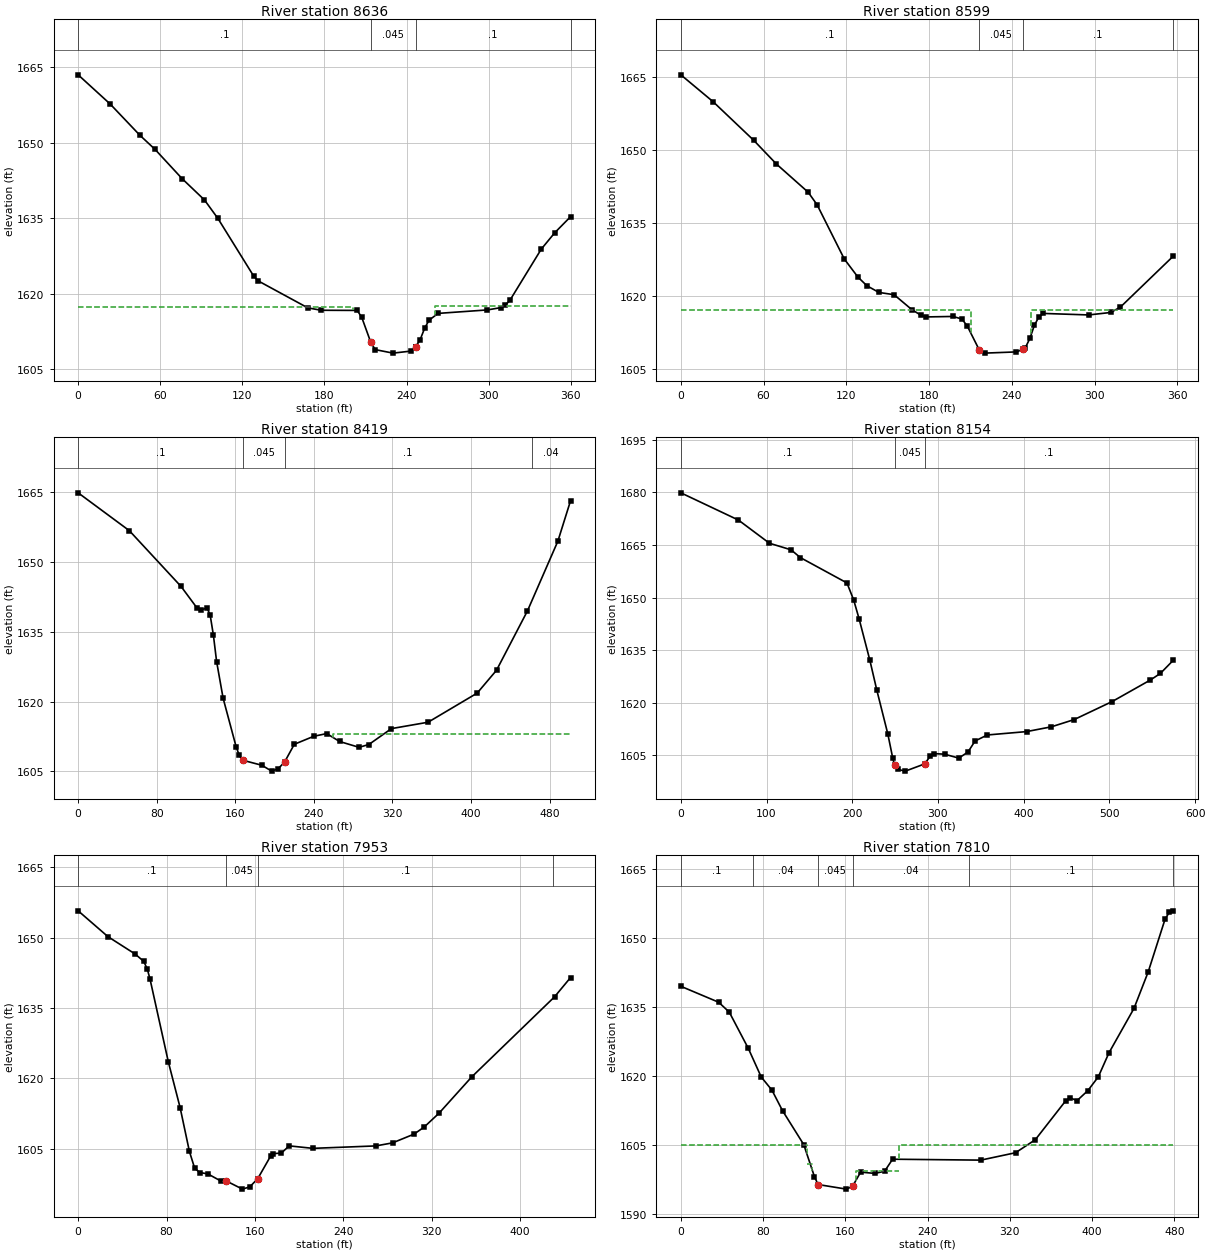
Type RM Length L Ch R = 1 ,8636    ,38.4,37.2,36.3
XS GIS Cut Line= 2
2012733.10265295274612.1452100692012723.64985322274971.804541372
#Sta/Elev= 30
       0 1663.47    23.4 1657.67    45.1 1651.47    56.2 1648.66    75.9 1642.87
    92.3 1638.62   102.1 1634.96   128.4 1623.44   131.7 1622.53   167.8  1617.2
   177.6 1616.72   203.9 1616.69   207.2 1615.33   213.7 1610.45     217 1608.91
   230.1 1608.21   243.3 1608.62   246.6  1609.4   246.6 1609.44   249.9 1610.89
   253.2 1613.17   256.4 1614.75     263  1616.1   299.1 1616.79   308.9 1617.25
   312.2 1617.76   315.5  1618.7   338.4 1628.86   348.3 1632.13   359.8  1635.3
#Mann= 4 ,-1 , 0
       0      .1       0   213.7    .045       0   246.6      .1       0
  359.78     .04       0
#XS Ineff= 2 , 0
           200.6  1617.3   260.6          1617.5
Permanent Ineff=
       F       F
Bank Sta=213.7,246.6
XS Rating Curve= 0 ,0
Exp/Cntr(USF)=0,0
Exp/Cntr=0.5,0.3

Type RM Length L Ch R = 1 ,8599    ,183.1,180.4,178.2
XS GIS Cut Line= 2
2012687.92940156274615.4171227912012691.30930206 274972.40746718
#Sta/Elev= 30
       0 1665.46    23.4 1659.93    52.9 1651.98    69.3 1647.12    92.3 1641.33
    98.8 1638.74   118.5  1627.6   128.4 1623.88   134.9  1622.1   143.6 1620.73
   154.6 1620.26   167.7 1617.14   174.3 1616.01   177.6 1615.69   197.3 1615.79
   203.8 1615.26   207.7  1613.8   216.5 1608.83   220.2 1608.25   243.2  1608.5
   248.21609.034   249.8 1609.38   253.1  1611.3   256.3 1613.95   259.6  1615.7
   262.9 1616.41   295.7  1616.1   311.7 1616.61   318.7 1617.71     357 1628.18
#Mann= 4 ,-1 , 0
       0      .1       0   216.5    .045       0   248.2      .1       0
  357.01     .04       0
#XS Ineff= 2 , 0
           210.6  1617.1   254.2          1617.2
Permanent Ineff=
       F       F
Bank Sta=216.5,248.2
XS Rating Curve= 0 ,0
Exp/Cntr(USF)=0,0
Exp/Cntr=0.5,0.3

Type RM Length L Ch R = 1 ,8419    ,283.2,264.2,248.7
XS GIS Cut Line= 3
2012492.80022047274665.676576379 2012525.0789171275016.108764601
2012623.52294239275128.629976176
#Sta/Elev= 30
       0 1664.86    52.1 1656.73   104.8 1644.73   121.3 1640.03   124.6 1639.63
   131.2 1640.14   134.4 1638.61   137.7 1634.28     141 1628.57   147.6 1620.72
   160.8 1610.32   164.1  1608.4   167.4 1607.39   187.1  1606.3     197 1605.04
   203.6 1605.54   210.2 1606.99   220.1 1610.81   239.9 1612.53   253.1 1613.11
   266.2 1611.41     286 1610.16     296 1610.76     319 1614.18   356.3 1615.55
   406.3 1621.81     426 1626.72   457.5 1639.48   488.5 1654.48   501.4 1663.17
#Mann= 4 ,-1 , 0
       0      .1       0   167.4    .045       0   210.2      .1       0
  461.92     .04       0
#XS Ineff= 2 , 0
                             260            1613
Permanent Ineff=
       F       F
Bank Sta=167.4,210.2
XS Rating Curve= 0 ,0
Exp/Cntr=0.3,0.1

Type RM Length L Ch R = 1 ,8154    ,209.8,201.4,191.4
XS GIS Cut Line= 3
2012203.81627391 274729.283538842012216.43571375  274893.3376555
2012468.36446116275216.812912889
#Sta/Elev= 30
       0 1679.89    67.2 1672.12   103.4 1665.51   128.6 1663.64   139.3 1661.44
   193.8 1654.19   201.7 1649.29   207.9 1644.02   220.5 1632.17   228.6 1623.66
   241.5 1611.11   247.2 1604.26   249.4 1602.22   253.1 1601.02   261.9 1600.53
   284.6  1602.6     291 1604.83   295.3 1605.53   307.7 1605.36   324.3 1604.24
     335 1605.98   343.3 1609.13   357.6 1610.84   403.3  1611.8   432.4 1613.17
   458.9 1615.23   503.3 1620.38   547.7  1626.5   559.4 1628.37   574.5 1632.13
#Mann= 3 ,-1 , 0
       0      .1       0   249.4    .045       0   284.6      .1       0
Bank Sta=249.4,284.6
XS Rating Curve= 0 ,0
Exp/Cntr=0.3,0.1

Type RM Length L Ch R = 1 ,7953    ,150.1,143,136.9
XS GIS Cut Line= 2
2012033.33463993275052.0681025992012409.99093626275290.380799641
#Sta/Elev= 30
       0 1655.72    26.9 1650.23    51.6 1646.51    59.4 1644.94    62.6 1643.27
      65 1641.22    81.6 1623.55    92.3 1613.77   100.7 1604.44   105.4 1600.91
   109.9 1599.95   117.3 1599.67   129.2 1598.13   133.81598.182   148.7 1596.41
   155.3 1596.89   162.5 1598.62   174.4 1603.53   176.7 1603.98   183.9 1604.09
     191 1605.63   212.4  1605.1   269.5 1605.62   284.6 1606.27     304 1608.13
   313.2 1609.64   326.6 1612.58   356.1 1620.29   431.2 1637.39   445.7  1641.5
#Mann= 4 ,-1 , 0
       0      .1       0   133.8    .045       0   162.5      .1       0
     430     .04       0
Bank Sta=133.8,162.5
XS Rating Curve= 0 ,0
Exp/Cntr=0.5,0.3

Type RM Length L Ch R = 1 ,7810    ,57.6,55.8,54.8
XS GIS Cut Line= 2
2011940.32123232275204.4593970322012395.41692888275353.873345603
#Sta/Elev= 30
       0 1639.46    36.8 1635.99    47.1 1633.84    65.6 1625.96    78.2 1619.72
    88.6 1616.87    98.9  1612.4   119.6    1605     130 1598.01   133.5 1596.33
   161.1 1595.33     167 1595.94   174.9 1599.03   188.7 1598.75   198.2 1599.22
     206 1601.84   291.8 1601.64   325.6 1603.25   344.8 1606.08   374.3 1614.53
   378.6 1615.21   385.4 1614.58   395.9 1616.76   406.1 1619.76   416.5    1625
   440.8 1634.65   454.6 1642.57   471.1 1654.11   475.3  1655.6     479 1655.88
#Mann= 6 ,-1 , 0
       0      .1       0      70     .04       0   133.5    .045       0
     167     .04       0     280      .1       0     479     .04       0
#XS Ineff= 4 ,-1
       0     123    1605     123     128  1600.7     170     212  1599.2
     212 478.995    1605
Permanent Ineff=
       F       F       F       F
Bank Sta=133.5,167
XS Rating Curve= 0 ,0
Exp/Cntr(USF)=0,0
Exp/Cntr=0.5,0.3

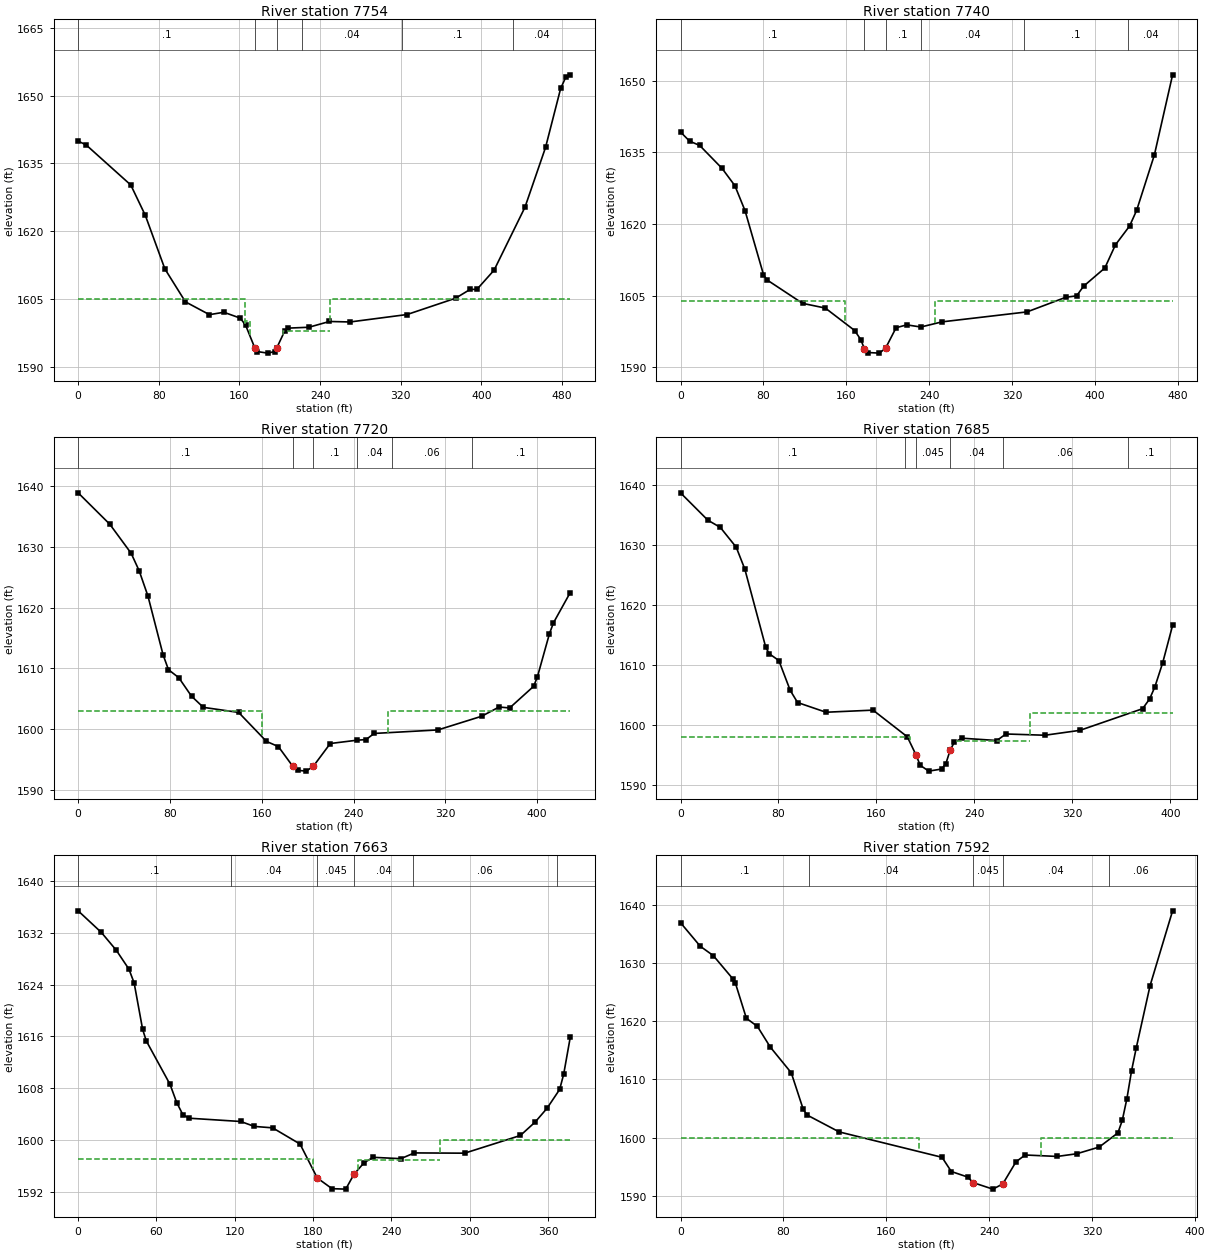
Type RM Length L Ch R = 1 ,7754    ,14.3,14.6,15
XS GIS Cut Line= 3
2011914.27659908 275216.110943482011967.73663572275277.795601147
2012359.77690445275384.715674436
#Sta/Elev= 30
       0 1639.94     7.9  1639.1    52.2 1630.22    66.6  1623.5      86 1611.64
   106.4 1604.34   130.2  1601.5   144.5 1602.03   160.8 1600.73   166.1 1599.15
   175.4 1594.02   177.8 1593.32     188 1592.98   194.8 1593.32   196.8 1594.05
     205 1597.95   208.4 1598.52   228.8 1598.71   249.2 1599.99   269.6 1599.88
   326.2 1601.53   374.3 1605.14   388.7 1607.09   395.5 1607.11   412.5 1611.36
   443.1 1625.29   463.5 1638.53   478.5  1651.6   483.5 1654.06     488 1654.62
#Mann= 6 ,-1 , 0
       0      .1       0   175.4    .045       0   196.8      .1       0
  221.63     .04       0  321.63      .1       0  431.63     .04       0
#XS Ineff= 4 ,-1
       0     165    1605     165     170    1600     203     250  1597.8
     250 487.986    1605
Permanent Ineff=
       F       F       F       F
Bank Sta=175.4,196.8
XS Rating Curve= 0 ,0
Exp/Cntr(USF)=0,0
Exp/Cntr=0.5,0.3

Type RM Length L Ch R = 1 ,7740    ,19.5,20.1,21.3
XS GIS Cut Line= 3
2011907.00538045275229.3209161952011962.36878541275289.815563569
2012339.92020072275398.921981155
#Sta/Elev= 30
       0 1639.24     8.8 1637.32    18.5 1636.43    40.1 1631.63    52.5 1628.01
    62.3 1622.78    80.1 1609.42    83.3 1608.34   117.8 1603.41   139.8 1602.42
   168.1 1597.73     174 1595.83   177.51593.914   180.8 1593.13   191.9    1593
   197.9 1594.01   208.1 1598.31   218.4 1598.91     232 1598.46   252.5 1599.54
   334.5 1601.62   372.1 1604.69   382.3 1604.97   389.1 1606.99   409.6  1610.8
   419.8 1615.63   433.5 1619.58   440.3 1622.85   457.4 1634.42     475 1651.19
#Mann= 6 ,-1 , 0
       0      .1       0   177.5    .045       0   197.9      .1       0
     232     .04       0     332      .1       0     432     .04       0
#XS Ineff= 2 , 0
             159    1604     246            1604
Permanent Ineff=
       F       F
Bank Sta=177.5,197.9
XS Rating Curve= 0 ,0
Exp/Cntr(USF)=0,0
Exp/Cntr=0.3,0.1

Type RM Length L Ch R = 1 ,7720    ,34.5,34.7,35.6
XS GIS Cut Line= 3
2011897.28302641275242.013989528 2011954.5368891275302.238571512
2012281.04594569 275415.93610073
#Sta/Elev= 30
       0 1638.95    27.6 1633.77    46.2 1628.98    53.2 1626.09    60.8 1621.95
      74 1612.26    78.7  1609.8    87.7 1608.48    98.8 1605.43   109.1 1603.59
   139.8 1602.76   164.1 1597.98   174.5 1597.12   186.91593.911   191.9  1593.2
   198.8 1593.08   204.91593.872   219.7 1597.63   243.1 1598.18   250.9 1598.28
   257.9 1599.29   313.5 1599.87   351.7 1602.13   366.8 1603.65     376 1603.49
   396.9 1607.06   400.2 1608.62   410.7 1615.74   414.2 1617.53   428.8 1622.51
#Mann= 6 ,-1 , 0
       0      .1       0   186.9    .045       0   204.9      .1       0
   243.1     .04       0   273.1     .06       0   343.1      .1       0
#XS Ineff= 2 , 0
             160    1603     270            1603
Permanent Ineff=
       F       F
Bank Sta=186.9,204.9
XS Rating Curve= 0 ,0
Exp/Cntr(USF)=0,0
Exp/Cntr=0.5,0.3

Type RM Length L Ch R = 1 ,7685    ,21.3,21.5,21.4
XS GIS Cut Line= 4
2011883.37862471275260.1584337952011963.23973581275340.019544885
2012115.32306919275396.2695448992012231.98973581275445.575100452
#Sta/Elev= 30
       0 1638.74    22.3 1634.18    32.5 1632.97    45.5 1629.66    52.5 1626.02
    69.6 1612.97    72.4 1611.89    80.3 1610.75    89.6 1605.76    95.6 1603.74
   118.8 1602.12   157.2 1602.47   185.2 1598.02   192.2 1595.04   195.7 1593.27
   202.7 1592.29   213.2 1592.64   216.7 1593.55   220.2  1595.8   223.7 1597.16
   230.2 1597.78   258.3  1597.4   265.7 1598.49   297.6 1598.28   326.2  1599.1
   377.3 1602.71     383 1604.32   387.3 1606.33   393.7 1610.36   401.8 1616.61
#Mann= 6 ,-1 , 0
       0      .1       0  182.94     .04       0   192.2    .045       0
   220.2     .04       0  262.94     .06       0  365.09      .1       0
#XS Ineff= 3 ,-1
       0   187.7 1598.03   224.7     285  1597.3     285  401.75    1602
Permanent Ineff=
       F       F       F
Bank Sta=192.2,220.2
XS Rating Curve= 0 ,0
Exp/Cntr(USF)=0,0
Exp/Cntr=0.5,0.3

Type RM Length L Ch R = 1 ,7663    ,70.3,71.6,72.8
XS GIS Cut Line= 3
2011873.65640253275296.9639893472011949.35084695275357.380656004
2012211.85084698275455.297322676
#Sta/Elev= 30
       0 1635.39    17.8 1632.05    29.2 1629.31    38.9 1626.39    42.9 1624.26
    49.4 1617.09    52.2 1615.31    70.4  1608.6    75.5  1605.8    80.2 1603.93
    84.9 1603.38   124.6 1602.87     135 1602.11     149 1601.89     170 1599.39
   183.2 1594.15   194.5  1592.5     205 1592.43   211.3 1594.71     219  1596.5
     226 1597.34   247.2 1597.13   257.6 1598.02   296.1 1597.98   338.8 1600.71
   350.1 1602.78   359.2  1604.9   368.9 1607.82     372 1610.19     377 1615.85
#Mann= 6 ,-1 , 0
       0      .1       0  116.85     .04       0   183.2    .045       0
   211.3     .04       0  256.85     .06       0  366.85      .1       0
#XS Ineff= 3 ,-1
       0   179.7  1597.1   214.5     277  1596.9     277  377.02    1600
Permanent Ineff=
       F       F       F
Bank Sta=183.2,211.3
XS Rating Curve= 0 ,0
Exp/Cntr(USF)=0,0
Exp/Cntr=0.5,0.3

Type RM Length L Ch R = 1 ,7592    ,78,92.6,104.3
XS GIS Cut Line= 3
2011843.97851458275308.234866425 2011942.2827706275425.263742649
 2012151.9985168275518.886843627
#Sta/Elev= 30
       0 1636.94    15.4 1632.88    25.5 1631.28    40.9 1627.23    42.7 1626.53
    51.2 1620.51    59.8  1619.1    69.8 1615.55    86.1 1611.13    95.4 1604.85
    98.4 1603.87   123.3 1600.97   203.3  1596.6   210.5 1594.16   223.2 1593.21
   227.6 1592.24   242.8 1591.13   250.5 1592.02   260.8 1595.83   267.9    1597
   292.8 1596.75     308 1597.21   325.5 1598.37     340  1600.8   343.4 1602.96
     347  1606.7   350.6 1611.47   354.2 1615.36     365 1626.12   382.5 1638.98
#Mann= 5 ,-1 , 0
       0      .1       0     100     .04       0   227.6    .045       0
   250.5     .04       0  332.84     .06       0
#XS Ineff= 2 , 0
             185    1600     280            1600
Permanent Ineff=
       F       F
Bank Sta=227.6,250.5
XS Rating Curve= 0 ,0
Exp/Cntr(USF)=0,0
Exp/Cntr=0.3,0.1

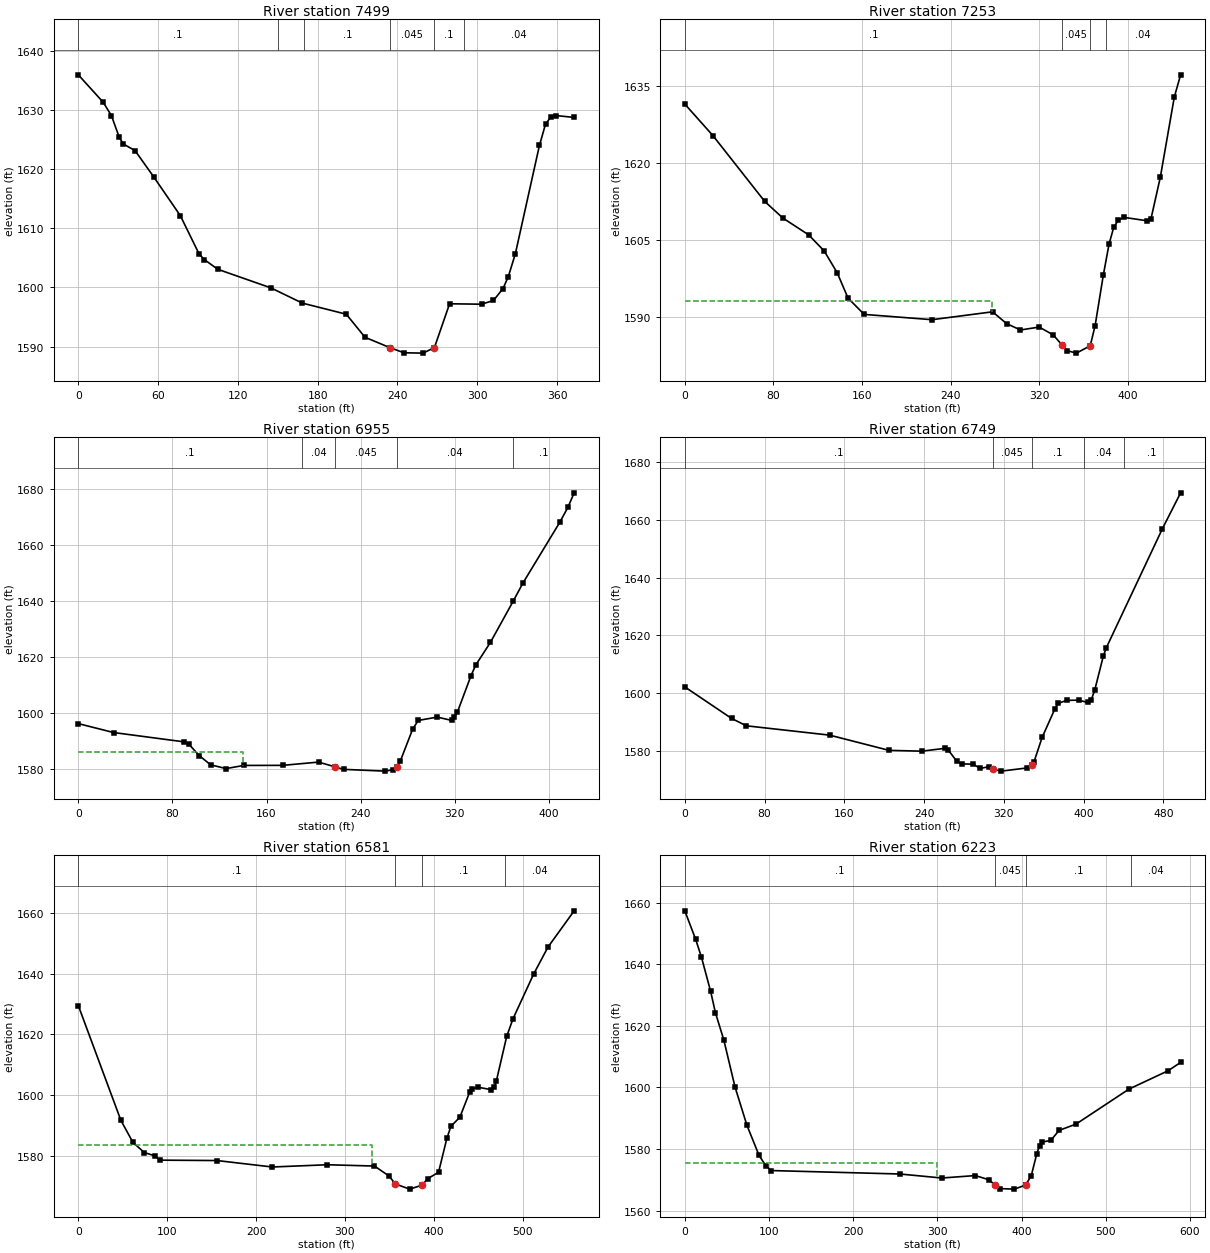
Type RM Length L Ch R = 1 ,7499    ,248.8,245.7,244
XS GIS Cut Line= 2
2011821.35188804275325.6292028942012035.70663221275630.807643683
#Sta/Elev= 30
       0 1635.92    18.7 1631.28    24.9 1629.02    30.7  1625.4    33.7 1624.25
    42.7  1623.1    56.6  1618.7    76.7 1612.12    90.8 1605.65    94.8 1604.68
   104.9 1603.05   144.8 1599.91   168.5 1597.33   201.5 1595.46   215.6 1591.56
   234.5 1589.79   244.9 1588.94   259.2 1588.88   267.8 1589.81   279.2 1597.22
   303.3 1597.15   312.2 1597.78   319.4 1599.79   323.4 1601.82   328.7  1605.7
   346.8    1624   351.4 1627.61   355.4 1628.79   359.1 1629.04   372.9 1628.72
#Mann= 6 ,-1 , 0
       0      .1       0     150     .04       0     170      .1       0
   234.5    .045       0   267.8      .1       0     290     .04       0
Bank Sta=234.5,267.8
XS Rating Curve= 0 ,0
Exp/Cntr=0.3,0.1

Type RM Length L Ch R = 1 ,7253    ,298.1,298.4,298.5
XS GIS Cut Line= 2
2011572.00580806275426.0663775382011852.33281704275775.132576454
#Sta/Elev= 30
       0 1631.55    25.4 1625.39    72.2 1612.53    88.6 1609.28   111.9    1606
   125.9 1602.85   137.6 1598.61   147.4 1593.65     162 1590.47   223.2 1589.44
   277.9 1590.98   290.5 1588.68   303.1 1587.43     320    1588   332.6 1586.48
     341 1584.42   345.3 1583.39   353.6 1582.91   366.1 1584.35   370.5 1588.29
   377.9 1598.15   383.1 1604.23   387.3 1607.47   391.5  1608.9   396.6 1609.42
   417.6 1608.75     421  1609.2   429.4  1617.3     442 1632.92   447.7 1637.26
#Mann= 4 ,-1 , 0
       0      .1       0     341    .045       0   366.1      .1       0
     380     .04       0
#XS Ineff= 2 , 0
          277.78 1593.04
Permanent Ineff=
       F       F
Bank Sta=341,366.1
XS Rating Curve= 0 ,0
Exp/Cntr(USF)=0,0
Exp/Cntr=0.3,0.1

Type RM Length L Ch R = 1 ,6955    ,206.9,206.1,205.1
XS GIS Cut Line= 2
 2011399.8521868275651.4061306672011641.79066996 275996.71497845
#Sta/Elev= 30
       0 1596.14      30 1592.96    89.6 1589.65    93.7 1588.91     103 1584.66
   112.5 1581.44   125.6  1580.1   140.7 1581.22   173.7 1581.25   204.3 1582.41
   218.5 1580.69   225.5 1579.82   260.9 1579.19   267.9 1579.72   270.9 1580.65
   273.8 1582.82   284.4 1594.29   289.1 1597.28   305.2 1598.47   317.4 1597.29
   319.7 1598.35   322.4 1600.32   333.9 1613.27   337.9 1617.03   350.4 1625.13
     370 1640.01     378 1646.27   409.3 1667.92   416.3 1673.32   421.6 1678.49
#Mann= 5 ,-1 , 0
       0      .1       0     190     .04       0   218.5    .045       0
   270.9     .04       0     370      .1       0
#XS Ineff= 2 , 0
          139.71 1586.07
Permanent Ineff=
       F       F
Bank Sta=218.5,270.9
XS Rating Curve= 0 ,0
Exp/Cntr=0.3,0.1

Type RM Length L Ch R = 1 ,6749    ,170.3,168.2,165.9
XS GIS Cut Line= 2
 2011174.9137445275706.9024391552011472.83042075276105.018028293
#Sta/Elev= 30
       0 1602.08    46.9 1591.15    61.8 1588.59   145.2 1585.36   204.8 1580.08
   237.6  1579.8   261.1 1580.79   264.1 1580.23   272.8 1576.26   277.5  1575.4
   289.2 1575.28   296.2 1573.83     305  1574.4   309.1 1573.53   317.3 1572.88
   343.1 1573.98   347.8 1574.84   350.1 1576.02   358.3 1584.55   371.2 1594.53
   374.7 1596.41   382.9 1597.41   395.2 1597.49     404 1596.68   407.5 1597.46
   411.1 1601.02   419.8 1612.93   422.8 1615.74     479 1656.98   497.2 1669.37
#Mann= 5 ,-1 , 0
       0      .1       0   309.1    .045       0   347.8      .1       0
     400     .04       0     440      .1       0
Bank Sta=309.1,347.8
XS Rating Curve= 0 ,0
Exp/Cntr=0.3,0.1

Type RM Length L Ch R = 1 ,6581    ,342.7,357.8,372.8
XS GIS Cut Line= 2
 2010996.1817445275797.0151962282011364.64522138276216.017523577
#Sta/Elev= 30
       0 1629.45    47.9 1591.75    61.4 1584.54    74.2  1581.2    86.5 1580.06
    91.6 1578.69   156.1 1578.56   218.3 1576.44   280.3 1577.18   333.3 1576.75
   349.9 1573.43   356.6 1570.89   372.9 1569.17   386.8 1570.47   393.1 1572.58
   405.4 1574.72   414.7 1585.81   419.3 1589.81   429.4  1592.8   440.3 1600.96
   442.6 1601.99   449.6 1602.66   464.1 1601.88   468.2  1602.6   470.5 1604.77
   482.1 1619.37   489.2 1625.15   512.3 1639.76   528.5 1648.67     558  1660.6
#Mann= 4 ,-1 , 0
       0      .1       0   356.6    .045       0   386.8      .1       0
     480     .04       0
#XS Ineff= 2 , 0
          330.25 1583.52
Permanent Ineff=
       F       F
Bank Sta=356.6,386.8
XS Rating Curve= 0 ,0
Exp/Cntr=0.3,0.1

Type RM Length L Ch R = 1 ,6223    ,279.3,290.8,300.7
XS GIS Cut Line= 2
 2010870.6512607275833.1312679662010959.79739765276415.266282774
#Sta/Elev= 30
       0 1657.35    12.9  1648.1    19.8 1642.29    30.7 1631.18    36.4 1624.25
    46.4 1615.37    59.6 1600.21    73.8 1587.72    88.2 1577.94    96.1 1574.66
   102.6 1573.03   255.5 1571.91   305.2 1570.61   345.1  1571.4   361.7    1570
   368.3  1568.3   374.9 1567.16   391.5    1567   404.8 1568.34   404.8 1568.35
   411.5 1571.35   418.1 1578.56   421.4 1581.11   424.7 1582.29   434.7 1582.82
   444.6 1586.08   464.6  1588.1   527.6 1599.48   574.1 1605.44   588.9 1608.14
#Mann= 4 ,-1 , 0
       0      .1       0   368.3    .045       0   404.8      .1       0
     530     .04       0
#XS Ineff= 2 , 0
             300 1575.45
Permanent Ineff=
       F       F
Bank Sta=368.3,404.8
XS Rating Curve= 0 ,0
Exp/Cntr(USF)=0,0
Exp/Cntr=0.3,0.1

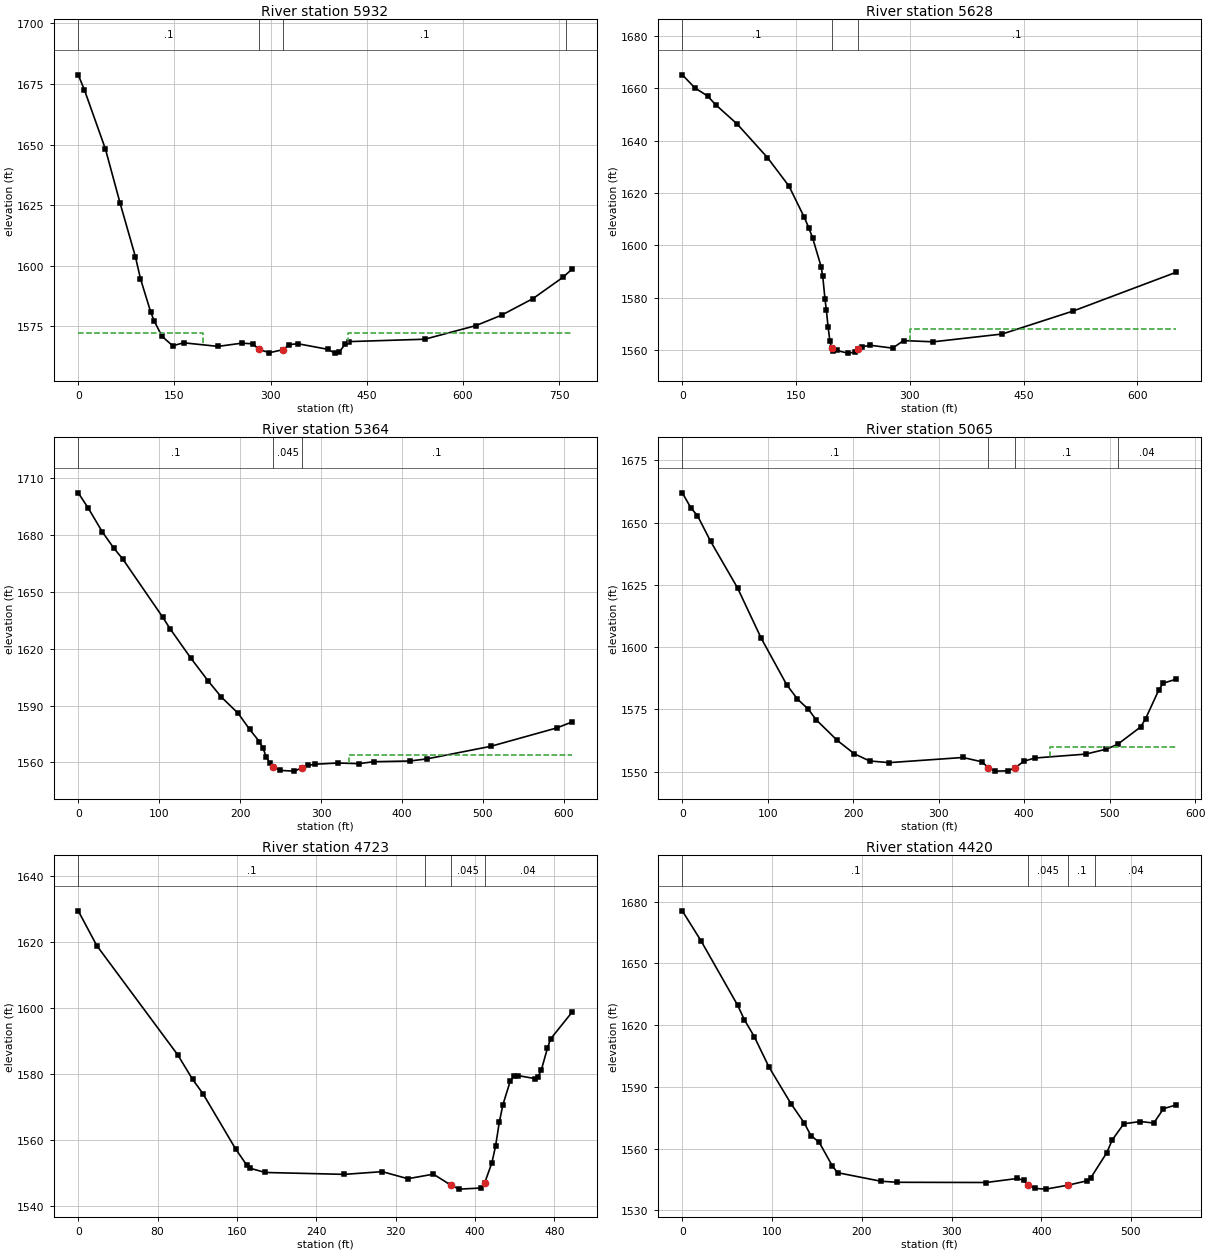
Type RM Length L Ch R = 1 ,5932    ,326.9,303.9,278.8
XS GIS Cut Line= 4
2010619.32359748275920.1293052352010685.91468774276017.867840931
2010591.39830157276429.2289307312010728.87668145276612.891453853
#Sta/Elev= 30
       0  1678.8     9.7 1672.54    42.5 1648.09    65.3 1625.78    89.1 1603.75
    97.1 1594.56   112.9 1580.95   118.2  1577.3   130.6 1570.81   147.4 1566.88
   164.2 1568.13   218.1 1566.64   255.1 1567.98     272 1567.71   281.6 1565.44
     298 1564.02   319.1 1565.28   329.2  1567.4   342.7 1567.73   389.8 1565.41
   399.9 1563.86   406.6 1564.15   416.7 1567.74   422.7 1568.62   540.3  1569.6
   620.2 1575.23   660.1 1579.53   709.3 1586.41   756.1 1595.22   769.8  1598.5
#Mann= 4 ,-1 , 0
       0      .1       0   281.6    .045       0   319.1      .1       0
  760.35     .06       0
#XS Ineff= 2 , 0
             195    1572     420            1572
Permanent Ineff=
       F       F
Bank Sta=281.6,319.1
XS Rating Curve= 0 ,0
Exp/Cntr(USF)=0,0
Exp/Cntr=0.3,0.1

Type RM Length L Ch R = 1 ,5628    ,271.8,264.8,259.1
XS GIS Cut Line= 3
2010301.40484401276090.9032302432010358.32948568276230.529709809
2010659.06344167276630.076251338
#Sta/Elev= 30
       0  1665.2    16.6  1660.2    33.3  1657.1    43.9 1653.78    72.3 1646.39
   112.2 1633.56   140.7 1622.61   160.8 1610.71   166.6 1606.78   171.7 1602.93
     183 1591.86   185.2 1588.05   188.1 1579.53   189.9  1575.3   192.2 1568.86
   194.5 1563.54   196.9 1560.61   199.2 1559.46   203.9 1559.73     218 1558.72
   227.3 1559.05   232.3  1560.2   236.7 1561.15   248.1 1561.72   277.4 1560.63
   291.7 1563.52   330.8 1563.05   421.8 1566.03   515.6 1574.85   650.9 1589.63
#Mann= 3 ,-1 , 0
       0      .1       0   196.9    .045       0   232.3      .1       0
#XS Ineff= 2 , 0
                             300            1568
Permanent Ineff=
       F       F
Bank Sta=196.9,232.3
XS Rating Curve= 0 ,0
Exp/Cntr(USF)=0,0
Exp/Cntr=0.3,0.1

Type RM Length L Ch R = 1 ,5364    ,299,298.6,296.8
XS GIS Cut Line= 2
2010038.26263252276327.1941956632010506.54836399276718.148338449
#Sta/Elev= 30
       0  1702.4    12.2 1694.46    29.7 1681.81    43.7 1673.35    55.4  1667.2
   104.3 1636.77   113.6 1630.54   139.2 1615.05   160.6    1603   176.9 1594.49
   197.5 1585.98   211.8 1577.45   223.9 1570.95   228.2  1567.6   232.4  1562.9
   236.8 1559.64     241  1557.4   249.6 1555.76   266.7 1555.38   276.7 1557.12
   283.6 1558.37   292.3 1559.02   320.9 1559.66   346.5 1559.33   365.4 1560.35
   409.4 1560.72   430.4 1561.81   509.6 1568.47   591.5 1578.21     610 1581.33
#Mann= 3 ,-1 , 0
       0      .1       0     241    .045       0   276.7      .1       0
#XS Ineff= 2 , 0
                             335            1564
Permanent Ineff=
       F       F
Bank Sta=241,276.7
XS Rating Curve= 0 ,0
Exp/Cntr(USF)=0,0
Exp/Cntr=0.3,0.1

Type RM Length L Ch R = 1 ,5065    ,330.3,342.1,351.9
XS GIS Cut Line= 3
2009870.71085704276479.7092733432009937.30194729276624.706002124
2010263.81309951276885.700113929
#Sta/Elev= 30
       0 1661.98    10.4 1655.72    17.7 1652.86      33 1642.57    64.6 1623.79
    92.4  1603.5   122.1  1584.9   134.5 1579.21   147.6 1574.94   156.7 1570.76
   181.3  1562.5   201.3 1557.11   219.1 1554.24     242 1553.56   328.3 1555.63
   350.6 1553.89   357.9 1551.56   366.1 1550.15     381 1550.27   389.1 1551.42
   399.7 1554.13   412.3 1555.41     472 1556.99   496.3 1558.99   509.4 1560.93
   536.3 1567.91   542.1 1571.24   557.3  1582.6   562.5 1585.46   577.6 1587.07
#Mann= 4 ,-1 , 0
       0      .1       0   357.9    .045       0   389.1      .1       0
  509.56     .04       0
#XS Ineff= 2 , 0
                             430            1560
Permanent Ineff=
       F       F
Bank Sta=357.9,389.1
XS Rating Curve= 0 ,0
Exp/Cntr(USF)=0,0
Exp/Cntr=0.3,0.1

Type RM Length L Ch R = 1 ,4723    ,303,302.5,301.8
XS GIS Cut Line= 2
2009684.90023423276630.0762513382009912.59880091277072.584786579
#Sta/Elev= 30
       0 1629.41    18.7 1618.89   100.3 1585.83   115.4 1578.36   125.7 1574.09
   158.7 1557.33   169.9 1552.45   173.6 1551.48   188.4 1550.22   268.4 1549.65
   306.5 1550.47   332.3 1548.33   358.1 1549.71   375.6  1546.4   383.9 1545.18
   406.1 1545.51   409.8 1547.09     417 1553.09   420.8 1558.24   424.5 1565.39
   428.2 1570.77   435.6 1577.89   439.3 1579.28     443 1579.56   460.8 1578.62
   463.3 1579.11   466.8 1581.12     473 1587.78   476.2 1590.62   497.7 1598.67
#Mann= 4 ,-1 , 0
       0      .1       0     350     .04       0   375.6    .045       0
   409.8     .04       0
Bank Sta=375.6,409.8
XS Rating Curve= 0 ,0
Exp/Cntr(USF)=0,0
Exp/Cntr=0.3,0.1

Type RM Length L Ch R = 1 ,4420    ,258.8,258.2,257.9
XS GIS Cut Line= 2
2009395.98082651276733.1850362482009652.67873894277219.729615045
#Sta/Elev= 30
       0  1675.5    20.9 1660.89    61.7  1629.6    69.1 1622.65    80.2 1614.39
    96.6  1599.6     121 1581.88   135.9 1572.42   143.3 1566.31   152.5 1563.07
     167 1551.71     173 1548.28   221.2 1544.13   239.7 1543.61   338.6 1543.51
   373.5 1545.48   380.6  1544.5   385.6 1542.32   392.9 1540.63     405 1540.29
   429.3 1542.17   451.2 1544.34   454.9 1545.57     473 1557.98   479.2 1564.26
     492 1572.04   510.5 1573.14   525.4 1572.39   536.2 1579.37   550.1 1581.17
#Mann= 4 ,-1 , 0
       0      .1       0   385.6    .045       0   429.3      .1       0
     460     .04       0
Bank Sta=385.6,429.3
XS Rating Curve= 0 ,0
Exp/Cntr(USF)=0,0
Exp/Cntr=0.3,0.1