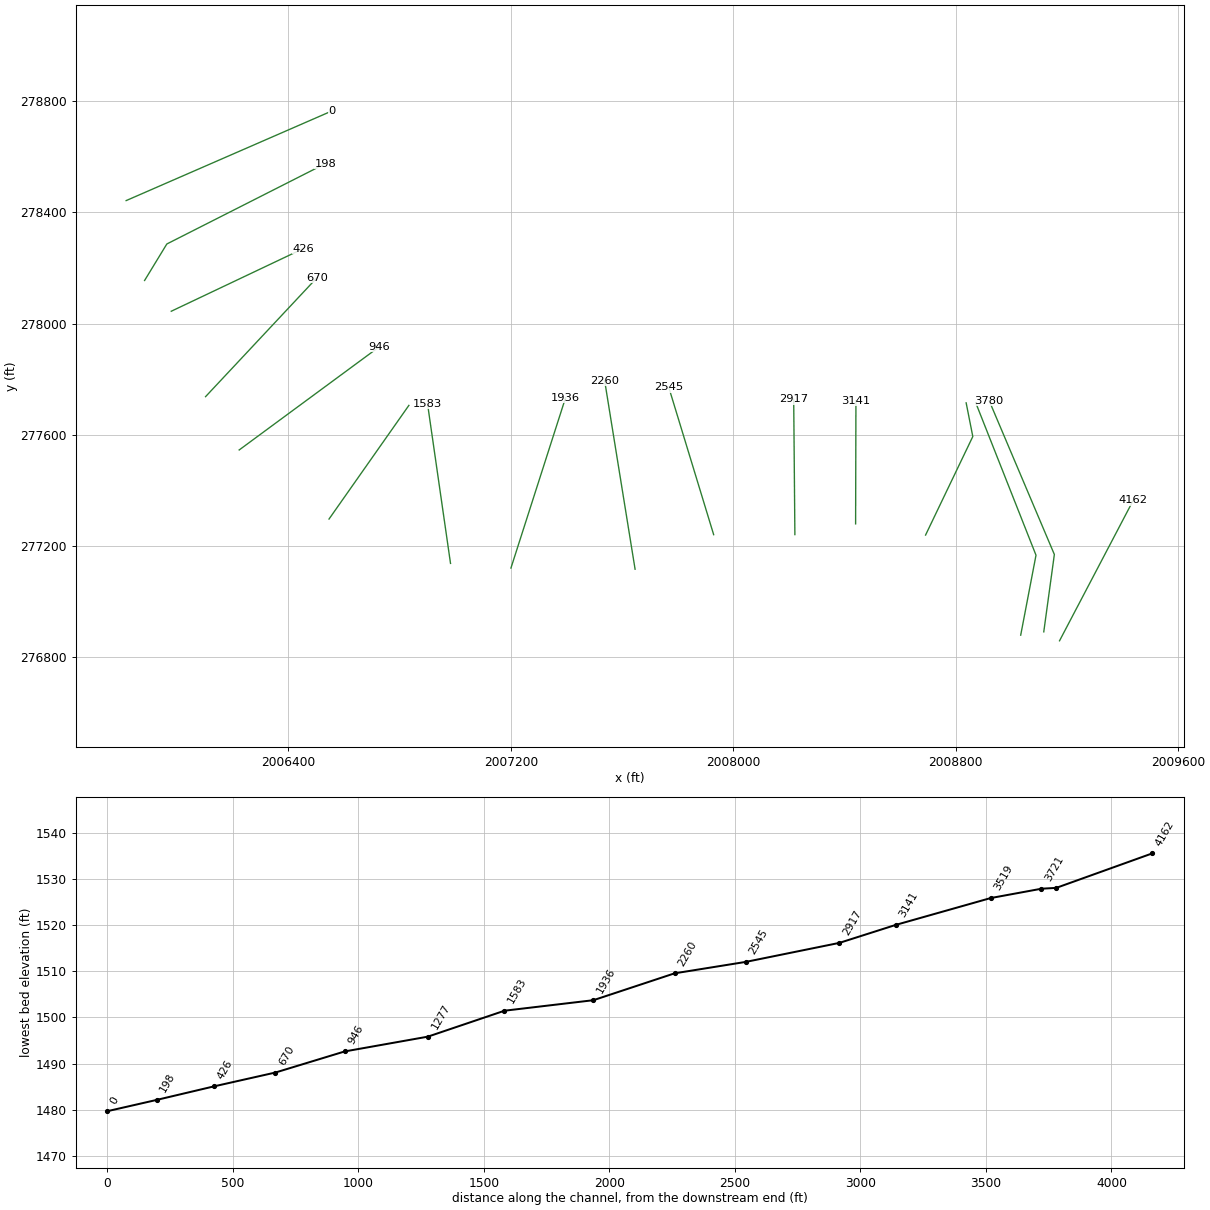
HEC-RAS study LAURELCK_A.prj: LAURELCK_A

--- LAURELCK_A.g01 (geometry) --- (continued)

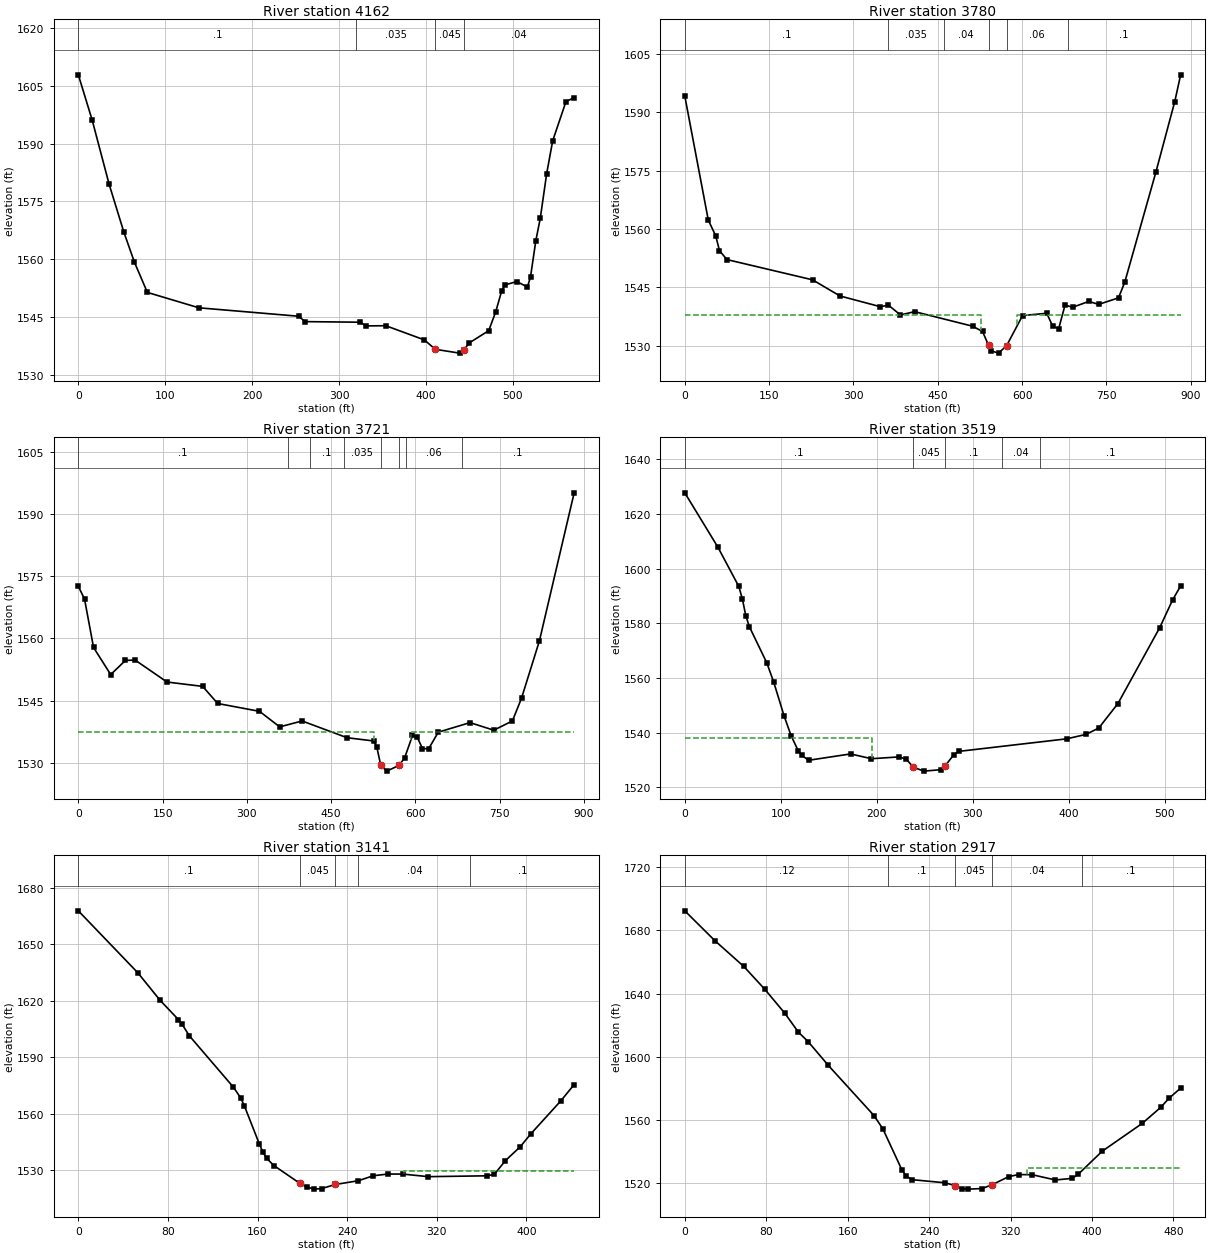
Type RM Length L Ch R = 1 ,4162    ,366.7,382.2,410.3
XS GIS Cut Line= 2
2009173.02518356276858.4861893772009437.87151895277363.640381793
#Sta/Elev= 30
       0 1607.88    15.9 1596.14    35.4 1579.48    52.4 1567.01    64.6 1559.18
    79.4 1551.37   138.7 1547.37   253.5 1545.18   260.9 1543.78   323.9 1543.63
   331.3 1542.67   353.7 1542.72     398 1539.04   410.7 1536.59   438.6  1535.6
   443.7  1536.5   449.9 1538.28   472.1 1541.43   480.1 1546.29   486.9 1551.66
   490.6  1553.3   504.4 1554.19   516.6 1552.78   520.2  1555.4   526.3  1564.8
   531.4  1570.6   538.8 1582.25   545.7 1590.75     561 1600.94   570.4 1601.94
#Mann= 4 ,-1 , 0
       0      .1       0     320    .035       0   410.7    .045       0
   443.7     .04       0
Bank Sta=410.7,443.7
XS Rating Curve= 0 ,0
Exp/Cntr(USF)=0,0
Exp/Cntr=0.5,0.3

Type RM Length L Ch R = 1 ,3780    ,57.6,58.7,56.2
XS GIS Cut Line= 3
2009116.33283701276890.6400575712009154.40978619277169.024863777
2008920.02501014277722.409858485
#Sta/Elev= 30
       0 1594.12    41.8 1562.27    55.1 1558.21    61.7 1554.42      75 1552.14
   227.3 1546.94     276  1542.8   347.9 1540.04   362.2 1540.44   383.6 1537.93
   408.9 1538.77   511.8 1535.04   529.6 1533.68   540.3 1530.13   543.9 1528.75
   558.1 1528.12   572.4 1530.02   600.9 1537.78   643.9 1538.34   654.3 1535.08
     665 1534.36   676.4 1540.46     690  1539.9   718.5 1541.39   736.3 1540.64
   771.5 1542.31   782.6 1546.32   837.9 1574.55   871.6 1592.72     882 1599.58
#Mann= 6 ,-1 , 0
       0      .1       0  360.98    .035       0  460.98     .04       0
   540.3    .045       0   572.4     .06       0  680.98      .1       0
#XS Ineff= 2 ,-1
       0   526.8    1538   591.5 881.952    1538
Permanent Ineff=
       F       F
Bank Sta=540.3,572.4
XS Rating Curve= 0 ,0
Exp/Cntr(USF)=0,0
Exp/Cntr=0.5,0.3

Type RM Length L Ch R = 1 ,3721    ,222.6,202.6,180
XS GIS Cut Line= 3
2009033.40970324276878.7938956052009088.40974094277166.486400498
2008871.79420785277714.794468649
#Sta/Elev= 30
       0 1572.58      11 1569.53    27.1 1557.81    57.6 1551.27    83.9 1554.69
     101 1554.78   157.8 1549.47   221.3 1548.41     248 1544.28   322.4 1542.39
   358.4 1538.63   398.2 1540.06   478.3 1536.01   525.9 1535.22   531.2 1533.74
   538.3  1529.3   548.9 1527.94   570.5 1529.32   580.6  1531.1   594.7 1536.55
     603 1536.18   612.4  1533.4   623.3 1533.32   640.6 1537.35     697 1539.66
   739.4 1537.83   772.5 1540.07   788.7 1545.55   820.5 1559.38   882.4 1595.18
#Mann= 8 ,-1 , 0
       0      .1       0   372.9    .035       0   412.9      .1       0
   472.9    .035       0   538.3    .045       0   570.5    .035       0
   582.9     .06       0   682.9      .1       0
#XS Ineff= 2 , 0
           525.8  1537.5   591.8          1537.5
Permanent Ineff=
       F       F
Bank Sta=538.3,570.5
XS Rating Curve= 0 ,0
Exp/Cntr(USF)=0,0
Exp/Cntr=0.5,0.3

Type RM Length L Ch R = 1 ,3519    ,364.7,377.7,388.3
XS GIS Cut Line= 3
2008691.37682252277238.9625728422008861.20569107277593.418676084
 2008837.2464316277714.624341606
#Sta/Elev= 30
       0 1627.72    34.4 1607.89    56.3 1593.46      60 1588.87    63.5 1582.84
    67.2 1578.79    85.4 1565.55    92.7 1558.42   103.6 1545.94   110.8 1538.84
   118.1 1533.41   121.8  1531.7     129 1529.88   172.7  1532.2   194.5 1530.45
   223.6 1531.12   230.9 1530.21   238.2 1527.33   249.1 1525.91   267.3 1526.45
   271.5 1527.95   280.4 1531.96   285.5 1533.14   397.8 1537.72   417.9 1539.33
   431.3 1541.67   451.3 1550.65   494.8 1578.38   508.2 1588.51   516.6 1593.66
#Mann= 5 ,-1 , 0
       0      .1       0   238.2    .045       0   271.5      .1       0
     330     .04       0     370      .1       0
#XS Ineff= 2 , 0
             195    1538
Permanent Ineff=
       F       F
Bank Sta=238.2,271.5
XS Rating Curve= 0 ,0
Exp/Cntr(USF)=0,0
Exp/Cntr=0.3,0.1

Type RM Length L Ch R = 1 ,3141    ,223.6,224.5,224.9
XS GIS Cut Line= 2
2008439.80754846277279.1847854742008440.96045433277721.791565814
#Sta/Elev= 30
       0 1667.64    53.2 1634.73    72.9 1620.26    89.3    1610    92.5 1607.62
    99.1 1601.38   138.5 1574.09     145 1568.38   148.3 1564.11   161.4 1544.28
   164.7 1539.75     168 1536.47   174.6 1532.58   197.5 1523.25   204.1 1521.11
   210.7 1520.09   217.2 1520.39   229.51522.557     250 1524.55   263.2 1527.18
   276.3 1528.08   289.4 1528.08   312.4  1526.7   364.9 1527.15   371.4 1527.94
   381.3 1535.24   394.4 1542.52   404.2 1549.58   430.5 1566.76   442.6 1575.53
#Mann= 5 ,-1 , 0
       0      .1       0   197.5    .045       0   229.5      .1       0
     250     .04       0     350      .1       0
#XS Ineff= 2 , 0
                          290.52          1529.6
Permanent Ineff=
       F       F
Bank Sta=197.5,229.5
XS Rating Curve= 0 ,0
Exp/Cntr(USF)=0,0
Exp/Cntr=0.3,0.1

Type RM Length L Ch R = 1 ,2917    ,361,372,378.4
XS GIS Cut Line= 2
2008221.45982415277240.5691365972008217.19155123277727.697628122
#Sta/Elev= 30
       0 1692.33    29.5 1673.47      58  1657.1    78.7  1642.6    98.4 1627.39
   111.5  1615.6   121.3 1609.46     141 1594.49   185.8 1562.79   194.6 1554.31
   213.2 1528.48   217.3 1524.63     223 1522.19   255.8  1520.2   265.7 1518.35
   272.2  1516.5   278.5 1516.19   291.9 1516.54   301.8 1518.94   318.2 1524.12
   328.1 1525.41   341.4 1525.29   364.1 1521.99   380.5 1522.98   386.5 1525.59
     410 1540.15   449.4  1557.8   467.8 1568.08   475.7 1573.72   487.1 1580.08
#Mann= 5 ,-1 , 0
       0     .12       0     200      .1       0   265.7    .045       0
   301.8     .04       0     390      .1       0
#XS Ineff= 2 , 0
                          335.77         1529.65
Permanent Ineff=
       F       F
Bank Sta=265.7,301.8
XS Rating Curve= 0 ,0
Exp/Cntr(USF)=0,0
Exp/Cntr=0.3,0.1

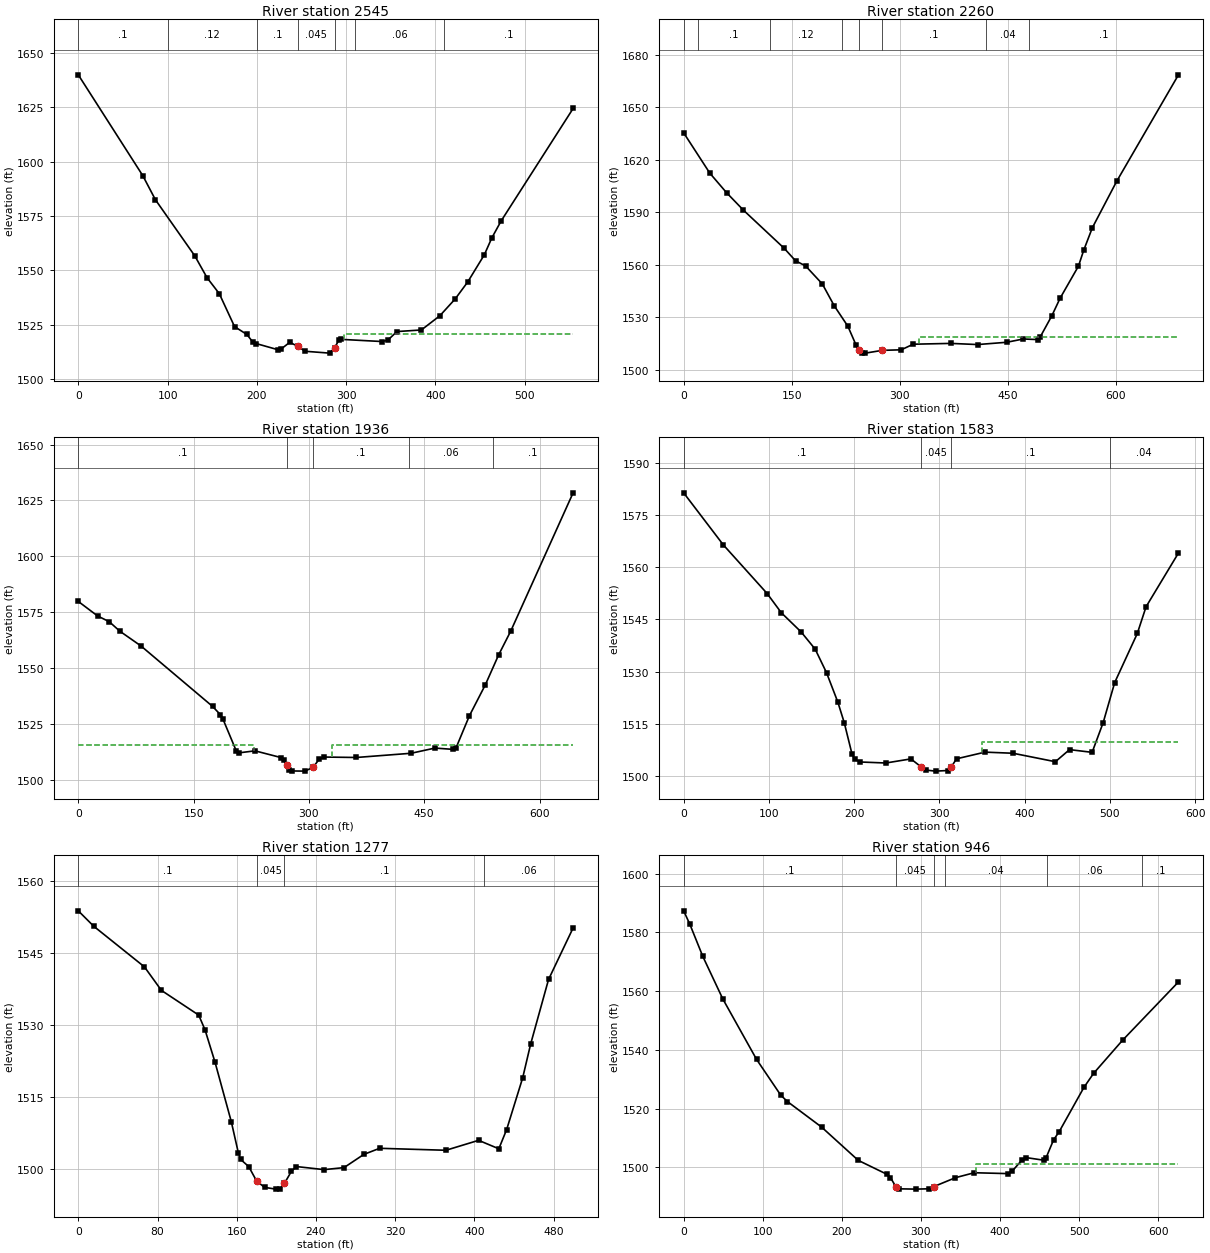
Type RM Length L Ch R = 1 ,2545    ,280.9,284.6,275.8
XS GIS Cut Line= 2
 2007929.4289883277240.3679784062007768.04251964277770.459014224
#Sta/Elev= 30
       0 1639.79    72.2 1593.54    86.4 1582.45   130.5 1556.69   144.2 1546.67
   157.9 1539.36     175 1524.23   188.8 1520.63   195.6 1517.08     199 1516.48
   223.1 1513.69   226.5 1513.75   236.8 1517.04   245.9 1515.18   253.9 1512.93
   281.4 1512.07     287 1514.42   291.6 1517.94   294.1 1518.39   339.7  1517.4
   346.5 1517.98   356.8 1521.97   384.2  1522.7   404.8 1529.19     422 1536.91
   436.1 1544.74   454.7 1557.21   463.1 1564.96   473.4 1572.66   554.1 1624.34
#Mann= 7 ,-1 , 0
       0      .1       0     100     .12       0     200      .1       0
   245.9    .045       0     287      .1       0     310     .06       0
     410      .1       0
#XS Ineff= 2 , 0
                           297.8         1520.75
Permanent Ineff=
       F       F
Bank Sta=245.9,287
XS Rating Curve= 0 ,0
Exp/Cntr=0.3,0.1

Type RM Length L Ch R = 1 ,2260    ,335.2,323.5,310.2
XS GIS Cut Line= 2
2007646.89685254277116.0087557372007537.47342068277794.347925937
#Sta/Elev= 30
       0 1635.54    36.4 1612.43    59.6 1601.29    82.9 1591.35   139.6 1569.51
   155.4 1562.36   169.3 1559.44   192.6 1549.11   209.2 1536.57     228 1524.97
   239.4 1514.21     2441511.119     248 1509.82   252.4 1509.58   275.71511.161
   302.1 1511.48   318.8 1514.68     371 1515.14   408.2 1514.48   448.7 1515.79
   471.7 1517.67   491.7 1517.32     495 1518.73   511.3 1530.97   522.7 1540.94
   548.2 1559.29   555.6 1568.47   567.5 1581.24   601.3  1607.8   687.1 1668.67
#Mann= 8 ,-1 , 0
       0     .12       0      20      .1       0     120     .12       0
     220      .1       0     244    .045       0   275.7      .1       0
     420     .04       0     480      .1       0
#XS Ineff= 2 , 0
                          326.93         1518.77
Permanent Ineff=
       F       F
Bank Sta=244,275.7
XS Rating Curve= 0 ,0
Exp/Cntr(USF)=0,0
Exp/Cntr=0.3,0.1

Type RM Length L Ch R = 1 ,1936    ,340.2,353.9,365.3
XS GIS Cut Line= 2
2007200.52672897 277120.138597342007396.96931567277733.112224378
#Sta/Elev= 30
       0 1579.75    25.1 1573.25    40.3 1570.67      54 1566.44    81.6  1559.8
   174.6 1532.76     185    1529   188.4 1526.89   205.6 1512.74   209.1 1511.94
   229.9 1512.84   264.2 1509.78   267.6 1508.94   271.1 1506.36   274.5 1504.33
     278 1503.83   294.9 1503.75   305.5 1505.49   313.2 1509.01   319.3 1510.06
   361.7 1509.86     433 1511.75     464 1514.08   488.1 1513.48   491.6 1514.32
   508.8 1528.55   529.5 1542.39   546.7 1555.72   562.7 1566.56   643.7 1628.39
#Mann= 5 ,-1 , 0
       0      .1       0   271.1    .045       0   305.5      .1       0
     430     .06       0     540      .1       0
#XS Ineff= 2 , 0
          227.94  1515.3  330.48         1515.48
Permanent Ineff=
       F       F
Bank Sta=271.1,305.5
XS Rating Curve= 0 ,0
Exp/Cntr(USF)=0,0
Exp/Cntr=0.3,0.1

Type RM Length L Ch R = 1 ,1583    ,323.8,305.4,286.4
XS GIS Cut Line= 2
2006983.28092689277136.947480108  2006900.579089277711.564146016
#Sta/Elev= 30
       0 1581.32    46.4 1566.43      98 1552.41   114.6 1546.91   137.8 1541.41
   154.3 1536.47   167.6 1529.72   180.9 1521.27   188.4 1515.38   197.4 1506.49
   200.7 1504.81   207.4 1504.09   237.2  1503.8   266.6 1504.98   278.2 1502.76
     284 1501.77   295.6 1501.47   310.1 1501.65   314.1 1502.72   320.1    1505
   353.5 1506.92   386.4  1506.6   436.1 1504.17   452.7 1507.64   479.2 1506.86
   492.2 1515.41   505.7 1526.89   532.2 1540.96   542.5 1548.64   580.5 1564.06
#Mann= 4 ,-1 , 0
       0      .1       0   278.2    .045       0   314.1      .1       0
     500     .04       0
#XS Ineff= 2 , 0
                           350.2          1509.8
Permanent Ineff=
       F       F
Bank Sta=278.2,314.1
XS Rating Curve= 0 ,0
Exp/Cntr(USF)=0,0
Exp/Cntr=0.3,0.1

Type RM Length L Ch R = 1 ,1277    ,339.3,331.3,324.1
XS GIS Cut Line= 2
2006546.45974655277296.5342990412006833.55326954277705.425074202
#Sta/Elev= 30
       0 1553.78    15.6 1550.57    66.8 1542.11    83.9 1537.22   121.6 1532.07
     128 1528.98   138.1 1522.24   154.5 1509.88   161.6  1503.4     164 1502.01
   172.1 1500.53   180.1 1497.51   188.1 1496.21   199.3 1495.84     204 1495.97
   208.1 1497.02   215.2 1499.55   220.2 1500.54   248.2  1499.9   268.3 1500.32
   288.3 1503.07   304.3 1504.34   371.2 1503.93   404.2    1506   424.6 1504.24
   432.5 1508.24   448.7 1519.02   456.7 1526.02   474.8 1539.49   499.6 1550.22
#Mann= 4 ,-1 , 0
       0      .1       0   180.1    .045       0   208.1      .1       0
     410     .06       0
Bank Sta=180.1,208.1
XS Rating Curve= 0 ,0
Exp/Cntr(USF)=0,0
Exp/Cntr=0.3,0.1

Type RM Length L Ch R = 1 ,946     ,268.8,275.5,281.7
XS GIS Cut Line= 2
2006223.43686955 277545.106427722006727.04690696 277916.25031785
#Sta/Elev= 30
       0 1587.37     7.8 1582.83    24.2 1571.87    49.5 1557.38    92.2 1536.79
   122.7 1524.65   131.1 1522.46   174.4 1513.75   220.7 1502.43   257.4 1497.63
   261.5 1496.56   268.2 1493.47   272.9 1492.73     294 1492.63   310.5 1492.75
   316.1 1493.47   343.7 1496.53   367.4 1498.21   410.1 1497.91   415.6 1498.82
   427.8 1502.56   432.6 1503.38   455.9 1502.45   458.3 1503.35   467.7 1509.41
   474.7 1512.14     506 1527.23   518.2 1532.01   554.9 1543.31   625.6 1563.17
#Mann= 6 ,-1 , 0
       0      .1       0   268.2    .045       0   316.1      .1       0
     330     .04       0     460     .06       0     580      .1       0
#XS Ineff= 2 , 0
                          369.92         1501.26
Permanent Ineff=
       F       F
Bank Sta=268.2,316.1
XS Rating Curve= 0 ,0
Exp/Cntr(USF)=0,0
Exp/Cntr=0.3,0.1

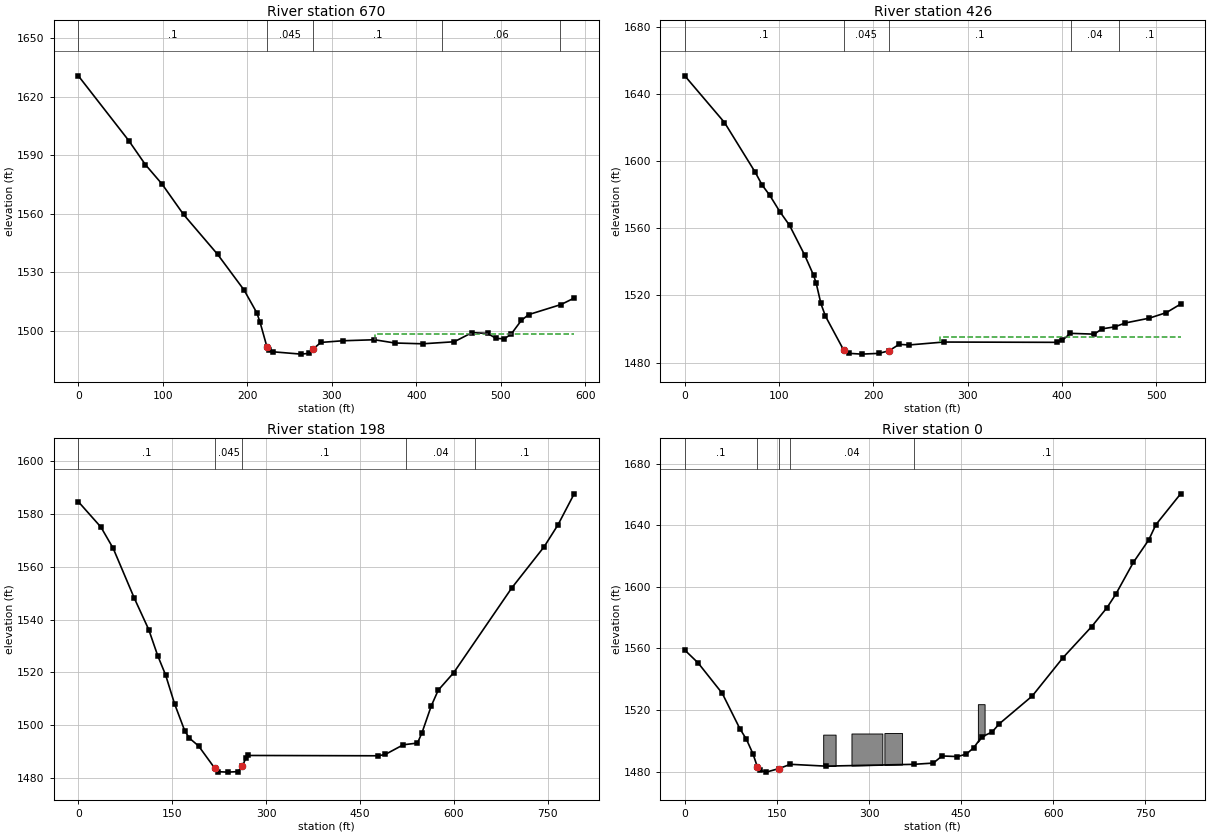
Type RM Length L Ch R = 1 ,670     ,258.4,244.5,230.6
XS GIS Cut Line= 2
2006102.60626223277736.9794651962006503.58487022278165.406013609
#Sta/Elev= 30
       0 1630.66    59.6 1597.51    79.4 1585.13      99 1575.23   124.5 1559.62
   164.8  1539.2   196.2 1520.86   211.2 1509.25   215.1 1504.34   223.2  1491.8
   225.6 1490.06   230.4 1489.25   263.7 1488.06   273.1 1488.46   277.7  1490.6
     287 1494.06   313.1 1494.91   350.4 1495.43   374.4 1493.77   407.4 1493.35
   444.9  1494.4   465.8 1499.06   484.3 1498.68   494.5 1496.09   504.1 1495.92
   512.2 1498.31   524.3 1505.33   532.9  1508.3   571.3 1513.48   586.8 1516.78
#Mann= 5 ,-1 , 0
       0      .1       0   223.2    .045       0   277.7      .1       0
     430     .06       0     570      .1       0
#XS Ineff= 2 , 0
                          350.87         1498.49
Permanent Ineff=
       F       F
Bank Sta=223.2,277.7
XS Rating Curve= 0 ,0
Exp/Cntr(USF)=0,0
Exp/Cntr=0.3,0.1

Type RM Length L Ch R = 1 ,426     ,227.3,228.3,229.3
XS GIS Cut Line= 2
2005979.24567084278044.2293235652006454.21437911278269.779790557
#Sta/Elev= 30
       0 1650.78    42.1 1622.98    74.8 1593.26      82 1585.75    90.2 1579.55
   100.7 1569.97   111.1 1561.73   127.1 1544.05   136.5 1532.12   139.4 1527.15
   144.3 1515.23   149.1 1507.72   168.4 1487.56   173.9 1485.54   187.4 1485.06
   205.5  1485.5   216.4 1486.99   227.3 1490.87   237.9 1490.52   274.5 1492.26
   394.4 1492.08   400.4 1493.32   408.9 1497.44   434.3 1496.95   442.3  1500.1
   456.1 1501.31     467  1503.6   492.4 1506.45   510.6 1509.76   525.8 1514.86
#Mann= 5 ,-1 , 0
       0      .1       0   168.4    .045       0   216.4      .1       0
     410     .04       0     460      .1       0
#XS Ineff= 2 , 0
                           271.1         1495.15
Permanent Ineff=
       F       F
Bank Sta=168.4,216.4
XS Rating Curve= 0 ,0
Exp/Cntr(USF)=0,0
Exp/Cntr=0.3,0.1

Type RM Length L Ch R = 1 ,198     ,197.6,197.6,197.6
XS GIS Cut Line= 3
2005883.32108599278154.9280606982005963.27812984278286.200819265
2006532.52454654278575.000888112
#Sta/Elev= 30
       0 1584.71    36.1 1575.06    55.7    1567    89.4 1548.11   112.5 1536.17
   126.8  1526.3   139.4 1518.98   153.7 1508.05   170.1 1497.71   177.4 1495.01
   192.1 1492.04   217.9  1483.6   223.8 1482.27   238.5 1482.12   254.7  1482.3
   262.1 1484.33   267.7 1487.58   271.7 1488.44   479.1 1488.32   490.2 1488.82
   519.1  1492.5   541.7 1493.14     549  1497.1   563.7  1507.2   574.8 1513.18
   599.7 1519.87   692.4 1552.01     744  1567.6   766.1  1575.9     792 1587.69
#Mann= 5 ,-1 , 0
       0      .1       0   217.9    .045       0   262.1      .1       0
  523.71     .04       0  633.71      .1       0
Bank Sta=217.9,262.1
XS Rating Curve= 0 ,0
Exp/Cntr(USF)=0,0
Exp/Cntr=0.3,0.1

Type RM Length L Ch R = 1 ,0       ,194.3,195.9,201.9
XS GIS Cut Line= 2
2005816.98713409278442.3102322562006556.98183326278764.980836929
#Sta/Elev= 30
       0 1558.92    21.6 1550.63      61 1530.83    89.6 1507.93   100.4 1500.93
   111.1 1491.44   118.3 1482.92   121.8 1480.92   132.6 1479.66   153.4 1481.99
     172 1484.74   229.2 1483.56   372.4 1484.72   404.6 1485.54   418.9 1490.16
     444 1489.77   458.3 1491.36   470.4  1495.5   483.3 1502.49   500.3 1505.71
     512 1511.03   565.7 1529.11   615.8 1554.02   662.3 1574.12   687.4 1586.49
   701.7  1595.2   730.3 1615.88   755.4 1630.51     767 1640.39   807.3 1660.44
#Mann= 5 ,-1 , 0
       0      .1       0   118.3    .045       0   153.4      .1       0
     172     .04       0   372.4      .1       0
#Block Obstruct= 4 ,-1
  225.34   245.5 1504.02  271.38  321.64 1504.75  325.01  353.73 1505.04
  477.21  488.11 1523.79
Bank Sta=118.3,153.4
XS Rating Curve= 0 ,0
Exp/Cntr(USF)=0,0
Exp/Cntr=0.3,0.1
LCMann Table=0

Chan Stop Cuts=-1
Use User Specified Reach Order=0
Composite Channel Slope=5